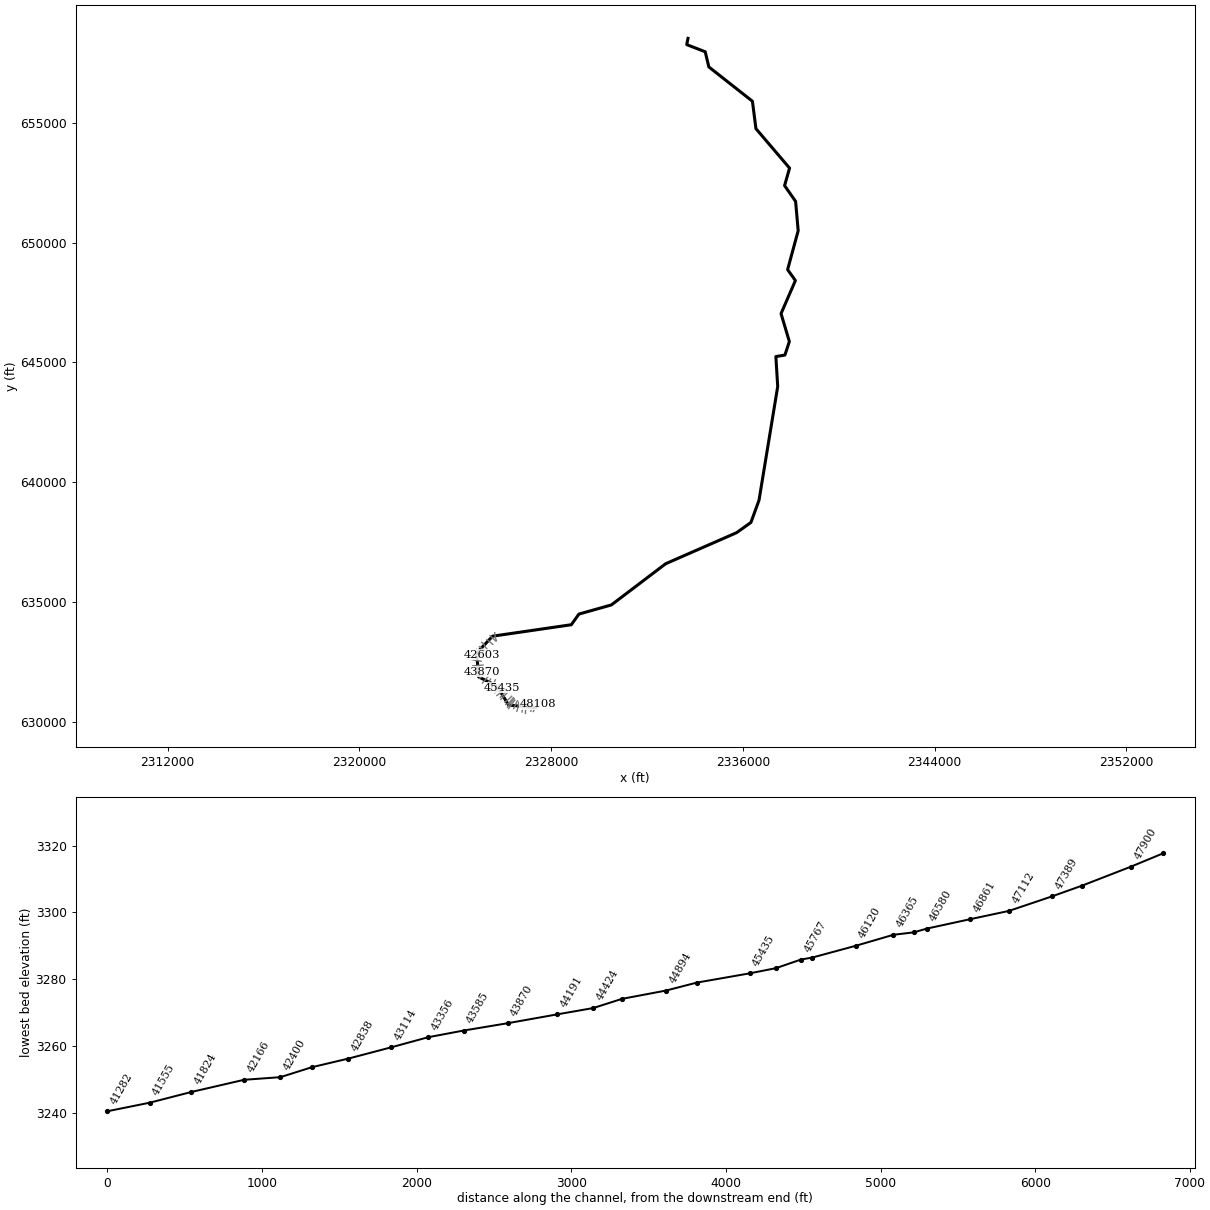
--- EFKGLADYFK.prj (project) ---

Proj Title=EFKGLADYFK
Current Plan=p01
Default Exp/Contr=0,0
English Units
Geom File=g01
Flow File=f01
Plan File=p01
BEGIN DESCRIPTION:
----------MODEL BY WOOD PLC 2022----------
AFH study
Randolph County, WV
HEC-RAS Version: RAS 6.2
Vertical Datum: NAVD88
Projection: NAD 1983 StatePlane West Virginia S FIPS 4702 (US Feet)
Terrain: 1-meter LIDAR (FEMA Region III 3DEP collected 2016-2018)
Land Use: 2019 NLCD
Hydrologic Method:
WV SIR2010-5033 regression equations
Additional Model Notes:
KWSEL tie-in with GLADYFK due to main stem name change
END DESCRIPTION:
DSS Export Rating Curves= 0
DSS Export Rating Curve Sorted= 0
DSS Export Volume Flow Curves= 0
DXF OffsetX= 0
DXF OffsetY= 0
DXF ScaleX= 0
DXF ScaleY= 0

--- EFKGLADYFK.p01 (plan) ---

Plan Title=Floodplain
Program Version=6.20
Short Identifier=Floodplain
Geom File=g01
Flow File=f01
Subcritical Flow
K Sum by GR= 0
Std Step Tol= 0.01
Critical Tol= 0.01
Num of Std Step Trials= 20
Max Error Tol= 0.3
Flow Tol Ratio= 0.001
Split Flow NTrial= 30
Split Flow Tol= 0.02
Split Flow Ratio= 0.02
Log Output Level= 0
Friction Slope Method= 1
Unsteady Friction Slope Method= 2
Unsteady Bridges Friction Slope Method= 1
Parabolic Critical Depth
Global Vel Dist= 0 , 0 , 0
Global Log Level= 0
CheckData=True
Encroach Param=-1 ,0,0, 0
Mapping Interval=1HOUR
Computation Time Step Use Courant=        0
Computation Time Step Use Time Series=    0
Computation Time Step Count To Double=0
Computation Time Step Max Doubling=0
Computation Time Step Max Halving=0
Computation Time Step Residence Courant=0
Run HTab= 0
Run UNet= 0
Run Sediment= 0
Run PostProcess= 0
Run WQNet= 0
Run RASMapper=-1
UNET Theta= 0
UNET Theta Warmup= 0
UNET ZTol= 0
UNET ZSATol= 0
UNET MxIter= 0
UNET Max Iter WO Improvement= 0
UNET MaxInSteps= 0
UNET DtIC= 0
UNET DtMin= 0
UNET MaxCRTS= 0
UNET WFStab= 0
UNET SFStab= 0
UNET WFX= 1
UNET SFX= 1
UNET Gravity=32.174
UNET 1D Methodology=Finite Difference
UNET DSS MLevel= 1
UNET Pardiso=0
UNET DZMax Abort= 0
UNET Use Existing IB Tables= 0
UNET Froude Reduction=False
UNET Froude Limit= 0
UNET Froude Power= 0
UNET D1 Cores= 0
UNET WindReference=Eulerian
UNET WindDragFormulation=Hsu (1988)
UNET D2 Coriolis=0
UNET D2 Cores= 0
UNET D2 Theta= 1
UNET D2 Theta Warmup= 1
UNET D2 Z Tol= 0.01
UNET D2 Volume Tol= 0.01
UNET D2 Max Iterations= 20
UNET D2 Equation= 0
UNET D2 RampUpFraction=0.1
UNET D2 TimeSlices= 1
UNET D2 Turbulence Formulation=Non-Conservative (original)
UNET D2 Eddy Viscosity=0.3
UNET D2 Transverse Eddy Viscosity=0.1
UNET D2 Smagorinsky Mixing=0
UNET D2 BCVolumeCheck=0
UNET D2 Cores=0
UNET D2 SolverType=PARDISO (Direct)
UNET D2 Minimum Iterations= 2147483647
UNET D2 Maximum Iterations= 2147483647
UNET D2 Restart Number= 10
UNET D2 Relaxation Coeff=1.3
UNET D2 SOR Precondition Iterations= 10
UNET D2 ILUT Maximum Fill= 8
UNET D2 ILUT Tolerance=1E-08
UNET D1D2 MaxIter= 0
UNET D1D2 ZTol=0.01
UNET D1D2 QTol=0.1
UNET D1D2 MinQTol=1
Write IC File= 0
Write IC File at Fixed DateTime=0
Write IC File at Sim End=0
Echo Input=False
Echo Parameters=False
Echo Output=False
Write Detailed= 0
HDF Write Warmup=0
HDF Write Time Slices=0
HDF Flush=0
HDF Compression= 1
HDF Chunk Size= 1
HDF Spatial Parts= 1
HDF Use Max Rows=0
HDF Fixed Rows= 1
Calibration Method= 0
Calibration Iterations= 20
Calibration Max Change=0.05
Calibration Tolerance=0.2
Calibration Maximum=1.5
Calibration Minimum=0.5
Calibration Optimization Method= 1
WQ AD Non Conservative
WQ ULTIMATE=-1
WQ Max Comp Step=1HOUR
WQ Output Interval=15MIN
WQ Output Selected Increments= 0
WQ Output face flow=0
WQ Output face velocity=0
WQ Output face area=0
WQ Output face dispersion=0
WQ Output cell volume=0
WQ Output cell surface area=0
WQ Output cell continuity=0
WQ Output cumulative cell continuity=0
WQ Output face conc=0
WQ Output face dconc_dx=0
WQ Output face courant=0
WQ Output face peclet=0
WQ Output face adv mass=0
WQ Output face disp mass=0
WQ Output cell mass=0
WQ Output cell source sink temp=0
WQ Output nsm pathways=0
WQ Output nsm derived pathways=0
WQ Create Restart=0
WQ Fixed Restart=0
WQ System Summary=0
WQ Write To DSS=0
Sorting and Armoring Iterations= 10
XS Update Threshold= 0.02
Bed Roughness Predictor= 0
Hydraulics Update Threshold= 0.02
Energy Slope Method= 1
Volume Change Method= 1
Sediment Retention Method= 0
Sediment TS Multiplier= 1
Warm Up Method= 0
XS Weighting Method= 0
Number of US Weighted Cross Sections= 1
Number of DS Weighted Cross Sections= 1
Upstream XS Weight=0
Main XS Weight=1
Downstream XS Weight=0
Number of DS XS's Weighted with US Boundary= 1
Upstream Boundary Weight= 1
Weight of XSs Associated with US Boundary= 0
Number of US XS's Weighted with DS Boundary= 1
Downstream Boundary Weight= 0.5
Weight of XSs Associated with DS Boundary= 0.5
Percentile Method= 0
Sediment Output Level= 3
Mass or Volume Output= 0
Output Increment Type= 1
Profile and TS Output Increment= 1
Transport Output Increment 1
XS Output Flag= 0
XS Output Increment= 10
Read HDF5 Sediment Hotstart= 0
Sediment Hotstart Type= 0
Write Gradation File= 0
Read Gradation Hotstart= 0
Write HDF5 File= 1
Write Binary Output= 1
Write DSS Sediment File= 0
DSS Sediment Output Type= 1
SV Curve= 0
Specific Gage Flag= 0
Subcell Erosion Methods= 0
Subcell Deposition Methods= 0
Advection Scheme= 1
Matrix Solver= 0
Implicit Weighting Factor= 1
Maximum Outer Loop Convergence Iterations= 5
Convergence Maximum Absolute= 0.001
Convergence RMSE= 0.0001
Grain Fractions Max Abs Error= 0.001
Max Subgrid Regions= 1
Max Subgrid Length Scale= 3.402823E+38
Initial Layer Thickness= 3.402823E+38
Min Layer Thickness= 3.402823E+38
Max Layer Thickness= 3.402823E+38
Number of Layers= 5

--- EFKGLADYFK.f01 (steady flow) ---

Flow Title=Flow
Program Version=6.20
Number of Profiles= 1
Profile Names=P100yr
River Rch & RM=EFKGLADYFK,Main            ,48108
     386
River Rch & RM=EFKGLADYFK,Main            ,44191
     430
River Rch & RM=EFKGLADYFK,Main            ,41824
     479
River Rch & RM=EFKGLADYFK,Main            ,39009
     543
River Rch & RM=EFKGLADYFK,Main            ,37600
     604
River Rch & RM=EFKGLADYFK,Main            ,34561
     674
River Rch & RM=EFKGLADYFK,Main            ,33354
     779
River Rch & RM=EFKGLADYFK,Main            ,29184
     870
River Rch & RM=EFKGLADYFK,Main            ,25886
     983
River Rch & RM=EFKGLADYFK,Main            ,23837
    1110
River Rch & RM=EFKGLADYFK,Main            ,20596
    1320
River Rch & RM=EFKGLADYFK,Main            ,18055
    1470
River Rch & RM=EFKGLADYFK,Main            ,14361
    1740
River Rch & RM=EFKGLADYFK,Main            ,9556
    2200
River Rch & RM=EFKGLADYFK,Main            ,0
    3560
Boundary for River Rch & Prof#=EFKGLADYFK,Main            , 1
Up Type= 0
Dn Type= 1
Dn Known WS=2838.7
DSS Import GetInterval= 0
DSS Import GetPeak= 0
DSS Import FillOption= 0

--- EFKGLADYFK.g01 (geometry) ---

Geom Title=Geometry
Program Version=6.20

River Reach=EFKGLADYFK      ,Main
Reach XY= 30
2327361.97000001630585.741999999     2326223.742630696.958000019
2325744.47800002631482.9050000012324972.86400002631876.135000005
     2324894.131 632868.669000032325557.26000004633570.753000021
2328841.44100003 634049.245000022329159.13999999634493.418000013
     2330513.227634875.4210000192332781.43900001636597.220000014
2335738.89300002 637892.260000022336336.50300002638320.100000009
2336674.14700003639247.0300000162337454.35600004643997.030000001
2337376.73700003 645245.086000012337754.23400001645308.378000021
2337940.17000003645872.4370000212337593.24100001647038.573000014
     2338192.086648418.6430000222337867.42900001648876.283000007
     2338308.323650501.0890000162338200.39900002651725.557999998
2337741.06999998652382.896000013     2337948.376 653114.36300002
2336545.41900001654762.1149999952336399.69500002655905.494000003
2334580.53500004657338.400000021     2334429.564657971.185000002
     2333658.361658269.8560000062333711.04517532658532.188815863

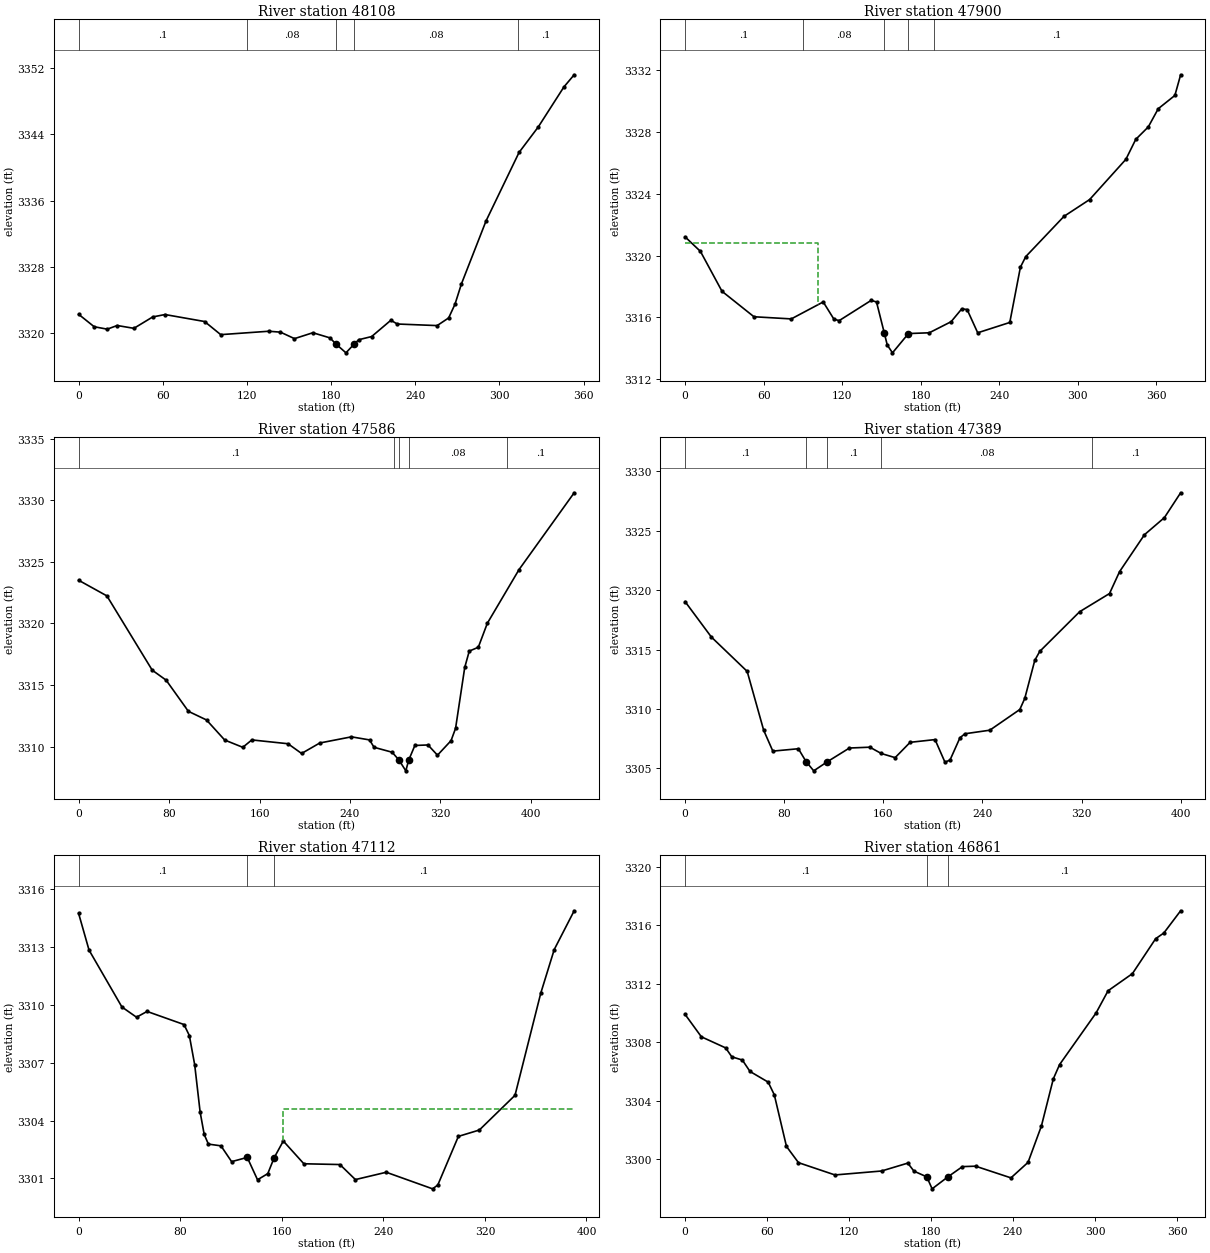
Type RM Length L Ch R = 1 ,48108   ,204.3,207.6,207.1
XS GIS Cut Line= 3
2327258.76851035630426.8039334772327372.62377538630630.709292793
2327430.52306737630735.559358476
#Sta/Elev= 30
       0 3322.31    11.1 3320.81    20.4 3320.52    27.5 3320.96    39.4 3320.62
    52.8 3321.99    61.6 3322.28    89.8 3321.44   101.3 3319.86   135.6 3320.27
   143.9 3320.16   153.9 3319.38     167 3320.09   179.2 3319.47   183.4 3318.74
   190.6 3317.67   196.43318.723   199.7 3319.25   208.9 3319.63   222.6 3321.59
   227.2 3321.14   255.6 3320.95   263.8 3321.87   268.3 3323.51   272.9 3325.96
   290.5 3333.56     314 3341.79   327.7 3344.86     346 3349.68   353.3 3351.14
#Mann= 5 ,-1,0
       0      .1       0     120     .08       0   183.4    .045       0
   196.4     .08       0  313.54      .1       0
Bank Sta=183.4,196.4
XS Rating Curve= 0 ,0
Exp/Cntr=0.3,0.1

Type RM Length L Ch R = 1 ,47900   ,310.5,314.4,314
XS GIS Cut Line= 2
2327154.27005751630437.455383183 2327223.8543037630809.463468562
#Sta/Elev= 30
       0 3321.21    11.7 3320.27    28.2 3317.68    52.6 3316.03    81.1 3315.89
   105.5 3316.99   113.7 3315.87   117.7 3315.78   142.1 3317.09   146.2 3316.99
   152.2 3314.96   154.4  3314.2   158.4 3313.69   170.6 3314.94   186.5 3314.99
   203.2 3315.71   211.3 3316.54   215.4  3316.5   223.5 3314.99     248 3315.66
   256.1 3319.24   260.2 3319.93   289.4 3322.54     309 3323.63   336.7 3326.24
   344.2 3327.53   353.8 3328.34   361.4 3329.52   374.1 3330.38   378.5 3331.72
#Mann= 5 ,-1,0
       0      .1       0      90     .08       0   152.2    .045       0
   170.6     .08       0     190      .1       0
#XS Ineff= 2 , 0
           101.3  3320.8
Permanent Ineff=
       F       F
Bank Sta=152.2,170.6
XS Rating Curve= 0 ,0
Exp/Cntr(USF)=0,0
Exp/Cntr=0.3,0.1

Type RM Length L Ch R = 1 ,47586   ,198.9,196.6,188.8
XS GIS Cut Line= 3
2326928.03598126630348.1762299362326941.36964419630616.512773908
2326951.35932455630785.821002763
#Sta/Elev= 30
       0 3323.51      25 3322.24    65.1 3316.21    77.4  3315.4    97.1 3312.87
   113.1 3312.17   129.2 3310.54   145.2 3309.95   153.2 3310.55   185.2 3310.24
   197.2 3309.45   213.3  3310.3   241.3  3310.8   257.3 3310.55   261.3 3309.95
   277.3 3309.55   283.3 3308.92   289.4 3308.04   291.9  3308.9   297.4  3310.1
     309 3310.14   317.4 3309.31   329.4 3310.49   333.4 3311.49   341.5 3316.43
   345.5 3317.76   353.5 3318.07   361.5 3320.02   389.5 3324.37   438.3 3330.61
#Mann= 5 ,-1,0
       0      .1       0  278.67     .08       0   283.3    .045       0
   291.9     .08       0  378.67      .1       0
Bank Sta=283.3,291.9
XS Rating Curve= 0 ,0
Exp/Cntr=0.3,0.1

Type RM Length L Ch R = 1 ,47389   ,271.5,276.8,273.5
XS GIS Cut Line= 3
2326781.49603887630404.580296366 2326820.3026377630558.048604782
2326846.52245604630798.191054401
#Sta/Elev= 30
       0 3319.03    21.2 3316.05    50.1 3313.16    63.4 3308.21    70.8 3306.45
    91.4 3306.65    97.63305.575   103.8 3304.79   114.7 3305.55   132.6 3306.71
   149.1 3306.78   158.3 3306.25   169.5  3305.9   181.6 3307.19   201.7 3307.42
   209.7 3305.52   213.8  3305.7   221.8 3307.57   225.8 3307.91   245.9 3308.21
   270.1 3309.95   274.1 3310.88   282.2 3314.09   286.2 3314.84   318.4 3318.18
   342.5 3319.71   350.6 3321.55   370.7 3324.66   386.8  3326.1   399.9 3328.19
#Mann= 5 ,-1,0
       0      .1       0    97.6    .045       0   114.7      .1       0
   158.3     .08       0   328.3      .1       0
Bank Sta=97.6,114.7
XS Rating Curve= 0 ,0
Exp/Cntr(USF)=0,0
Exp/Cntr=0.3,0.1

Type RM Length L Ch R = 1 ,47112   ,253.8,251,244.8
XS GIS Cut Line= 3
2326569.94614068630433.2757804222326604.44899833 630555.13730718
 2326648.3799999 630815.12089789
#Sta/Elev= 30
       0 3314.74     8.2 3312.84    34.1 3309.89    45.6 3309.36    53.9 3309.66
      83 3308.98    87.2 3308.41    91.4  3306.9    95.7 3304.44    98.9 3303.28
   102.2 3302.78   112.1 3302.69   120.5 3301.87   132.8 3302.09   140.9 3300.93
     149 3301.25     1543302.073   161.2 3302.94   177.4 3301.76   205.8 3301.72
     218 3300.94   242.3 3301.32   278.8 3300.46   282.9 3300.66   299.1 3303.18
   315.6 3303.51   343.7 3305.31     364 3310.61   374.6 3312.87   390.3 3314.88
#Mann= 3 ,-1,0
       0      .1       0   132.8    .045       0     154      .1       0
#XS Ineff= 2 , 0
                          161.22         3304.62
Permanent Ineff=
       F       F
Bank Sta=132.8,154
XS Rating Curve= 0 ,0
Exp/Cntr=0.3,0.1

Type RM Length L Ch R = 1 ,46861   ,281.9,281.6,282.9
XS GIS Cut Line= 2
2326434.91296652630546.4251058992326592.81567902630872.935799542
#Sta/Elev= 30
       0 3309.91    11.9 3308.38    29.7 3307.62    34.2 3307.01    41.9 3306.79
    47.5 3306.01    60.8 3305.28    65.3 3304.41    74.2 3300.88      83 3299.77
   109.7 3298.93   143.8  3299.2     163 3299.74   167.5 3299.19   176.9  3298.8
   180.8 3297.98   192.5 3298.81     203  3299.5   212.6 3299.53   238.5 3298.73
     251 3299.79   260.8 3302.28   269.5  3305.5   274.1 3306.48   300.8 3310.01
   309.6 3311.53   327.4  3312.7   344.4 3315.09   350.4 3315.48   362.7    3317
#Mann= 3 ,-1,0
       0      .1       0   176.9    .045       0   192.5      .1       0
Bank Sta=176.9,192.5
XS Rating Curve= 0 ,0
Exp/Cntr(USF)=0,0
Exp/Cntr=0.3,0.1

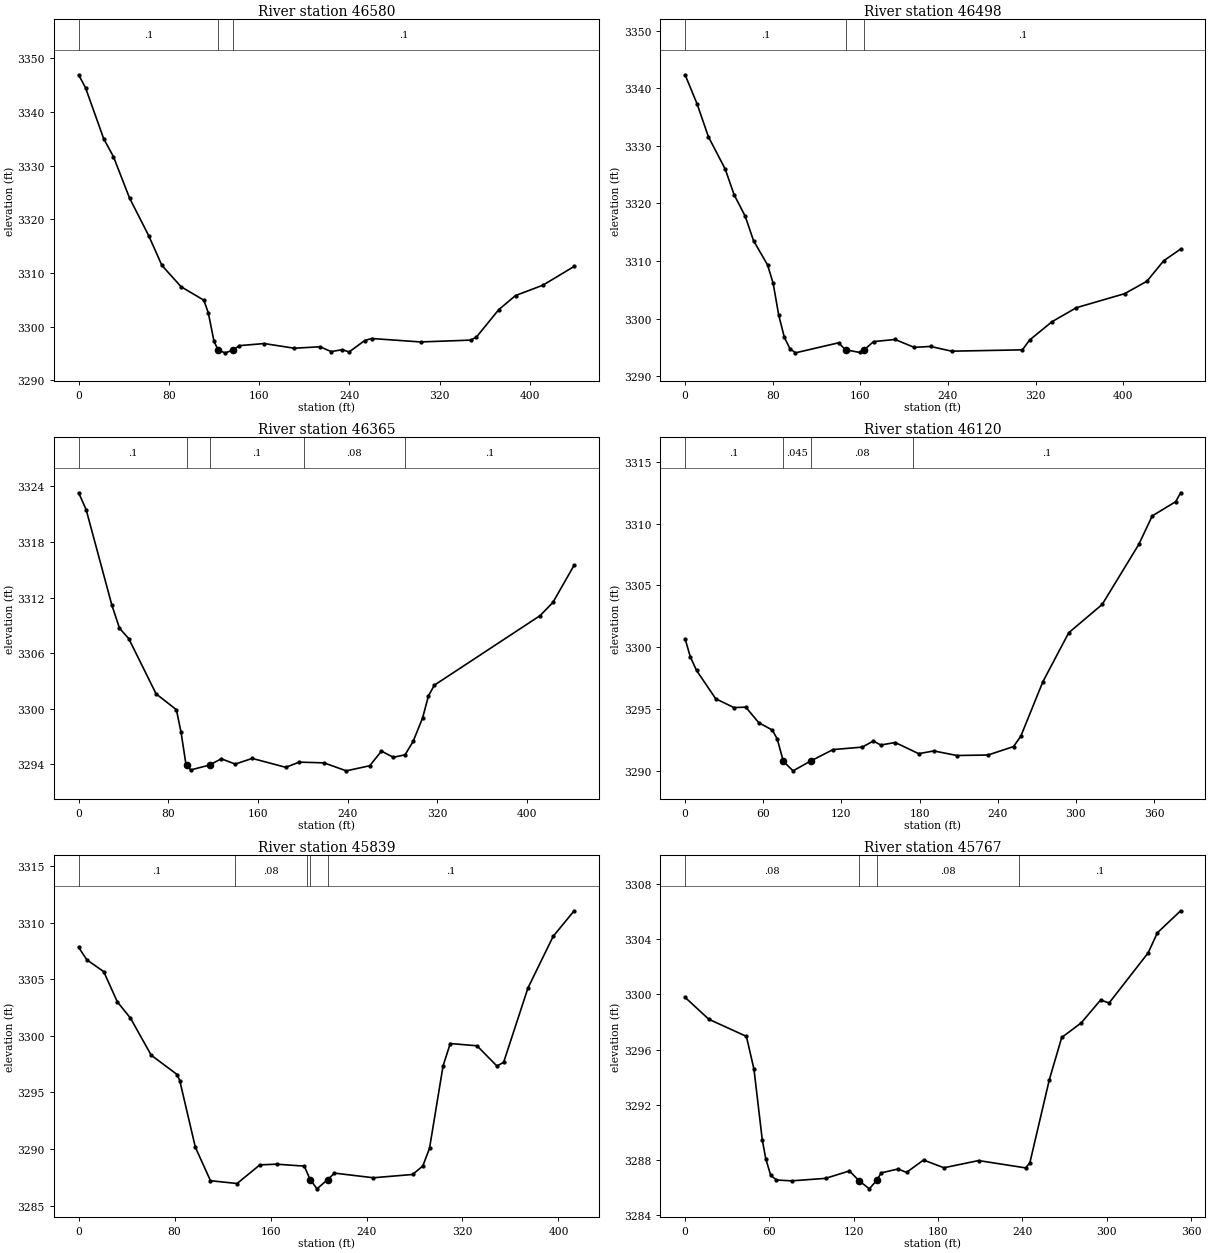
Type RM Length L Ch R = 1 ,46580   ,81,81.6,82.7
XS GIS Cut Line= 2
2326226.05529299630548.2458595732326484.90914695630903.233504736
#Sta/Elev= 30
       0 3346.94     6.1 3344.53    22.2 3335.04    30.9 3331.67    45.1    3324
    62.3 3316.89    73.8 3311.44    90.9 3307.45     111 3304.96     115 3302.56
     120  3297.3   123.83295.631   129.9 3295.15   136.7 3295.64   142.5 3296.49
   164.5 3296.88   191.1 3296.01   214.1 3296.28   223.9 3295.38   233.8 3295.74
   239.8 3295.31   253.6 3297.44   259.8 3297.82   303.1 3297.18   347.7 3297.52
   352.6 3298.07   372.4 3303.19   387.3 3305.82   411.6 3307.75   439.3 3311.25
#Mann= 3 ,-1,0
       0      .1       0   123.8    .045       0   136.7      .1       0
Bank Sta=123.8,136.7
XS Rating Curve= 0 ,0
Exp/Cntr=0.3,0.1

Type RM Length L Ch R = 1 ,46498   ,131.8,133,117.5
XS GIS Cut Line= 2
2326177.44846933630606.0505621492326457.61302297630961.363420543
#Sta/Elev= 30
       0 3342.33    10.9  3337.3    21.3 3331.56    36.7 3325.93    44.7 3321.53
    54.9 3317.76    62.5 3313.52    75.3 3309.32    80.4 3306.13    85.5 3300.58
    90.6 3296.76    95.7 3294.79   100.8 3294.05   140.1 3295.79   146.5 3294.58
   159.4 3294.12   163.7  3294.6   172.1    3296   191.7 3296.37   209.2    3295
   224.1 3295.16   243.4 3294.34     308 3294.57   314.6 3296.28   335.1 3299.46
   357.3 3301.89   401.3 3304.32   421.7 3306.48     437 3310.03   452.5 3312.07
#Mann= 3 ,-1,0
       0      .1       0   146.5    .045       0   163.7      .1       0
Bank Sta=146.5,163.7
XS Rating Curve= 0 ,0
Exp/Cntr(USF)=0,0
Exp/Cntr=0.3,0.1

Type RM Length L Ch R = 1 ,46365   ,241,245.1,243
XS GIS Cut Line= 3
2326105.82899046630719.5050045752326220.00819702630759.211212409
2326427.55892788631004.407331795
#Sta/Elev= 30
       0 3323.32     6.7  3321.5    29.5 3311.26    36.4 3308.72    44.8 3307.56
    69.1 3301.62    87.2 3299.91    91.4 3297.46    95.7 3294.05   96.613293.938
    99.9  3293.4   116.8 3293.94   127.3 3294.61   139.7 3294.04   154.9 3294.65
   184.8 3293.69   196.8 3294.25   218.9 3294.17   238.8 3293.31   259.7 3293.86
   270.2 3295.44   280.7 3294.77   291.2 3295.04   298.4 3296.48   306.9 3299.03
   312.1  3301.4   317.4 3302.56   411.7 3310.06   423.2  3311.5   442.1 3315.51
#Mann= 5 ,-1,0
       0      .1       0   96.61    .045       0   116.8      .1       0
  200.89     .08       0  290.89      .1       0
Bank Sta=96.61,116.8
XS Rating Curve= 0 ,0
Exp/Cntr(USF)=0,0
Exp/Cntr=0.3,0.1

Type RM Length L Ch R = 1 ,46120   ,276.4,281.1,278.2
XS GIS Cut Line= 3
2326064.77935149630820.1294188982326169.69668392630888.017041445
 2326356.0872529631062.701572035
#Sta/Elev= 30
       0 3300.68       4 3299.22     8.8 3298.12    23.5 3295.83    37.4 3295.12
    46.6 3295.15    56.5  3293.9    66.9  3293.3    70.7 3292.59    75.4 3290.77
    82.9    3290    96.63290.807   113.6 3291.72     136 3291.92   144.5 3292.41
   150.2 3292.09   161.3 3292.29   179.3 3291.39     191 3291.61   208.6 3291.24
   232.5 3291.28   252.1 3291.96   257.7  3292.8   274.7 3297.22   294.5 3301.17
   320.2 3303.46   348.3 3308.32   358.6 3310.62   376.6 3311.77   380.4 3312.49
#Mann= 4 ,-1,0
       0      .1       0    75.4    .045       0    96.6     .08       0
  174.97      .1       0
Bank Sta=75.4,96.6
XS Rating Curve= 0 ,0
Exp/Cntr=0.3,0.1

Type RM Length L Ch R = 1 ,45839   ,72,72.2,71.7
XS GIS Cut Line= 2
2325901.68522616630930.065762416 2326188.3187941631227.538414861
#Sta/Elev= 30
       0 3307.84     6.8 3306.74    20.9 3305.69    32.3 3303.01    43.2 3301.58
    60.5  3298.3    82.1 3296.59    84.3 3296.05    97.3 3290.16   109.9  3287.2
   132.1 3286.95   151.1  3288.6     165 3288.66   188.1 3288.49     1933287.302
   198.7 3286.48   207.6  3287.3   213.3 3287.87   245.7 3287.46   278.4 3287.75
   286.9  3288.5   292.5 3290.06   303.8 3297.35   309.8 3299.33   332.1 3299.13
   348.7 3297.34   354.3 3297.67   374.6 3304.25   395.6 3308.81   413.1 3311.07
#Mann= 5 ,-1,0
       0      .1       0     130     .08       0     190      .1       0
     193    .045       0   207.6      .1       0
Bank Sta=193,207.6
XS Rating Curve= 0 ,0
Exp/Cntr(USF)=0,0
Exp/Cntr=0.3,0.1

Type RM Length L Ch R = 1 ,45767   ,159.8,161.2,160.6
XS GIS Cut Line= 4
  2325879.493539631020.8272049522326010.16403784631136.395083329
2326031.83301504631184.9861231012326119.82219517631273.631938901
#Sta/Elev= 30
       0 3299.79    16.9  3298.2    43.6 3296.96      49 3294.57    54.9 3289.45
    57.4 3288.07    60.9 3286.88      65 3286.54    75.7 3286.48    99.9 3286.66
   116.9  3287.2   123.7 3286.49   131.1  3285.9   136.23286.509   139.6 3287.06
   151.5 3287.34   157.5 3287.09   169.6 3287.99   184.1 3287.43   208.8 3287.95
   242.2 3287.42   245.2 3287.77   259.1 3293.82   267.9 3296.88   281.8 3297.94
   295.6  3299.6   301.6 3299.38   329.4 3303.02     336 3304.48   352.5 3306.07
#Mann= 4 ,-1,0
       0     .08       0   123.7    .045       0   136.2     .08       0
  237.65      .1       0
Bank Sta=123.7,136.2
XS Rating Curve= 0 ,0
Exp/Cntr(USF)=0,0
Exp/Cntr=0.3,0.1

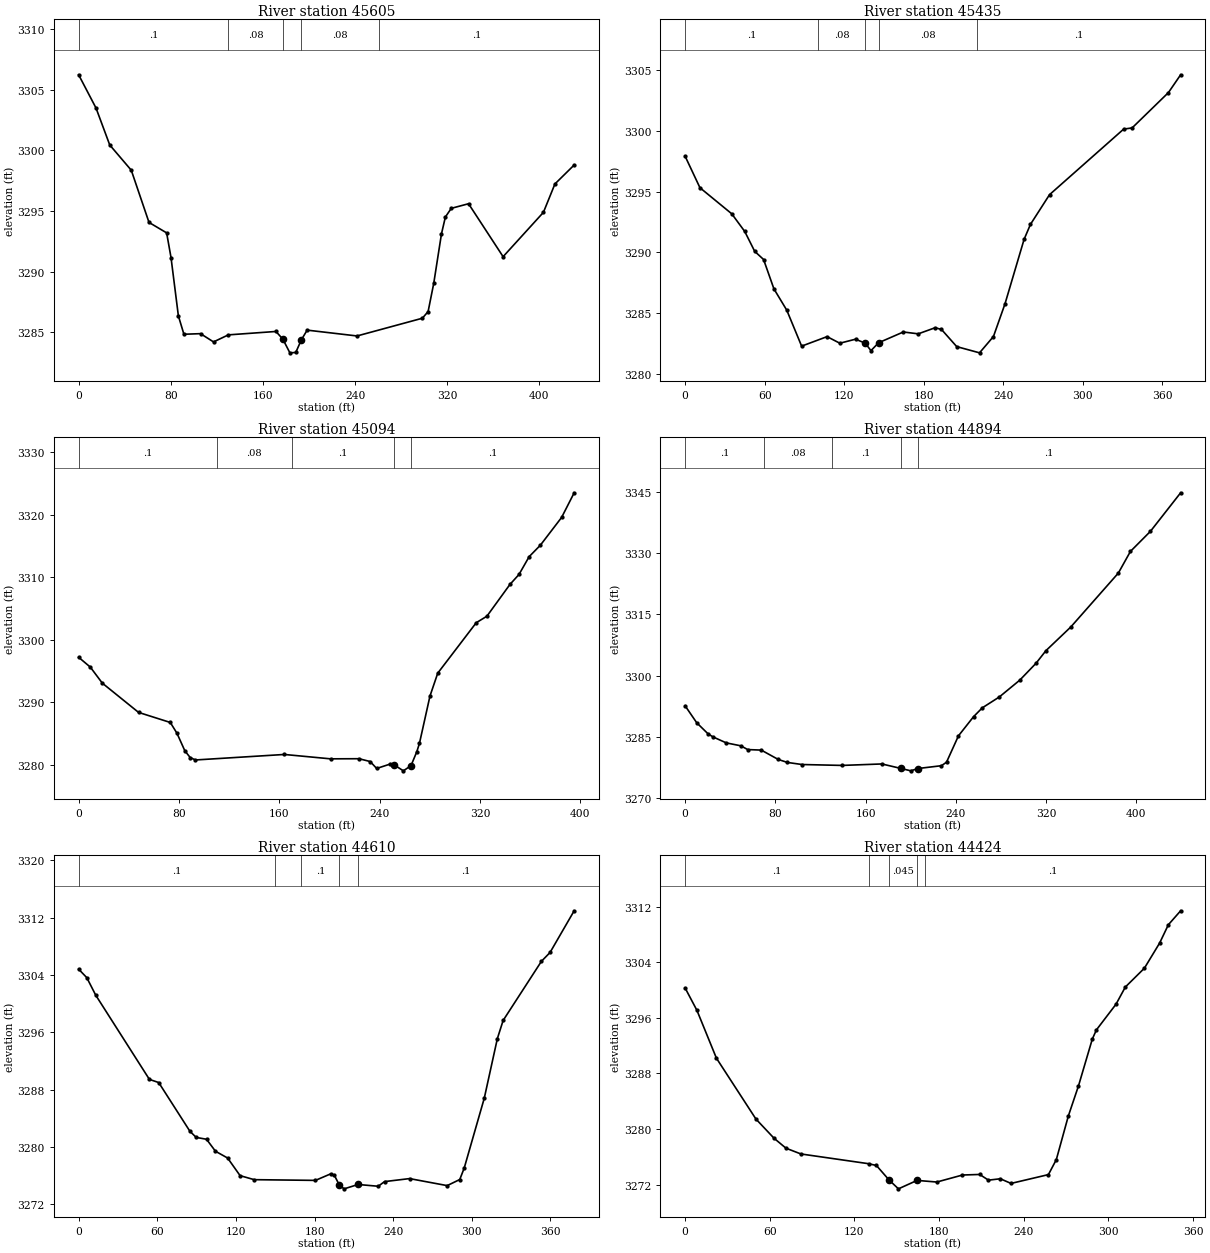
Type RM Length L Ch R = 1 ,45605   ,167.7,170.7,170.6
XS GIS Cut Line= 3
2325736.36137207 631092.362652752325869.95661194631198.456444777
2326077.50322421631354.348001625
#Sta/Elev= 30
       0 3306.22    15.1 3303.48      27 3300.44    45.7 3298.36    61.1 3294.06
    76.4  3293.2    80.2 3291.17    86.6 3286.36    91.4 3284.85   105.8  3284.9
   117.1 3284.22     130  3284.8   171.3 3285.08   177.33284.446   183.4 3283.32
   188.5 3283.35   193.4  3284.4   198.4 3285.19   241.7 3284.71   298.4 3286.17
   303.4 3286.72   308.3 3289.05     315 3293.12   318.4 3294.51   323.5 3295.22
   338.5  3295.6   368.5 3291.24   403.5 3294.89   413.5 3297.23   430.2 3298.79
#Mann= 5 ,-1,0
       0      .1       0     130     .08       0   177.3    .045       0
   193.4     .08       0   260.6      .1       0
Bank Sta=177.3,193.4
XS Rating Curve= 0 ,0
Exp/Cntr=0.3,0.1

Type RM Length L Ch R = 1 ,45435   ,333.5,341,341.6
XS GIS Cut Line= 2
2325654.79496805631208.2689313022325966.71973317631414.211536841
#Sta/Elev= 30
       0  3297.9    11.2 3295.31    35.2 3293.17      45 3291.72    52.5 3290.09
    59.2 3289.42      67 3287.01    76.7 3285.26    87.9 3282.31   107.1 3283.09
   116.7 3282.55   128.6 3282.88   135.9 3282.55   140.2 3281.94     146 3282.59
   164.6 3283.47   175.9 3283.32   188.6 3283.82   193.4 3283.68   204.9 3282.27
   222.1 3281.76   232.6  3283.1   241.3 3285.78   255.7 3291.07   260.5  3292.3
   274.9 3294.74   330.8 3300.12   337.2 3300.22   364.6 3303.12   373.8 3304.58
#Mann= 5 ,-1,0
       0      .1       0     100     .08       0   135.9    .045       0
     146     .08       0     220      .1       0
Bank Sta=135.9,146
XS Rating Curve= 0 ,0
Exp/Cntr(USF)=0,0
Exp/Cntr=0.3,0.1

Type RM Length L Ch R = 1 ,45094   ,196,199.9,201.6
XS GIS Cut Line= 2
2325557.15304928631300.7122393282325854.72890309631560.836951193
#Sta/Elev= 30
       0 3297.17     9.3  3295.6    18.9 3293.03    47.8 3288.35    73.1 3286.74
    78.4 3285.02    84.7 3282.21      89 3281.12    93.2 3280.74   164.1 3281.62
   200.9 3280.92   223.6 3280.94   232.5 3280.49   237.7 3279.38   248.4 3280.08
   251.9 3279.92     259    3279   265.1 3279.84   269.7 3282.06   271.8 3283.39
   280.2 3290.97   286.4 3294.63   317.1  3302.7   325.6 3303.74     344 3308.83
   351.2 3310.42   359.3 3313.27   368.2 3315.09   385.2 3319.55   395.2 3323.49
#Mann= 5 ,-1,0
       0      .1       0     110     .08       0     170      .1       0
   251.9    .045       0   265.1      .1       0
Bank Sta=251.9,265.1
XS Rating Curve= 0 ,0
Exp/Cntr=0.3,0.1

Type RM Length L Ch R = 1 ,44894   ,281,283.5,280.1
XS GIS Cut Line= 2
2325488.87060395631350.8652530462325673.13504049631749.502694178
#Sta/Elev= 30
       0 3292.58    10.3 3288.41    20.2 3285.73    24.6 3284.95    36.5 3283.47
    49.4 3282.75    55.5 3281.83    67.5  3281.7    82.6  3279.4    90.7 3278.67
   103.7 3278.16   139.2 3277.94   174.4  3278.3   191.1 3277.21   200.1 3276.61
   206.1 3277.17   227.2 3277.87   231.7 3278.73   242.3 3285.21   255.7 3289.91
   263.4 3292.07   278.5 3294.74   296.6 3298.86     311    3303   319.8  3306.1
   341.8  3311.9     384 3325.15   394.7 3330.46   412.4 3335.38   439.2 3344.85
#Mann= 5 ,-1,0
       0      .1       0      70     .08       0     130      .1       0
   191.1    .045       0   206.1      .1       0
Bank Sta=191.1,206.1
XS Rating Curve= 0 ,0
Exp/Cntr(USF)=0,0
Exp/Cntr=0.3,0.1

Type RM Length L Ch R = 1 ,44610   ,186.5,186.7,182.2
XS GIS Cut Line= 2
2325266.51942961 631466.21357274 2325474.3064946 631782.09675964
#Sta/Elev= 30
       0 3304.81     6.2 3303.63    13.1 3301.16      54 3289.42    61.1 3288.98
    84.9 3282.18    89.7 3281.32    97.6 3281.06   104.4 3279.39   113.7 3278.44
   123.2 3275.98     134 3275.42   180.7 3275.32   192.3 3276.23   195.1 3276.04
   198.93274.671   202.6 3274.14   213.23274.748   228.6  3274.5   233.4 3275.15
   252.5 3275.57   281.2 3274.59   290.8 3275.44   294.2 3277.04   309.5 3286.79
   319.5 3295.12   323.9 3297.65   353.1  3305.9   359.7 3307.14   378.1 3312.96
#Mann= 5 ,-1,0
       0      .1       0     150     .08       0     170      .1       0
   198.9    .045       0   213.2      .1       0
Bank Sta=198.9,213.2
XS Rating Curve= 0 ,0
Exp/Cntr=0.3,0.1

Type RM Length L Ch R = 1 ,44424   ,228.2,232.6,231.5
XS GIS Cut Line= 2
2325134.67520149631615.3789007532325365.98034512631879.646362129
#Sta/Elev= 30
       0  3300.3     8.4 3297.07    22.2 3290.19    50.2 3281.43      63 3278.67
    71.5 3277.23    82.1  3276.4     130    3275   135.6 3274.74   144.63272.646
   151.2 3271.38   164.43272.594   178.4 3272.36   196.6 3273.37   208.8 3273.45
     215 3272.63   223.4 3272.83     231 3272.16   257.5 3273.43   263.1 3275.59
   271.6 3281.86   278.8  3286.2   288.6 3292.94   291.5 3294.26   305.4 3297.96
     312 3300.43   325.5 3303.14   336.3 3306.76   342.5  3309.4   351.2 3311.41
#Mann= 5 ,-1,0
       0      .1       0     130     .08       0   144.6    .045       0
   164.4     .08       0     170      .1       0
Bank Sta=144.6,164.4
XS Rating Curve= 0 ,0
Exp/Cntr(USF)=0,0
Exp/Cntr=0.3,0.1

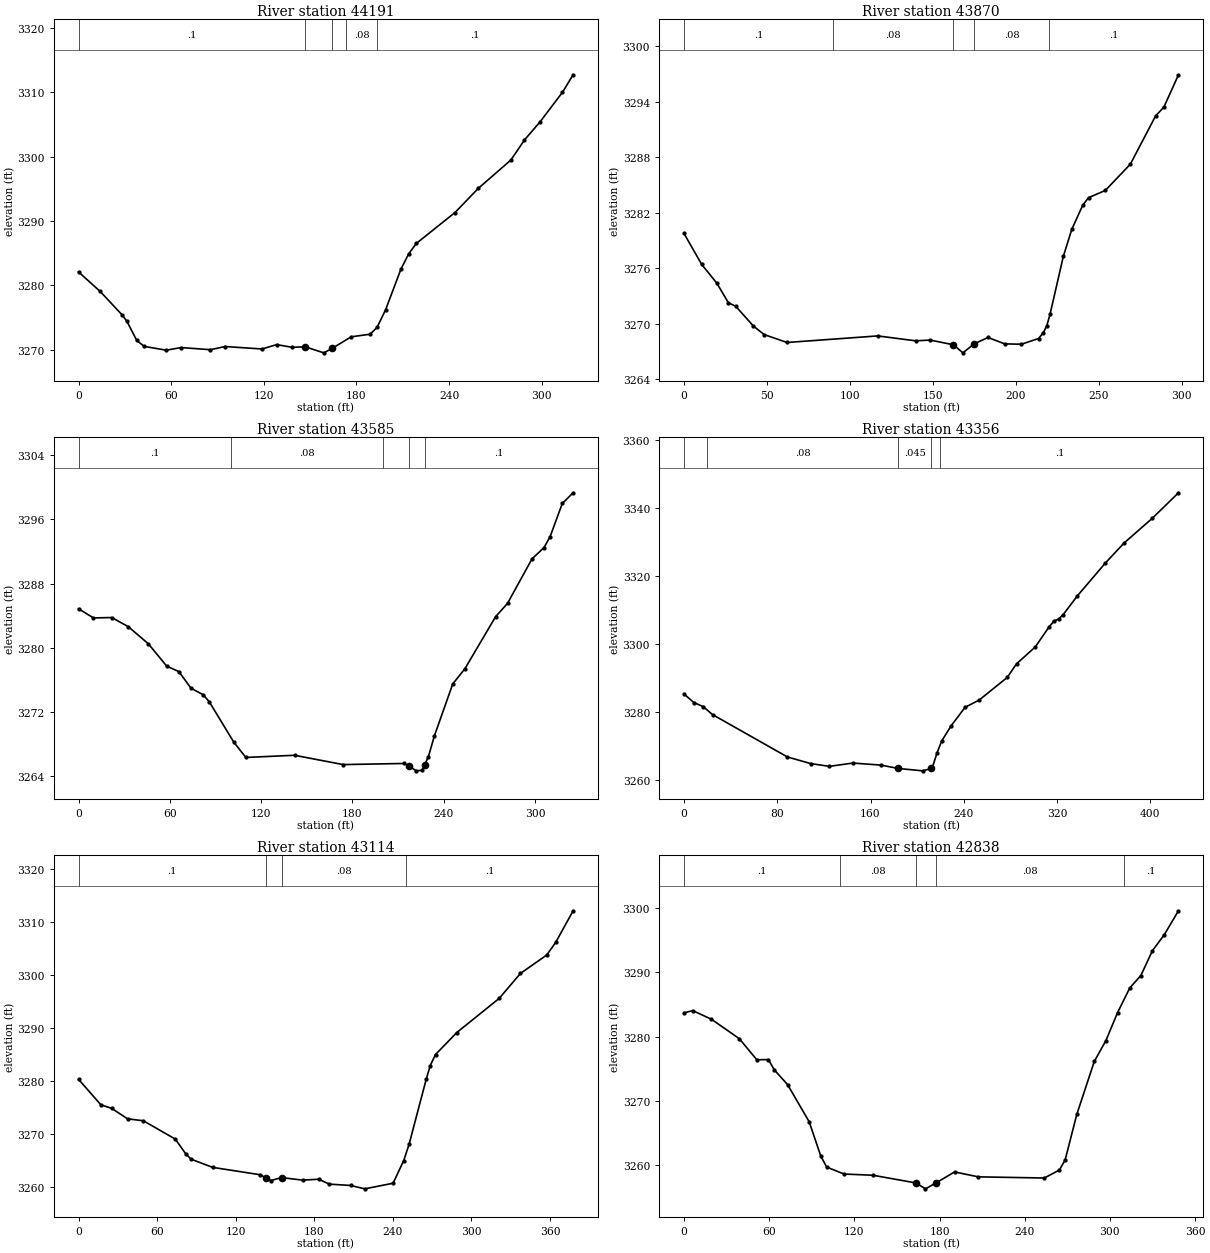
Type RM Length L Ch R = 1 ,44191   ,321.9,320.7,314.2
XS GIS Cut Line= 4
2324996.53936278631805.5435548782325118.84365276631884.904167701
2325131.70279883631909.1701564782325249.37390578631997.328487537
#Sta/Elev= 30
       0 3282.07      14 3279.04    28.2 3275.39    31.3  3274.4    37.7 3271.41
    42.5 3270.49    56.8  3269.9    66.3 3270.31    85.4 3269.98    94.9 3270.47
   118.8 3270.09   128.3 3270.77   138.3 3270.35   146.83270.427   158.8 3269.49
   164.2 3270.17   176.5 3271.98   188.8 3272.39   193.3 3273.44   198.8 3276.16
   208.8 3282.52   213.8 3284.89   218.8 3286.52   243.8 3291.32   258.8 3295.06
     280 3299.49   288.8 3302.61   298.8  3305.4   313.4 3310.02   320.3 3312.75
#Mann= 5 ,-1,0
       0      .1       0   146.8    .045       0   164.2      .1       0
  173.26     .08       0  193.26      .1       0
Bank Sta=146.8,164.2
XS Rating Curve= 0 ,0
Exp/Cntr=0.3,0.1

Type RM Length L Ch R = 1 ,43870   ,285.6,285.5,276.4
XS GIS Cut Line= 2
 2324878.9517533631914.6749237132325115.16961609632096.396436662
#Sta/Elev= 30
       0 3279.76    10.7  3276.4    19.8 3274.38    26.8 3272.25    31.2 3271.88
    41.9 3269.73    48.3 3268.82    62.1 3267.96   116.8 3268.67   139.6 3268.14
   148.4 3268.22   162.4 3267.71   168.1 3266.84   174.83267.802   183.2  3268.5
   193.3 3267.81   203.4 3267.77   213.7 3268.39   216.6 3269.03   218.6 3269.74
   220.6 3271.01   228.6 3277.26   233.7 3280.19   240.3  3282.8   243.8 3283.62
   253.9  3284.4     269 3287.24   284.2 3292.46   289.2 3293.41     298 3296.91
#Mann= 5 ,-1,0
       0      .1       0      90     .08       0   162.4    .045       0
   174.8     .08       0     220      .1       0
Bank Sta=162.4,174.8
XS Rating Curve= 0 ,0
Exp/Cntr(USF)=0,0
Exp/Cntr=0.3,0.1

Type RM Length L Ch R = 1 ,43585   ,226.3,228.3,225.7
XS GIS Cut Line= 2
2324758.32716015632162.0931481332325083.34650507632165.644965372
#Sta/Elev= 30
       0 3284.85     9.8 3283.71    21.8 3283.76    32.6 3282.63    45.9 3280.48
    57.9  3277.7    65.9 3277.02    73.9 3274.94    81.9 3274.13    85.9 3273.25
   101.9 3268.25   109.9 3266.31   141.9 3266.58   173.9 3265.42   213.9 3265.56
   217.1 3265.26   221.9 3264.64   225.9 3264.72   227.43265.355   229.9 3266.42
   233.9 3269.04   245.9 3275.48   253.9 3277.38     274 3283.85   281.9 3285.53
     298 3291.08   305.9 3292.49   309.9 3293.86   317.9 3297.99     325 3299.32
#Mann= 5 ,-1,0
       0      .1       0     100     .08       0     200      .1       0
   217.1    .045       0   227.4      .1       0
Bank Sta=217.1,227.4
XS Rating Curve= 0 ,0
Exp/Cntr=0.3,0.1

Type RM Length L Ch R = 1 ,43356   ,237.8,242.1,239
XS GIS Cut Line= 2
2324735.72561501632334.4037122082325158.64980836632365.792617182
#Sta/Elev= 30
       0 3285.26     8.5 3282.75    16.5 3281.54    24.5  3279.2    88.7 3266.74
   108.7 3264.78   124.8 3263.97   144.8 3264.94   168.9 3264.34   183.8 3263.35
   204.6 3262.65   212.1 3263.34     213 3263.56     217  3267.9   221.1 3271.47
   229.1 3275.88   241.1 3281.34   253.2 3283.48   277.2 3290.11   285.2 3294.12
   301.3  3299.1   313.3 3305.09   317.3 3306.67   321.3  3307.3   325.3 3308.63
   337.4 3314.13   361.4 3323.78   377.5 3329.69   401.6 3336.93   424.1 3344.45
#Mann= 5 ,-1,0
       0      .1       0      20     .08       0   183.8    .045       0
   212.1     .08       0     220      .1       0
Bank Sta=183.8,212.1
XS Rating Curve= 0 ,0
Exp/Cntr(USF)=0,0
Exp/Cntr=0.3,0.1

Type RM Length L Ch R = 1 ,43114   ,273.3,276.1,273.1
XS GIS Cut Line= 2
2324707.33448867632588.2380997942325079.73646894632525.472693259
#Sta/Elev= 30
       0 3280.27    17.1 3275.45    25.2 3274.81    37.4 3272.82    49.5 3272.45
    73.9 3268.98      82 3266.15      86 3265.19   102.3 3263.65   138.8 3262.25
   142.8  3261.7   146.9 3261.16     155 3261.72   171.2 3261.23   183.4 3261.41
   191.5 3260.48   207.7 3260.23   218.6 3259.59   240.2 3260.65   248.3 3264.92
   252.4 3267.99   265.6 3280.38   268.6 3282.88   272.6 3284.97   288.9 3289.13
   321.3 3295.59   337.5  3300.3   357.5 3303.76   364.4 3306.16   377.7 3312.13
#Mann= 4 ,-1,0
       0      .1       0   142.8    .045       0     155     .08       0
     250      .1       0
Bank Sta=142.8,155
XS Rating Curve= 0 ,0
Exp/Cntr=0.3,0.1

Type RM Length L Ch R = 1 ,42838   ,237.7,235.2,231.1
XS GIS Cut Line= 2
2324746.15262335632798.320356197 2325086.0449028632722.045317109
#Sta/Elev= 30
       0 3283.69     6.2 3284.04    19.4 3282.69      39 3279.66    51.3 3276.38
    59.5 3276.39    63.6 3274.81      73 3272.49    88.2  3266.7    96.3 3261.39
   100.5 3259.63   112.8 3258.54   133.1 3258.35   163.4 3257.15   170.1 3256.23
   177.33257.119   190.6 3258.87   207.3  3258.1   253.8 3257.92   264.4 3259.16
   268.5 3260.76   276.7 3267.86     289 3276.11   297.2 3279.37   305.4 3283.73
     314 3287.58   321.8 3289.52     330 3293.41   338.2 3295.85   348.3 3299.62
#Mann= 5 ,-1,0
       0      .1       0     110     .08       0   163.4    .045       0
   177.3     .08       0     310      .1       0
Bank Sta=163.4,177.3
XS Rating Curve= 0 ,0
Exp/Cntr(USF)=0,0
Exp/Cntr=0.3,0.1

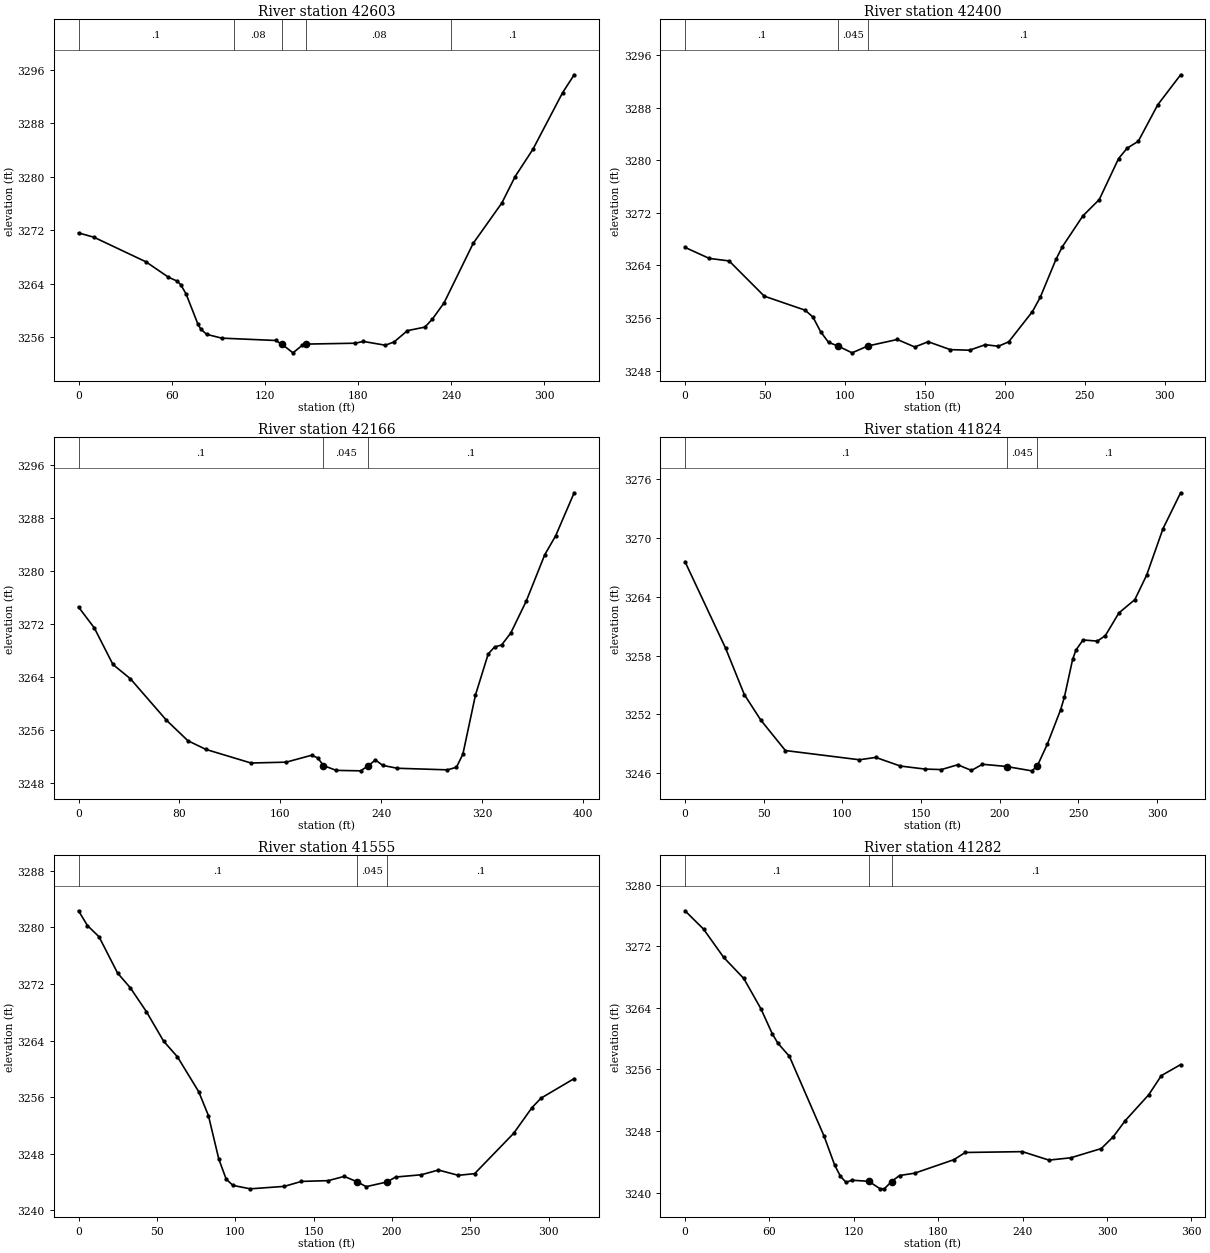
Type RM Length L Ch R = 1 ,42603   ,200.4,202.7,202.4
XS GIS Cut Line= 2
2324881.11640837633017.6089667382325109.56985805632794.613727754
#Sta/Elev= 30
       0  3271.6     9.9 3270.96    43.4 3267.28    57.9 3264.98    63.6 3264.38
    65.8 3263.87    69.3 3262.46    76.9 3257.95    78.8  3257.2    82.5 3256.43
    92.2 3255.86   126.9 3255.51     1313254.954   138.1 3253.66     144 3254.77
   146.7 3254.97   178.1  3255.1   183.5 3255.36   197.6  3254.8   203.3  3255.3
   211.8 3256.98   223.1 3257.51   227.9 3258.71   235.4 3261.13   254.2 3270.05
   272.6 3276.07   281.2 3280.04   292.7 3284.14   311.7 3292.56   319.2 3295.26
#Mann= 5 ,-1,0
       0      .1       0     100     .08       0     131    .045       0
   146.7     .08       0     240      .1       0
Bank Sta=131,146.7
XS Rating Curve= 0 ,0
Exp/Cntr=0.3,0.1

Type RM Length L Ch R = 1 ,42400   ,214.8,234.8,226.5
XS GIS Cut Line= 2
2325006.94649391633133.1498235052325259.85846563632953.836573718
#Sta/Elev= 30
       0 3266.73    15.2 3265.05    27.6 3264.67    49.6 3259.31    75.1 3257.18
      80 3256.15    84.9 3253.88    89.8 3252.28    95.5 3251.75   104.5 3250.69
   114.3 3251.73   132.8 3252.72   143.7 3251.58   152.1 3252.38   165.9 3251.18
     178 3251.09   187.8 3251.93     196 3251.69   202.5 3252.37   217.3 3256.96
   222.2 3259.14     232 3264.89   236.1 3266.86   248.9 3271.53   259.1    3274
   271.2 3280.24   276.6 3281.83   283.5 3282.86   295.7 3288.42     310 3292.98
#Mann= 3 ,-1,0
       0      .1       0    95.5    .045       0   114.3      .1       0
Bank Sta=95.5,114.3
XS Rating Curve= 0 ,0
Exp/Cntr(USF)=0,0
Exp/Cntr=0.3,0.1

Type RM Length L Ch R = 1 ,42166   ,328,341.2,340.2
XS GIS Cut Line= 4
2325103.17538666633313.7381106742325207.85426615633233.925677288
2325214.42062288633178.4764427132325338.50562634633014.882652423
#Sta/Elev= 30
       0 3274.61    12.5 3271.46    27.3 3265.94    41.1 3263.79    69.6 3257.55
    86.7 3254.44     101 3253.13   136.7 3251.08   164.6 3251.21   184.7 3252.25
   189.6 3251.85   194.1  3250.7   204.2 3249.97   223.5  3249.9   229.6 3250.65
   235.3 3251.55     241 3250.73   252.5 3250.29   292.4 3250.05   299.5 3250.44
   304.6 3252.41   314.6 3261.35   324.7 3267.54   329.7 3268.58   335.3 3268.88
   342.6  3270.7   354.8 3275.49   369.5  3282.5   378.1 3285.34   392.8 3291.84
#Mann= 3 ,-1,0
       0      .1       0   194.1    .045       0   229.6      .1       0
Bank Sta=194.1,229.6
XS Rating Curve= 0 ,0
Exp/Cntr=0.3,0.1

Type RM Length L Ch R = 1 ,41824   ,257.1,269.7,257.2
XS GIS Cut Line= 2
2325323.22242863633432.5342501282325564.75588521633230.509752581
#Sta/Elev= 30
       0 3267.59    25.8 3258.76    37.7 3254.03    48.2 3251.42    63.8 3248.32
   110.8 3247.38   121.2 3247.62   136.8 3246.74   152.5 3246.43   162.9 3246.38
   173.3 3246.87     182 3246.29     189 3246.92   204.7 3246.69   204.7 3246.68
   220.3 3246.25  223.72 3246.71   230.2 3248.97   238.7  3252.5   241.1  3253.8
   246.3 3257.63   248.4 3258.57   252.9  3259.6     262 3259.48   267.1 3260.05
   275.7 3262.36   285.8 3263.71   293.3 3266.21   303.7 3270.95   314.9 3274.61
#Mann= 3 ,-1,0
       0      .1       0   204.7    .045       0  223.72      .1       0
Bank Sta=204.7,223.72
XS Rating Curve= 0 ,0
Exp/Cntr(USF)=0,0
Exp/Cntr=0.3,0.1

Type RM Length L Ch R = 1 ,41555   ,278,272.6,267.1
XS GIS Cut Line= 2
2325451.99960817633590.1277373692325683.59381892633374.896594592
#Sta/Elev= 30
       0 3282.36     5.7 3280.27    13.1 3278.68    24.9 3273.56      33 3271.48
    43.3  3268.1    54.3 3263.92    63.1 3261.71    76.7 3256.77    82.9 3253.38
    89.5 3247.25    94.2 3244.41    98.5 3243.53   109.5 3243.04   131.3 3243.39
   142.2 3244.09   159.3  3244.2   169.5  3244.8   177.7 3244.04   183.5 3243.35
   196.8 3244.01   202.3 3244.71   218.7 3245.03   229.6  3245.7   242.3 3244.95
   252.7 3245.19   277.6 3250.89   289.3 3254.53   295.1 3255.87   316.2 3258.63
#Mann= 3 ,-1,0
       0      .1       0   177.7    .045       0   196.8      .1       0
Bank Sta=177.7,196.8
XS Rating Curve= 0 ,0
Exp/Cntr=0.3,0.1

Type RM Length L Ch R = 1 ,41282   ,214.6,217.6,217
XS GIS Cut Line= 3
2325646.93940459633718.7413194292325676.45038065633491.274899172
2325720.27257688633376.386501808
#Sta/Elev= 30
       0 3276.59    13.2 3274.21    27.5 3270.54    41.8  3267.8      54 3263.86
    62.1  3260.6    66.1 3259.38    74.2  3257.7    98.9 3247.32   106.4 3243.57
   110.5 3242.12   114.5 3241.33   118.5 3241.61   130.6 3241.47   138.7  3240.5
   141.7 3240.49   146.8 3241.44   152.5 3242.22   163.2 3242.52   191.2 3244.28
   199.2 3245.21   239.8 3245.32   258.7 3244.22   274.2 3244.52   295.9 3245.72
   304.4 3247.25     313 3249.36   329.6  3252.7   338.6 3255.19   352.3 3256.62
#Mann= 3 ,-1,0
       0      .1       0   130.6    .045       0   146.8      .1       0
Bank Sta=130.6,146.8
XS Rating Curve= 0 ,0
Exp/Cntr(USF)=0,0
Exp/Cntr=0.3,0.1