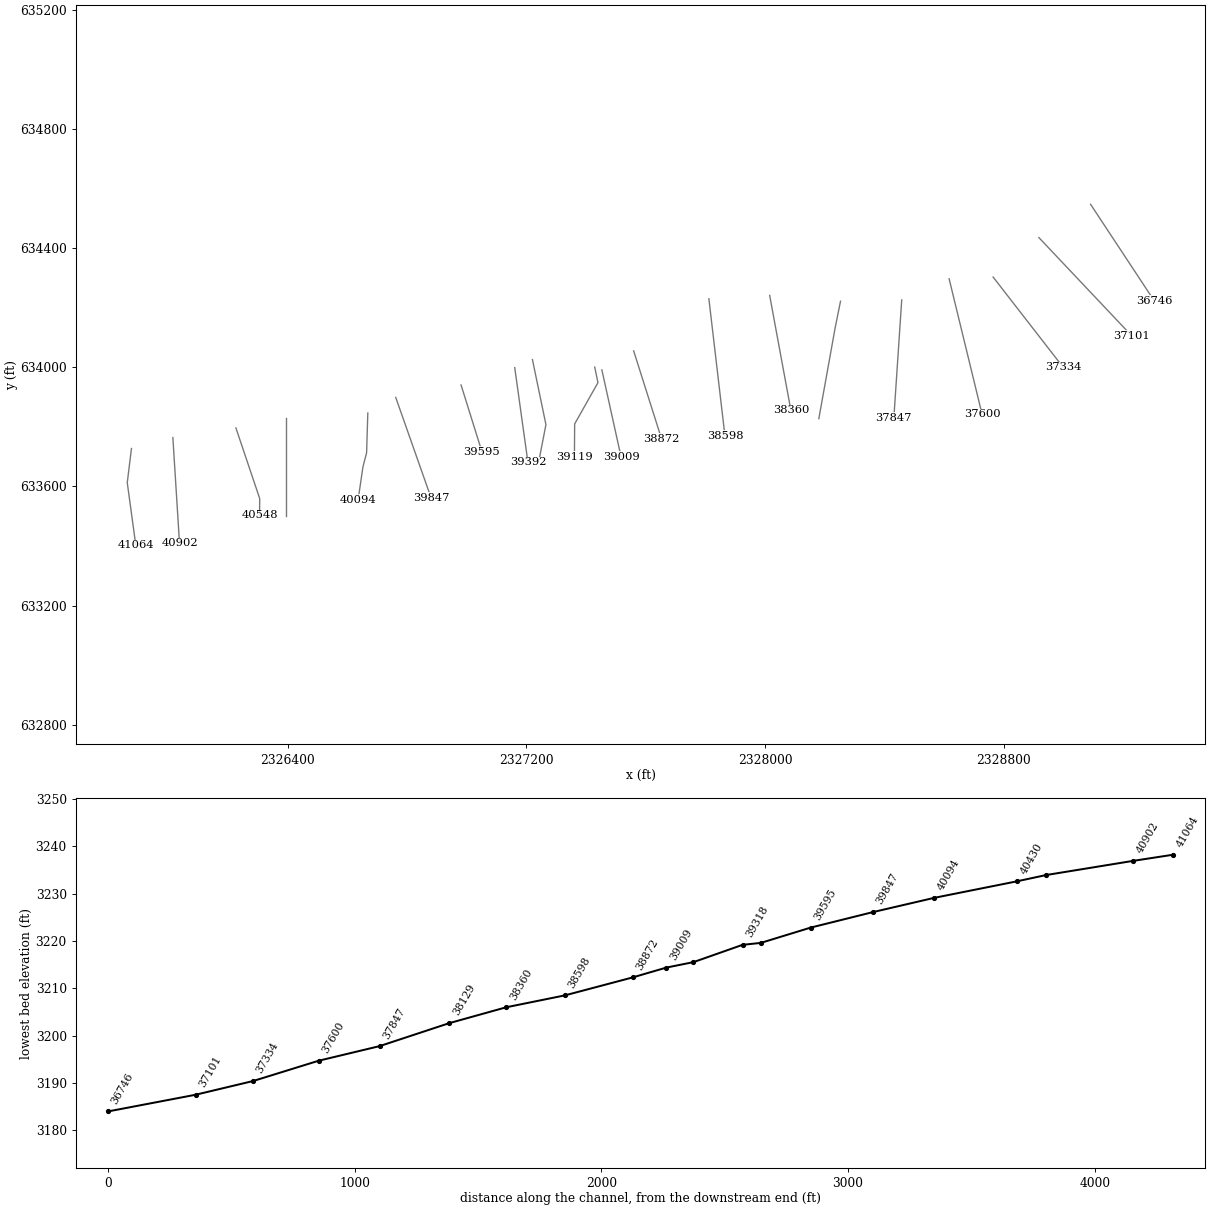
HEC-RAS study EFKGLADYFK.prj: EFKGLADYFK

--- EFKGLADYFK.g01 (geometry) --- (continued)

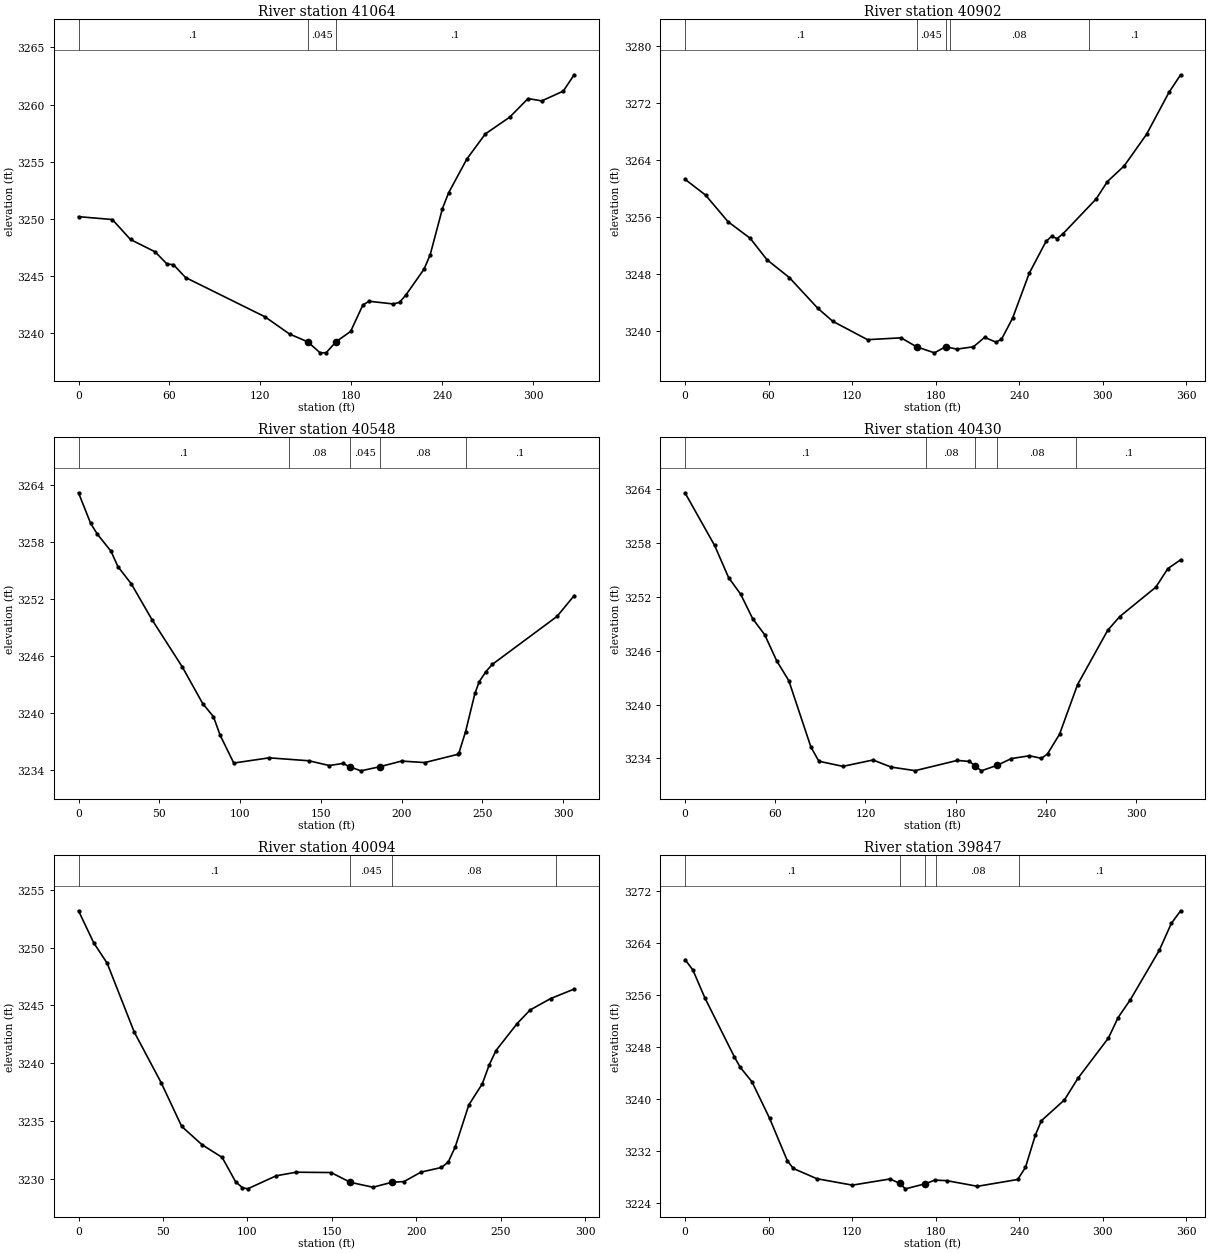
Type RM Length L Ch R = 1 ,41064   ,162.1,162,160.5
XS GIS Cut Line= 3
 2325875.6968304 633727.269406012325861.57155798633612.585581818
2325890.16100439633403.107965972
#Sta/Elev= 30
       0 3250.18    22.3 3249.93    34.3 3248.18    50.5  3247.1    58.5 3246.02
    62.6 3245.98    70.6 3244.85     123 3241.41   139.2  3239.9   151.3 3239.21
   159.4 3238.25   163.4 3238.26  169.993239.234   179.5 3240.12   187.6 3242.44
   191.7 3242.77   207.8 3242.53   211.8 3242.68   215.9  3243.3     228 3245.59
     232 3246.84   240.1 3250.89   244.1 3252.25   256.2 3255.23   268.4 3257.43
   284.5  3258.9   296.6 3260.53   305.6 3260.32   319.8 3261.18     327 3262.61
#Mann= 3 ,-1,0
       0      .1       0   151.3    .045       0  169.99      .1       0
Bank Sta=151.3,169.99
XS Rating Curve= 0 ,0
Exp/Cntr=0.3,0.1

Type RM Length L Ch R = 1 ,40902   ,350.1,354.7,351.5
XS GIS Cut Line= 2
 2326014.4515576633763.9937821142326036.83361494633408.678621754
#Sta/Elev= 30
       0 3261.34    14.8 3259.11    30.9 3255.38    46.9 3253.03    58.9 3250.03
      75 3247.52    95.3 3243.23   106.1 3241.39   131.1  3238.8   155.2 3239.06
   166.4 3237.79   179.2 3236.95   187.2 3237.81   195.2 3237.47   207.2  3237.8
   215.2 3239.12   223.3 3238.46   227.3 3238.84   235.3 3241.82   247.3 3248.15
   259.3  3252.6   263.3 3253.32   267.3 3253.01   271.4 3253.66   295.4 3258.59
   303.4 3261.02   315.4  3263.2   331.5 3267.65   347.6 3273.54     356 3276.02
#Mann= 5 ,-1,0
       0      .1       0   166.4    .045       0   187.2      .1       0
     190     .08       0     290      .1       0
Bank Sta=166.4,187.2
XS Rating Curve= 0 ,0
Exp/Cntr(USF)=0,0
Exp/Cntr=0.3,0.1

Type RM Length L Ch R = 1 ,40548   ,119.7,117.6,113.1
XS GIS Cut Line= 3
2326225.85961454 633796.293068572326305.71300986633559.163324152
2326305.06016801633502.623354025
#Sta/Elev= 30
       0 3263.23     7.5 3260.01    11.7 3258.86    20.1 3257.08    24.4 3255.45
    32.7 3253.63    45.5 3249.86    64.3 3244.87    76.9 3241.02    83.5 3239.65
    87.7 3237.68    96.1 3234.76     118 3235.31   142.6    3235   155.2  3234.5
   163.7 3234.72   167.9 3234.36   174.8 3233.94   186.83234.386     200 3234.97
   214.3 3234.81   234.8 3235.68   235.4 3235.78   239.6 3238.08   245.4 3242.12
   248.1 3243.35   252.2  3244.4   256.2 3245.16   296.2 3250.21   306.8  3252.4
#Mann= 5 ,-1,0
       0      .1       0     130     .08       0   167.9    .045       0
   186.8     .08       0     240      .1       0
Bank Sta=167.9,186.8
XS Rating Curve= 0 ,0
Exp/Cntr=0.3,0.1

Type RM Length L Ch R = 1 ,40430   ,333.9,336,324.3
XS GIS Cut Line= 2
2326394.92527453633830.1555607422326394.92527453633500.641938711
#Sta/Elev= 30
       0 3263.61    19.7 3257.74      29 3254.16      37 3252.31      45 3249.58
      53 3247.79      61 3244.87      69 3242.68    83.7 3235.28      89 3233.69
     105 3233.12     125 3233.83     137 3233.04     153 3232.64     181 3233.78
     189 3233.67     193 3233.17     197 3232.62   207.7 3233.25     217 3233.99
     229  3234.3     237 3234.01     241 3234.51     249  3236.7     261 3242.24
     281 3248.28     289 3249.81     313 3253.09     321 3255.16   329.5 3256.14
#Mann= 5 ,-1,0
       0      .1       0     160     .08       0     193    .045       0
   207.7     .08       0     260      .1       0
Bank Sta=193,207.7
XS Rating Curve= 0 ,0
Exp/Cntr(USF)=0,0
Exp/Cntr=0.3,0.1

Type RM Length L Ch R = 1 ,40094   ,242,247.4,245.9
XS GIS Cut Line= 4
2326668.11833057633846.2031276522326664.04366274633713.059253399
      2326651.66633665.0431699562326635.68523987633555.436102284
#Sta/Elev= 30
       0  3253.2       9 3250.43      17 3248.65      33  3242.7      49  3238.3
    61.1 3234.53    73.1 3232.95    85.1 3231.84    93.1 3229.72    97.1 3229.22
   100.2 3229.12   117.1 3230.25   128.9 3230.56   149.6 3230.53   161.1 3229.68
   174.4 3229.26   185.7 3229.69   192.8 3229.75   202.9 3230.57     215 3230.97
     219 3231.44   223.1 3232.73   231.2 3236.39   239.2 3238.22   243.3 3239.86
   247.3  3241.1   259.8 3243.43   267.5 3244.61   279.7  3245.6   293.6 3246.42
#Mann= 4 ,-1,0
       0      .1       0   161.1    .045       0   185.7     .08       0
  282.79      .1       0
Bank Sta=161.1,185.7
XS Rating Curve= 0 ,0
Exp/Cntr=0.3,0.1

Type RM Length L Ch R = 1 ,39847   ,249.6,252.1,248.9
XS GIS Cut Line= 2
2326761.74232547633898.5451804092326879.86985035633562.814320226
#Sta/Elev= 30
       0  3261.4     5.7 3259.78    14.2 3255.54    35.4 3246.45    39.6 3244.84
    48.1 3242.59    60.8 3236.95    73.5 3230.44    77.8 3229.25    94.7 3227.68
   120.2 3226.69   147.3 3227.64   154.1 3226.96   158.3 3226.12   172.4 3226.89
   179.5 3227.46     188 3227.38     210 3226.51   238.9 3227.56   244.5 3229.42
   251.6  3234.4   255.9  3236.6   272.5 3239.81   282.1 3243.11   304.1 3249.34
     311 3252.47   319.8 3255.22   340.7 3262.87   349.2 3266.95   355.9  3268.9
#Mann= 5 ,-1,0
       0      .1       0   154.1    .045       0   172.4      .1       0
     180     .08       0     240      .1       0
Bank Sta=154.1,172.4
XS Rating Curve= 0 ,0
Exp/Cntr(USF)=0,0
Exp/Cntr=0.3,0.1

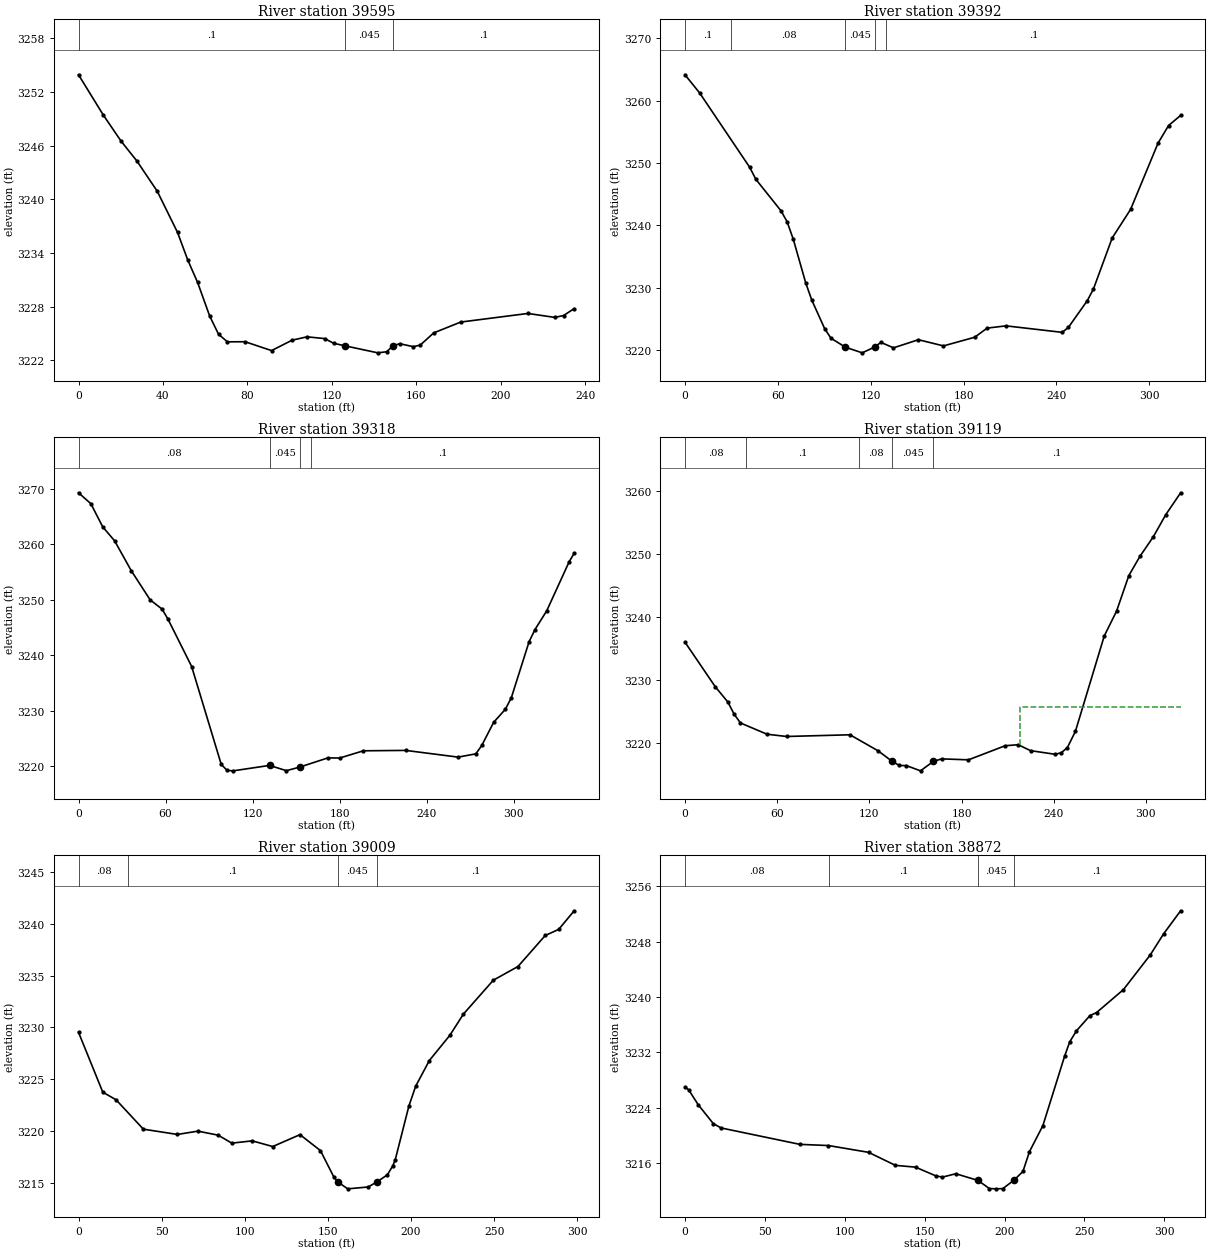
Type RM Length L Ch R = 1 ,39595   ,197.1,202.8,198.8
XS GIS Cut Line= 2
2326980.75766866633940.4470871592327050.70302469633716.386992215
#Sta/Elev= 30
       0 3253.92    11.8  3249.4    20.2 3246.49    27.7 3244.27    37.3  3240.9
    46.9  3236.3    51.7 3233.24    56.4 3230.71    62.1 3226.97    66.3 3224.93
    70.5 3224.08    78.9 3224.09    91.4  3223.1   101.1 3224.26   108.2 3224.64
   116.6 3224.44   120.8 3223.92   126.23223.633   141.7 3222.85   145.9 3222.97
     149 3223.65   152.1 3223.87   158.5 3223.54   161.8 3223.71   168.2 3225.08
     181 3226.29   212.8 3227.25   225.5 3226.81   229.7 3227.02   234.7 3227.79
#Mann= 3 ,-1,0
       0      .1       0   126.2    .045       0     149      .1       0
Bank Sta=126.2,149
XS Rating Curve= 0 ,0
Exp/Cntr=0.3,0.1

Type RM Length L Ch R = 1 ,39392   ,72.5,73.9,74.3
XS GIS Cut Line= 2
2327160.70961225633998.5572777042327204.86884541633681.413694126
#Sta/Elev= 30
       0 3264.13     9.5 3261.21    41.8 3249.32    45.8 3247.39      62 3242.36
      66 3240.59      70 3237.77    78.1 3230.72      82 3228.01    90.2  3223.5
    94.3 3221.95   103.6 3220.52   114.5 3219.61   122.5 3220.54   126.6 3221.28
   134.7 3220.41   150.8 3221.71     167 3220.72   187.2 3222.11   195.2 3223.57
   207.4 3223.93   243.7 3222.89   247.7 3223.69   259.9 3227.96   263.9 3229.85
     276 3238.01   287.9 3242.59   305.6 3253.18   312.4    3256   320.2 3257.63
#Mann= 5 ,-1,0
       0      .1       0      30     .08       0   103.6    .045       0
   122.5     .08       0     130      .1       0
Bank Sta=103.6,122.5
XS Rating Curve= 0 ,0
Exp/Cntr(USF)=0,0
Exp/Cntr=0.3,0.1

Type RM Length L Ch R = 1 ,39318   ,203.9,198.9,189
XS GIS Cut Line= 3
2327220.07780506634025.5364603612327265.31270695633807.387498021
  2327242.695256633690.652267337
#Sta/Elev= 30
       0 3269.28     8.5 3267.32    16.7 3263.14    24.9 3260.62    36.4 3255.23
    49.4 3249.99    57.6 3248.33    61.6 3246.56      78 3237.99    98.4 3220.35
   102.5 3219.27   106.6  3219.2   131.73220.177   143.3 3219.23   152.43219.867
   171.9 3221.53   180.1 3221.51   196.4 3222.81   225.6 3222.88   261.7 3221.67
   273.9 3222.26     278 3223.77   286.2 3227.94   294.3  3230.3   298.4 3232.38
   310.6 3242.44   314.7 3244.65   322.8 3248.03   338.3 3256.89   341.7 3258.38
#Mann= 4 ,-1,0
       0     .08       0   131.7    .045       0   152.4     .08       0
     160      .1       0
Bank Sta=131.7,152.4
XS Rating Curve= 0 ,0
Exp/Cntr(USF)=0,0
Exp/Cntr=0.3,0.1

Type RM Length L Ch R = 1 ,39119   ,96.9,110.3,114.7
XS GIS Cut Line= 4
2327428.89804877634000.5163100382327439.68595778633948.199370033
2327361.61927226633809.5762835962327360.82447654633699.528478186
#Sta/Elev= 30
       0    3236    19.7 3228.92    27.9 3226.49      32 3224.55    36.1 3223.16
    53.4 3221.37    66.1 3221.01   107.4 3221.28   125.7 3218.73   134.53217.114
   139.5  3216.4   144.1 3216.38   153.3 3215.55   161.73217.059   167.1 3217.45
   184.5  3217.3   208.4 3219.54   216.9  3219.7   224.9 3218.76   240.9 3218.18
   244.9 3218.42   248.9 3219.25   254.1 3221.81   272.9 3236.99   280.9 3240.93
   288.9 3246.59   296.1 3249.63   304.9 3252.78   312.9 3256.25   322.6 3259.74
#Mann= 5 ,-1,0
       0     .08       0      40      .1       0  113.42     .08       0
   134.5    .045       0   161.7      .1       0
#XS Ineff= 2 , 0
                          217.83          3225.7
Permanent Ineff=
       F       F
Bank Sta=134.5,161.7
XS Rating Curve= 0 ,0
Exp/Cntr=0.3,0.1

Type RM Length L Ch R = 1 ,39009   ,135.1,136.7,137.3
XS GIS Cut Line= 2
2327452.81867123633991.2454863472327517.02304811 633700.13700483
#Sta/Elev= 30
       0 3229.53    14.6 3223.74    22.6    3223      39 3220.16    59.5 3219.65
    71.8 3219.97      84 3219.58    92.2 3218.81   104.5 3219.03   116.8 3218.48
   133.2 3219.63   145.5 3218.09   153.7 3215.49     156 3215.05   161.9 3214.39
   174.2 3214.57  179.423215.053   185.8 3215.75   189.1 3216.64   190.5 3217.21
   198.7  3222.4   202.8 3224.32     211  3226.8   223.3 3229.23   231.5 3231.29
   249.5 3234.57   264.3 3235.89   280.7 3238.89   288.8 3239.48   298.1 3241.28
#Mann= 4 ,-1,0
       0     .08       0      30      .1       0     156    .045       0
  179.42      .1       0
Bank Sta=156,179.42
XS Rating Curve= 0 ,0
Exp/Cntr(USF)=0,0
Exp/Cntr=0.3,0.1

Type RM Length L Ch R = 1 ,38872   ,273.3,273.6,270.1
XS GIS Cut Line= 2
2327559.48086924634054.7599380852327653.15196988633759.026891795
#Sta/Elev= 30
       0    3227     2.3 3226.61     8.2 3224.48    17.7 3221.73    22.6  3221.1
    71.9 3218.73    89.8 3218.56   114.9 3217.58   131.7  3215.7   144.3 3215.44
   156.9 3214.19   161.1    3214   169.5 3214.49   183.4 3213.52   190.5 3212.35
   194.7 3212.31   198.9 3212.34   205.8 3213.54   211.5 3214.82   215.6 3217.68
     224 3221.44   237.6 3231.47   240.8 3233.53     245 3235.12   253.4 3237.31
   257.6 3237.76   274.4 3241.07   291.2 3246.08   299.6 3249.14   310.2 3252.45
#Mann= 4 ,-1,0
       0     .08       0      90      .1       0   183.4    .045       0
   205.8      .1       0
Bank Sta=183.4,205.8
XS Rating Curve= 0 ,0
Exp/Cntr(USF)=0,0
Exp/Cntr=0.3,0.1

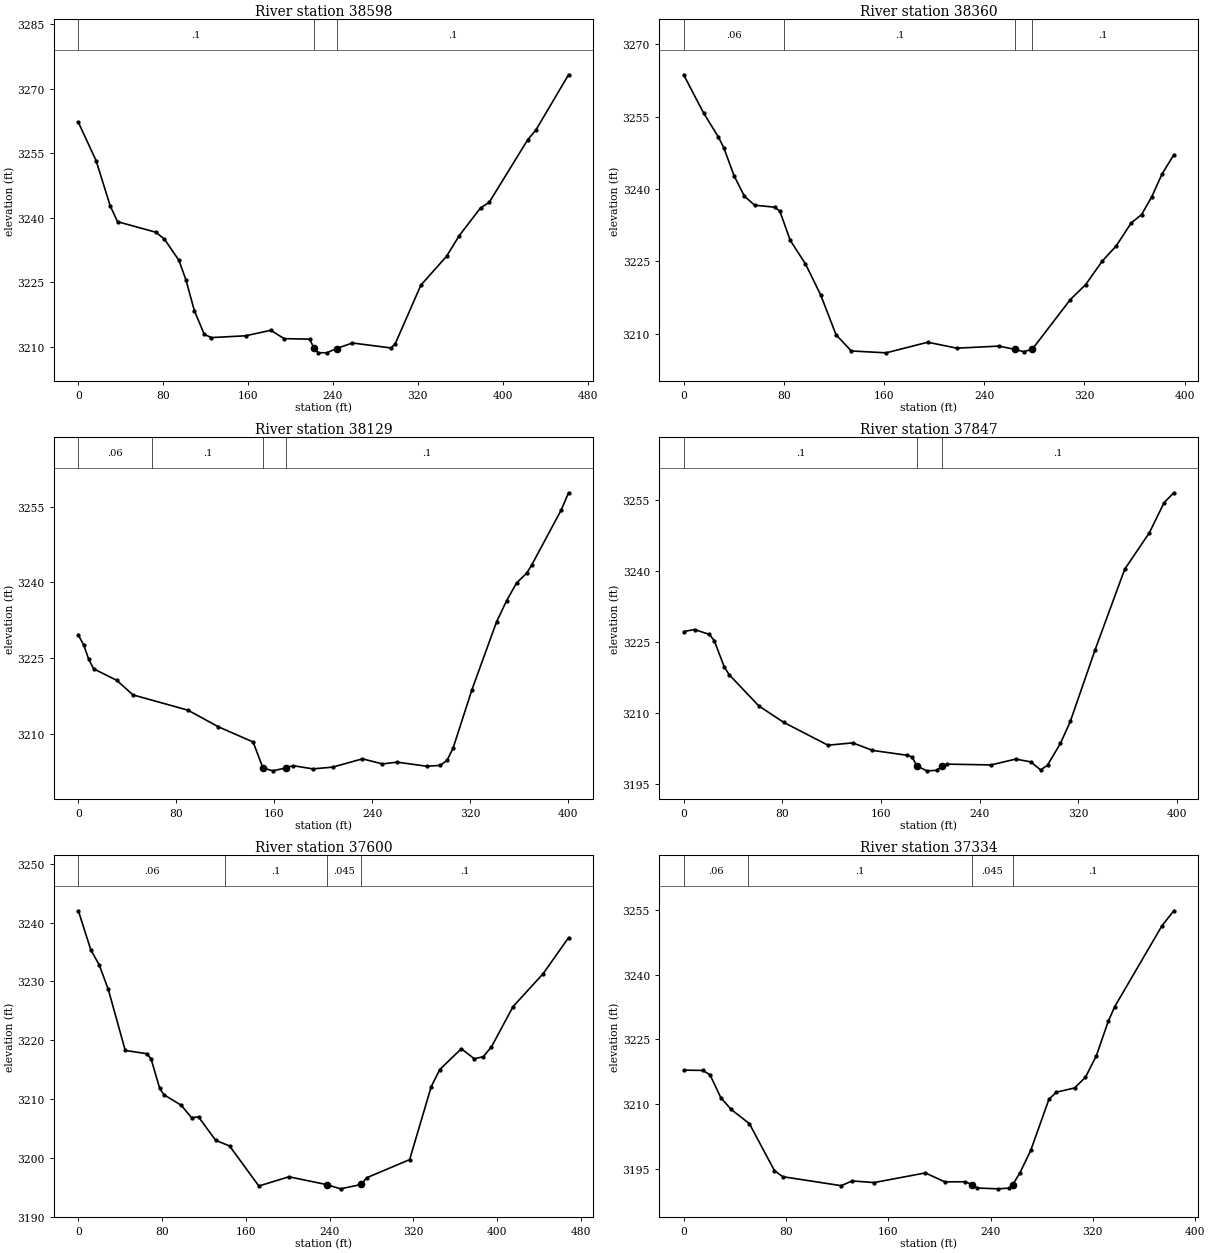
Type RM Length L Ch R = 1 ,38598   ,239.3,238.4,237.4
XS GIS Cut Line= 2
2327811.62705565634229.8395766322327865.35379597633770.879669374
#Sta/Elev= 30
       0 3262.18    16.8 3253.22    29.9 3242.82    36.9 3239.06    73.2 3236.59
    81.2 3234.97    94.8 3230.06   101.3  3225.6   109.4 3218.33   118.7 3212.82
   125.5 3212.08   157.7  3212.5   181.4 3213.78     194 3211.83   218.1 3211.72
   222.2 3209.57   226.2 3208.57   234.2 3208.53   243.43209.537   258.4 3210.82
   294.7 3209.67   298.7 3210.64   322.9 3224.28   347.2 3231.03   359.1 3235.82
   379.2 3242.28   387.3 3243.55   423.5 3258.08   431.6  3260.5   462.1 3273.25
#Mann= 3 ,-1,0
       0      .1       0   222.2    .045       0   243.4      .1       0
Bank Sta=222.2,243.4
XS Rating Curve= 0 ,0
Exp/Cntr=0.3,0.1

Type RM Length L Ch R = 1 ,38360   ,232.2,230.6,222.2
XS GIS Cut Line= 2
 2328015.4852403 634240.831022032328086.52328841633855.903924183
#Sta/Elev= 30
       0 3263.71    15.9 3255.79    27.8 3250.78    32.2 3248.48    40.3 3242.73
    48.5 3238.53    56.6 3236.65    72.9 3236.23    76.9 3235.36    85.1 3229.36
    97.3 3224.45   109.5 3217.98   121.7 3209.76   133.9  3206.4   161.7 3206.01
   194.9 3208.21   218.2 3206.98   251.8 3207.41   264.7 3206.71   271.6 3206.25
   278.4 3206.77   308.8 3217.07     321 3220.17   334.4  3225.1   345.4 3228.19
   357.4 3232.97   365.7 3234.71   373.9 3238.45     382 3243.12   391.4  3247.1
#Mann= 4 ,-1,0
       0     .06       0      80      .1       0   264.7    .045       0
   278.4      .1       0
Bank Sta=264.7,278.4
XS Rating Curve= 0 ,0
Exp/Cntr(USF)=0,0
Exp/Cntr=0.3,0.1

Type RM Length L Ch R = 1 ,38129   ,280.2,282.8,279.6
XS GIS Cut Line= 3
2328252.99100442 634221.356801062328235.28069533634133.562955778
2328180.29668412633827.382363363
#Sta/Elev= 30
       0 3229.54     4.3 3227.62     8.3 3224.86    12.4 3222.87    31.4 3220.58
    44.6  3217.7    89.6 3214.67   114.3  3211.4   142.8 3208.37   150.9 3203.22
     159 3202.66   169.63203.246   175.3 3203.69   191.6 3203.05   207.8 3203.39
   232.2 3205.04   248.4 3204.03   260.6 3204.38     285 3203.56   295.8 3203.75
   301.3 3204.74   306.2 3207.12   321.6 3218.68   341.9 3232.23     350 3236.35
   358.2 3239.89   366.3 3241.77   370.4 3243.36   394.8 3254.39   400.6 3257.72
#Mann= 4 ,-1,0
       0     .06       0      60      .1       0   150.9    .045       0
   169.6      .1       0
Bank Sta=150.9,169.6
XS Rating Curve= 0 ,0
Exp/Cntr=0.3,0.1

Type RM Length L Ch R = 1 ,37847   ,242.4,246.7,249.8
XS GIS Cut Line= 2
2328458.23400521634225.9625933582328431.80124313  633829.4711621
#Sta/Elev= 30
       0 3227.23     8.8 3227.66    20.8 3226.64    24.8 3225.32    32.9 3219.77
    36.9 3218.13    60.9 3211.53      81 3208.06     117 3203.22   137.1 3203.71
   153.1 3202.12   181.2 3201.09   185.2 3200.73   189.2 3198.81   197.2  3197.8
   205.2  3197.9   209.4 3198.77   213.3 3199.22   249.3 3199.05   269.2 3200.28
   281.4  3199.7   289.4 3197.99     295 3198.99   305.5 3203.61   313.5 3208.25
   333.5 3223.31   357.6 3240.41   377.6 3248.12   389.6  3254.5   397.4 3256.56
#Mann= 3 ,-1,0
       0      .1       0   189.2    .045       0   209.4      .1       0
Bank Sta=189.2,209.4
XS Rating Curve= 0 ,0
Exp/Cntr(USF)=0,0
Exp/Cntr=0.3,0.1

Type RM Length L Ch R = 1 ,37600   ,252.5,265.7,266.9
XS GIS Cut Line= 2
2328617.11223241634296.6890523562328727.75233387633841.676980382
#Sta/Elev= 30
       0 3242.02    11.8 3235.42    20.1 3232.74    28.6 3228.64    44.8 3218.26
    65.4 3217.71    69.5 3216.81    77.7 3211.81    81.8 3210.72    98.3 3208.94
   108.1 3206.83   114.8 3206.96   131.2 3202.97   144.5 3202.01   172.4  3195.2
   201.2 3196.77   237.2 3195.44   250.5 3194.72   270.4 3195.47   275.3 3196.59
   316.5 3199.69   337.1 3212.09   345.3 3215.02   365.9 3218.55   378.2 3216.85
   386.8 3217.19   394.7 3218.88   415.3 3225.72   444.1 3231.33   468.3 3237.43
#Mann= 4 ,-1,0
       0     .06       0     140      .1       0   237.2    .045       0
   270.4      .1       0
Bank Sta=237.2,270.4
XS Rating Curve= 0 ,0
Exp/Cntr=0.3,0.1

Type RM Length L Ch R = 1 ,37334   ,229.7,233.2,233.2
XS GIS Cut Line= 2
2328764.65181541 634302.51809837 2328999.6097006633999.642699492
#Sta/Elev= 30
       0 3217.89    14.9 3217.82    20.6 3216.82    29.1  3211.5    37.1 3208.81
    51.4 3205.51      71 3194.64    77.5 3193.24   123.2 3191.16   131.8 3192.26
   148.9 3191.88     189 3194.11   204.2 3192.05   220.1 3192.06   225.8  3191.4
   229.5 3190.62   245.8 3190.43   254.3 3190.59   257.2 3191.34   262.9 3194.09
   271.4 3199.31   285.7 3211.18   291.4 3212.78   305.7 3213.77   314.2 3216.23
   322.8 3221.27     332 3229.15     337 3232.52   374.1 3251.31   383.3 3254.75
#Mann= 4 ,-1,0
       0     .06       0      50      .1       0   225.8    .045       0
   257.2      .1       0
Bank Sta=225.8,257.2
XS Rating Curve= 0 ,0
Exp/Cntr(USF)=0,0
Exp/Cntr=0.3,0.1

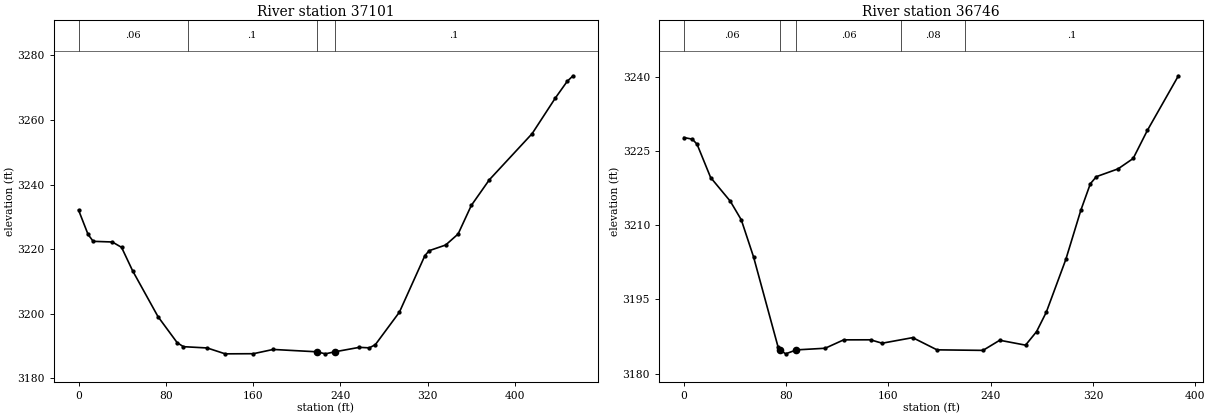
Type RM Length L Ch R = 1 ,37101   ,353.5,355.4,351.3
XS GIS Cut Line= 2
2328918.18363014634434.9233682372329229.39664813634105.322435337
#Sta/Elev= 30
       0 3232.06     8.7 3224.52    13.4 3222.39    30.9 3222.19    39.4 3220.53
    49.5 3213.29    72.8 3199.06    90.4 3190.98    96.1 3189.75   117.9 3189.35
   134.4 3187.53   160.2 3187.57   178.4 3188.89   218.5 3188.16   226.2 3187.53
   234.7 3188.15   257.3 3189.54   266.5 3189.39     272 3190.36   294.1 3200.45
   317.5    3218   321.5 3219.51   336.5 3221.25   347.9 3224.66     360 3233.51
   376.5 3241.45   415.8 3255.78     437 3266.78     448 3272.01   453.3 3273.69
#Mann= 4 ,-1,0
       0     .06       0     100      .1       0   218.5    .045       0
   234.7      .1       0
Bank Sta=218.5,234.7
XS Rating Curve= 0 ,0
Exp/Cntr=0.3,0.1

Type RM Length L Ch R = 1 ,36746   ,149.9,150.2,150
XS GIS Cut Line= 2
 2329091.3901245 634546.654025952329304.32070796634223.586933814
#Sta/Elev= 30
       0 3227.78     6.6 3227.45    10.3 3226.42    20.9 3219.69    36.3 3214.89
    44.9 3211.12    54.5 3203.61    73.6 3185.46    75.23184.815    79.6    3184
      88  3184.8   110.5 3185.13     125 3186.83     146 3186.84   155.1 3186.15
     179 3187.28     198 3184.81     234  3184.7   247.1 3186.75   267.3 3185.76
   275.9 3188.49   283.5 3192.41   298.8  3203.1   310.6  3213.1     318 3218.43
   322.7 3219.86   339.7 3221.44   351.5 3223.54   362.6 3229.22   386.9 3240.28
#Mann= 5 ,-1,0
       0     .06       0    75.2    .045       0      88     .06       0
     170     .08       0     220      .1       0
Bank Sta=75.2,88
XS Rating Curve= 0 ,0
Exp/Cntr(USF)=0,0
Exp/Cntr=0.3,0.1