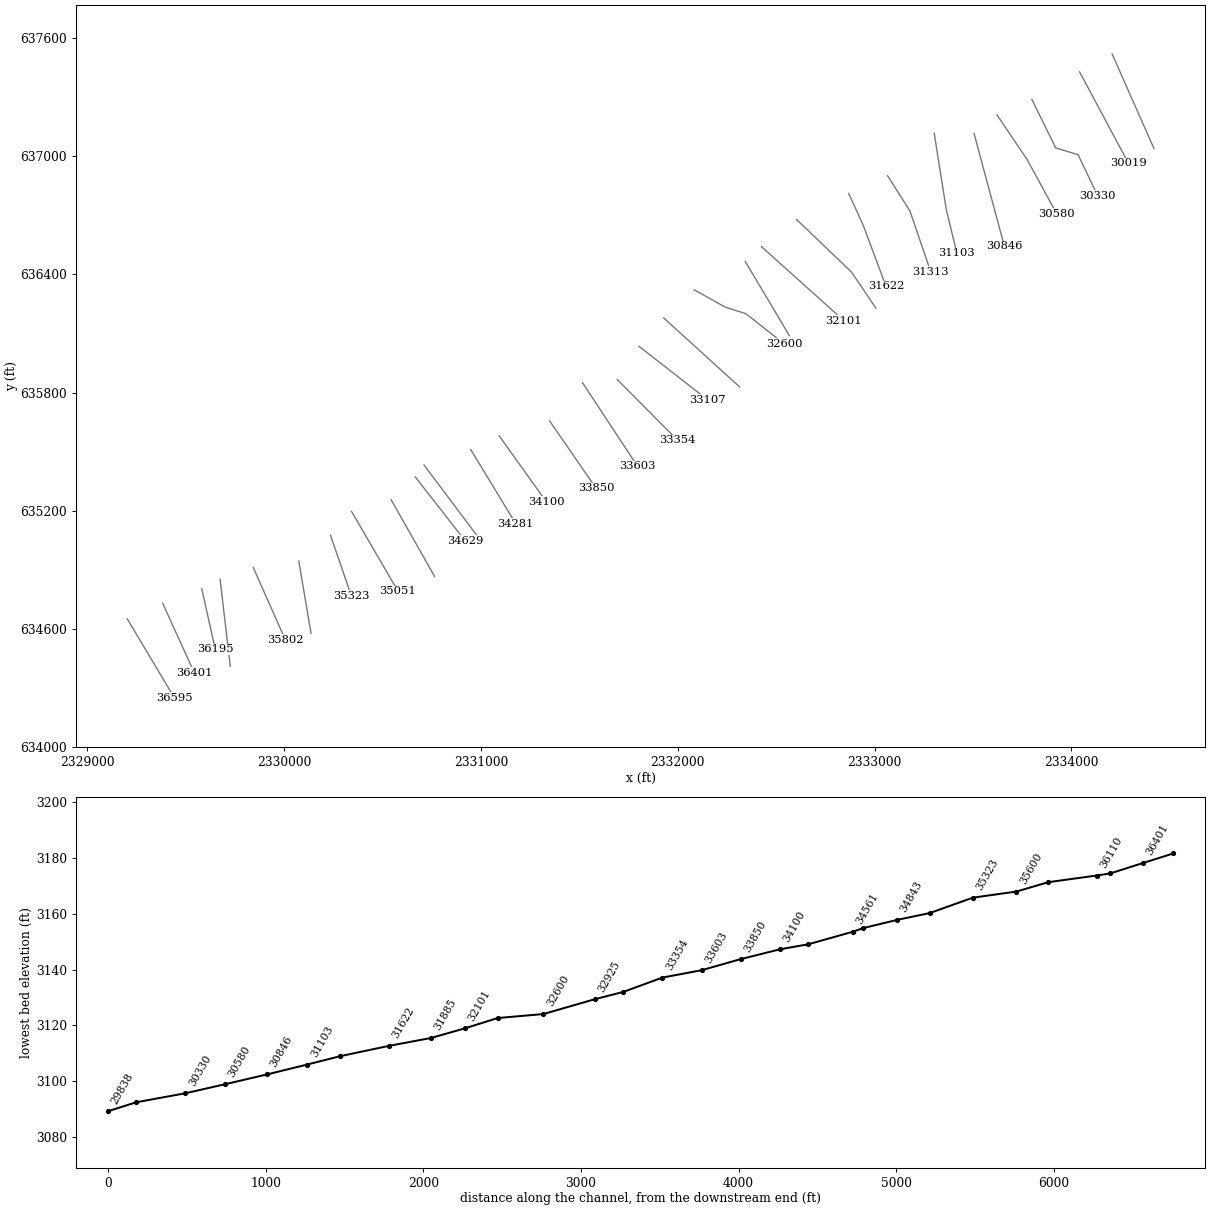
HEC-RAS study EFKGLADYFK.prj: EFKGLADYFK

--- EFKGLADYFK.g01 (geometry) --- (continued)

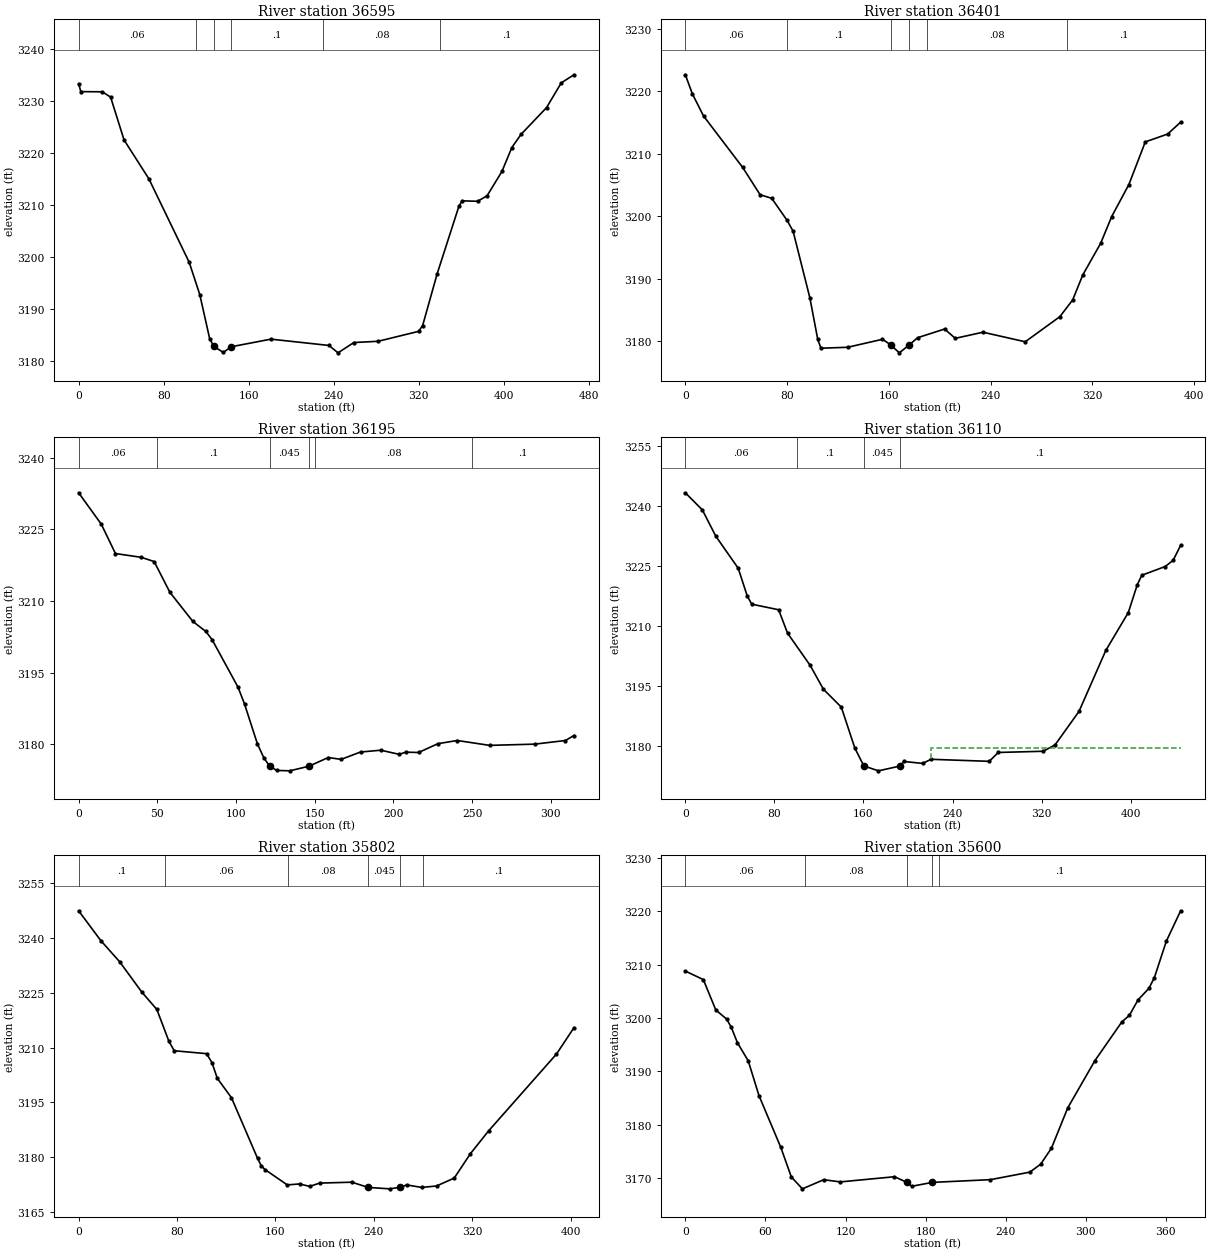
Type RM Length L Ch R = 1 ,36595   ,196.5,194.6,193.5
XS GIS Cut Line= 2
2329203.39208184634651.0077201052329442.30638534634251.034805423
#Sta/Elev= 30
       0 3233.35     2.1 3231.84    22.3 3231.81    30.1 3230.78    42.7 3222.57
    66.1 3215.08     104 3199.05     114 3192.81   123.3 3184.33   127.3 3182.86
   136.1 3181.72   143.63182.811   180.9 3184.27   235.5 3183.06     244 3181.64
   258.9 3183.62   281.7 3183.86   319.8 3185.77   323.6 3186.89   337.3 3196.87
   357.8 3209.87   360.9 3210.85   375.3 3210.77   384.2 3211.82   398.2 3216.51
   407.5  3221.1   416.1 3223.62   440.1 3228.76     454 3233.53   465.9 3235.08
#Mann= 6 ,-1,0
       0     .06       0     110      .1       0   127.3    .045       0
   143.6      .1       0     230     .08       0     340      .1       0
Bank Sta=127.3,143.6
XS Rating Curve= 0 ,0
Exp/Cntr=0.3,0.1

Type RM Length L Ch R = 1 ,36401   ,208.9,206.4,201.7
XS GIS Cut Line= 2
2329383.25187251634730.2148737552329544.78541858634375.942437492
#Sta/Elev= 30
       0 3222.66     5.5 3219.62    14.3 3216.07    45.1 3207.83    58.8 3203.46
    67.9  3202.9      80 3199.36    84.7 3197.64    97.9 3186.97   104.1 3180.32
   106.6 3178.91   127.6 3179.06     155 3180.34   161.5 3179.44   168.2 3178.17
   175.8  3179.4   182.6 3180.59   203.8 3181.98   212.2 3180.49     234 3181.47
   267.2 3179.94   294.4 3183.95   304.5 3186.63   312.5 3190.65   326.5 3195.69
   335.2 3199.98   348.7  3205.1   361.6 3211.92   379.2 3213.18   389.4 3215.08
#Mann= 6 ,-1,0
       0     .06       0      80      .1       0   161.5    .045       0
   175.8      .1       0     190     .08       0     300      .1       0
Bank Sta=161.5,175.8
XS Rating Curve= 0 ,0
Exp/Cntr(USF)=0,0
Exp/Cntr=0.3,0.1

Type RM Length L Ch R = 1 ,36195   ,85.8,84.7,83.8
XS GIS Cut Line= 2
2329581.77744083634804.0145299812329650.35938885634496.854954245
#Sta/Elev= 30
       0 3232.67    14.4  3226.1    23.4 3219.95    39.8 3219.16      48 3218.27
      58 3211.83    72.6 3205.73    80.8 3203.64    84.8 3201.93   101.3 3191.96
   105.4 3188.46   113.6 3180.11   117.7 3177.17  121.43 3175.41   125.9 3174.55
   134.1 3174.46   146.4 3175.43   158.6 3177.25   166.8 3176.86   179.1  3178.4
     192 3178.78   203.7 3177.91   207.8 3178.37     216  3178.3   228.3 3180.15
   240.6 3180.81   261.1 3179.79   289.8 3180.05   309.3 3180.81   314.7 3181.85
#Mann= 6 ,-1,0
       0     .06       0      50      .1       0  121.43    .045       0
   146.4      .1       0     150     .08       0     250      .1       0
Bank Sta=121.43,146.4
XS Rating Curve= 0 ,0
Exp/Cntr(USF)=0,0
Exp/Cntr=0.3,0.1

Type RM Length L Ch R = 1 ,36110   ,295.9,308.2,299.8
XS GIS Cut Line= 2
2329674.97845011 634852.365325572329726.65459229 634410.43973183
#Sta/Elev= 30
       0 3243.34    15.3 3239.04    27.4 3232.45    47.5 3224.44    55.6  3217.5
    59.6 3215.45    83.8 3214.05    91.8 3208.19   112.1 3200.14     124 3194.16
   140.1 3189.67   152.2 3179.45   160.3 3174.96   173.4 3173.72   192.5  3174.9
   196.5 3176.06   213.1 3175.58   220.7 3176.61     273  3176.1   281.1 3178.32
   321.4 3178.62   332.1 3180.22   353.6  3188.6   377.7 3203.88   397.9 3213.36
   405.9 3220.29     410 3222.69     431 3224.87   438.2 3226.45   444.9  3230.2
#Mann= 4 ,-1,0
       0     .06       0     100      .1       0   160.3    .045       0
   192.5      .1       0
#XS Ineff= 2 , 0
                          220.66         3179.35
Permanent Ineff=
       F       F
Bank Sta=160.3,192.5
XS Rating Curve= 0 ,0
Exp/Cntr=0.3,0.1

Type RM Length L Ch R = 1 ,35802   ,201.1,201.9,197
XS GIS Cut Line= 2
2329843.35649497634912.2413470612330006.61184179634544.247737424
#Sta/Elev= 30
       0 3247.44    18.1 3239.25    33.3 3233.51    51.3 3225.21    63.6 3220.42
    73.4 3211.71    77.7 3209.13     104 3208.33   108.4 3205.87   112.7 3201.59
   124.2 3196.29   145.4 3179.72   148.4 3177.67   151.5  3176.6   169.6 3172.41
   179.6 3172.67   187.8    3172   195.9  3172.9   222.1 3173.15   235.3 3171.72
   252.8 3171.33   261.5 3171.76   266.7  3172.4   278.8 3171.72   290.9 3172.11
   305.3 3174.27   318.4 3180.93   333.3 3187.22   388.4 3208.22   402.6 3215.43
#Mann= 6 ,-1,0
       0      .1       0      70     .06       0     170     .08       0
   235.3    .045       0   261.5     .08       0     280      .1       0
Bank Sta=235.3,261.5
XS Rating Curve= 0 ,0
Exp/Cntr(USF)=0,0
Exp/Cntr=0.3,0.1

Type RM Length L Ch R = 1 ,35600   ,273.8,276.3,272
XS GIS Cut Line= 2
2330075.01562585634943.6282469832330137.04379806634577.702842802
#Sta/Elev= 30
       0 3208.77    13.5 3207.17    22.8 3201.49    30.9 3199.78    34.4 3198.25
      39 3195.35    47.1 3191.96    55.2 3185.41    71.5 3175.75    79.4 3170.19
    87.7 3167.96   103.7 3169.67   116.1 3169.26   156.7 3170.23   166.2 3169.15
   169.6 3168.44   185.1 3169.17   228.6 3169.68   258.1 3171.09   266.2 3172.57
   274.3 3175.58   286.5 3183.13   306.8 3191.96     327 3199.23   332.7 3200.48
   339.2 3203.38   347.3 3205.53   351.4 3207.53   360.4 3214.39   371.1 3220.07
#Mann= 5 ,-1,0
       0     .06       0      90     .08       0   166.2    .045       0
   185.1     .08       0     190      .1       0
Bank Sta=166.2,185.1
XS Rating Curve= 0 ,0
Exp/Cntr=0.3,0.1

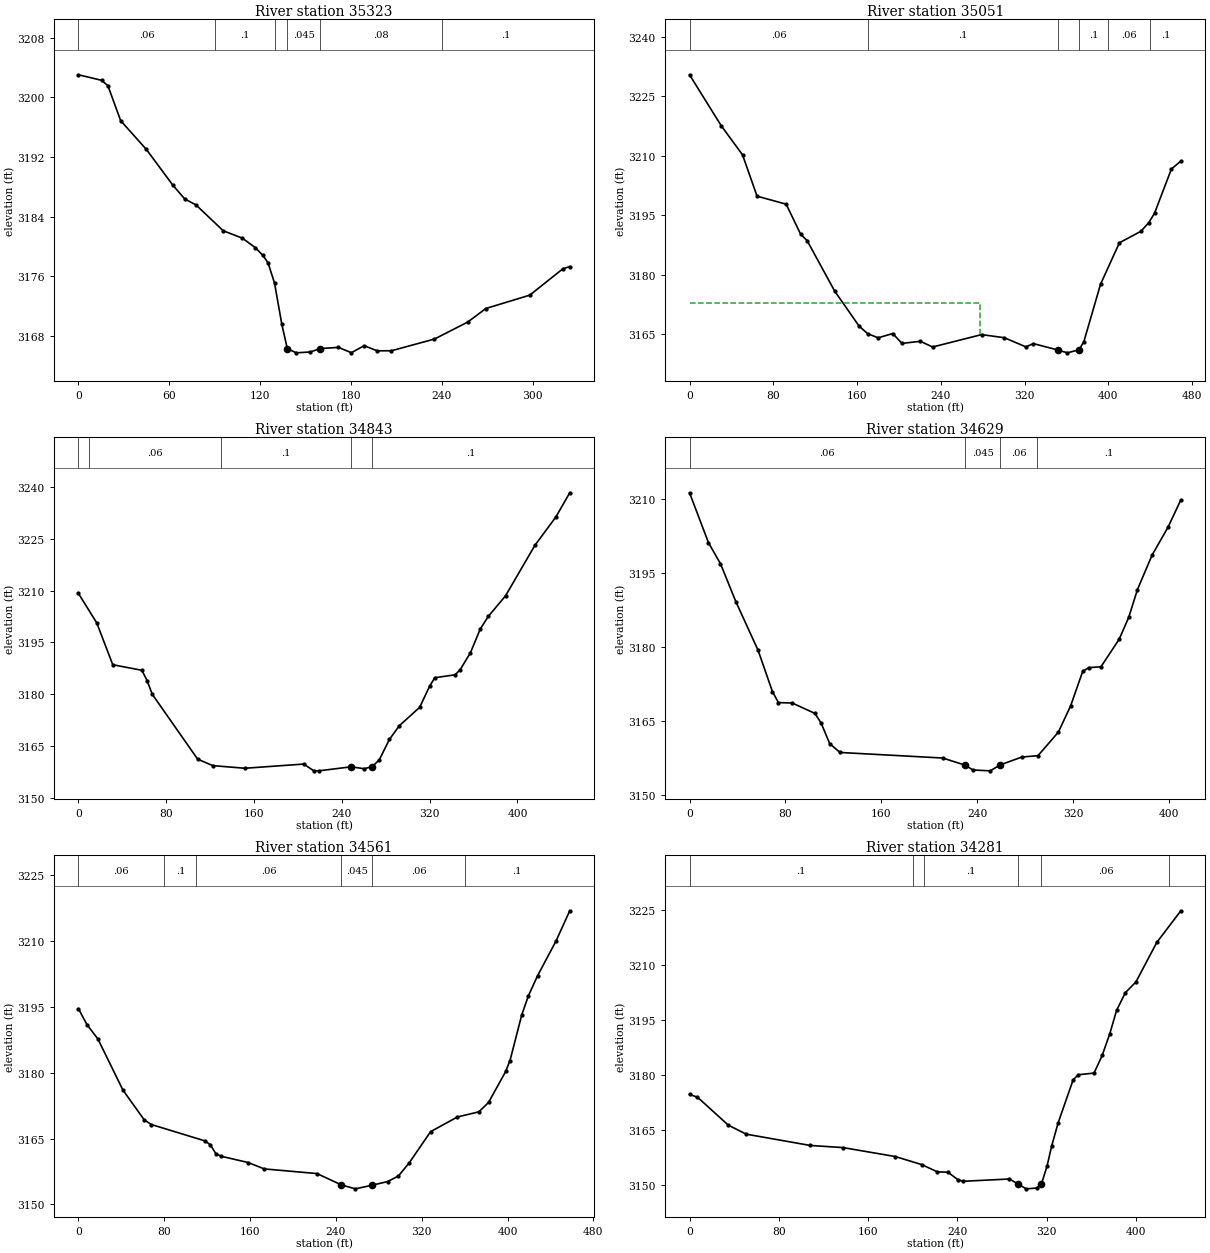
Type RM Length L Ch R = 1 ,35323   ,265.8,272,268.1
XS GIS Cut Line= 2
2330235.88023379635075.601838608 2330341.3342934634768.770427735
#Sta/Elev= 30
       0 3203.03    15.3 3202.29    19.5 3201.55    27.9 3196.88    44.9 3193.02
    62.4 3188.22    70.2 3186.39    77.7 3185.58    95.6 3182.13   108.3 3181.13
   116.8 3179.87   121.8 3178.83   125.2 3177.83   129.5 3175.11   134.3 3169.59
   137.9 3166.35   143.8 3165.77   153.2 3165.89   159.5 3166.34   171.7  3166.5
   180.2 3165.79   188.7 3166.73   197.3 3166.04   206.7 3166.05   235.1 3167.62
   257.1  3169.9     269 3171.71     298  3173.5   319.8 3177.02   324.4 3177.33
#Mann= 6 ,-1,0
       0     .06       0      90      .1       0     130     .08       0
   137.9    .045       0   159.5     .08       0     240      .1       0
Bank Sta=137.9,159.5
XS Rating Curve= 0 ,0
Exp/Cntr(USF)=0,0
Exp/Cntr=0.3,0.1

Type RM Length L Ch R = 1 ,35051   ,209.5,208.6,209.7
XS GIS Cut Line= 2
2330342.39832982635196.929995163 2330578.7903589634791.531753768
#Sta/Elev= 30
       0 3230.37    30.4 3217.48    50.6  3210.2    64.5 3199.77    92.3 3197.75
   106.2 3190.15   112.3 3188.58   138.6 3175.86     162 3167.01   170.3 3165.08
   180.3 3164.07   194.1 3165.15   202.9 3162.66   220.5 3163.19   232.2 3161.75
     279 3164.88   300.7 3164.09   321.2 3161.79   328.5  3162.6   351.6 3161.01
   360.9 3160.28   372.13161.057   376.7 3163.13   392.6 3177.58   410.6 3188.02
   431.1 3190.91   438.7  3193.1   444.2  3195.5   460.3 3206.62   469.3 3208.61
#Mann= 6 ,-1,0
       0     .06       0     170      .1       0   351.6    .045       0
   372.1      .1       0     400     .06       0     440      .1       0
#XS Ineff= 2 , 0
          277.56 3172.96
Permanent Ineff=
       F       F
Bank Sta=351.6,372.1
XS Rating Curve= 0 ,0
Exp/Cntr=0.3,0.1

Type RM Length L Ch R = 1 ,34843   ,211.2,214.2,212.5
XS GIS Cut Line= 2
2330543.93030242 635255.65980254 2330764.7264682634866.255655615
#Sta/Elev= 30
       0 3209.18    16.7 3200.65    31.3 3188.53    57.8 3186.92    62.6 3183.93
    67.2 3180.01   108.6 3161.19   122.4 3159.31   151.7 3158.55   205.2 3159.76
   214.4 3157.82     219  3157.8   248.5 3158.97   260.4 3158.41  267.673159.028
   274.1 3160.98   283.3 3166.89   292.4 3170.88   310.9  3176.2   320.1 3182.41
   324.7 3184.77   343.1 3185.61   347.7 3187.05   357.1 3191.98   366.1 3198.89
   373.5 3202.56   389.1 3208.49   415.8 3223.07   435.1 3231.39   447.6 3238.33
#Mann= 5 ,-1,0
       0      .1       0      10     .06       0     130      .1       0
   248.5    .045       0  267.67      .1       0
Bank Sta=248.5,267.67
XS Rating Curve= 0 ,0
Exp/Cntr(USF)=0,0
Exp/Cntr=0.3,0.1

Type RM Length L Ch R = 1 ,34629   ,67.8,68,67.3
XS GIS Cut Line= 2
2330666.41715594635371.6633362282330918.96782484635048.658618064
#Sta/Elev= 30
       0 3211.31    15.8 3201.19    25.8 3196.92    38.7 3189.19    57.2 3179.34
    69.2 3170.95    74.2 3168.72    85.7 3168.64   104.7 3166.52   109.8 3164.57
     117 3160.38   125.6  3158.6   211.3 3157.47   229.63156.058   236.6 3155.04
   250.9 3154.87   259.5  3156.1   277.3 3157.67   290.8 3157.95   307.8 3162.73
     318 3168.04   328.1 3175.06   333.2 3175.83   343.3 3175.98   358.6 3181.61
   366.5 3186.03   373.8 3191.67     386 3198.66   399.2 3204.28     410 3209.86
#Mann= 4 ,-1,0
       0     .06       0   229.6    .045       0   259.5     .06       0
     290      .1       0
Bank Sta=229.6,259.5
XS Rating Curve= 0 ,0
Exp/Cntr(USF)=0,0
Exp/Cntr=0.3,0.1

Type RM Length L Ch R = 1 ,34561   ,275.8,279.8,268.1
XS GIS Cut Line= 2
 2330711.2616645635431.6127233952330986.43170485635065.471829814
#Sta/Elev= 30
       0 3194.61       8 3190.97    18.1 3187.73    41.5 3176.05    61.4 3169.24
    68.1 3168.19   118.1 3164.45   123.1 3163.54   128.1 3161.55   133.1 3160.96
   158.2 3159.53   173.2 3158.08   222.4 3157.01   245.2 3154.42   258.2 3153.53
   273.8 3154.36   288.3 3155.19   298.3 3156.46   308.3 3159.43   328.3 3166.57
   353.3 3169.92   373.3 3171.09   382.3 3173.22   398.3  3180.3   402.3 3182.78
   413.3 3193.22   419.5 3197.58     428 3202.12   445.2 3210.04     458 3216.94
#Mann= 6 ,-1,0
       0     .06       0      80      .1       0     110     .06       0
   245.2    .045       0   273.8     .06       0     360      .1       0
Bank Sta=245.2,273.8
XS Rating Curve= 0 ,0
Exp/Cntr=0.3,0.1

Type RM Length L Ch R = 1 ,34281   ,180.5,181.4,182.9
XS GIS Cut Line= 2
2330948.00270651635510.7891930262331176.82782377635134.766631906
#Sta/Elev= 30
       0 3174.77     7.1 3174.03    34.7 3166.42    50.8 3163.96   108.1 3160.89
   137.7  3160.3   184.5 3157.86   208.1 3155.67     222 3153.71   231.6 3153.59
   240.7 3151.51   245.4 3151.14   286.6 3151.76   294.23150.414   301.6 3149.08
   310.9 3149.29   315.3 3150.42   320.3 3155.25   324.4 3160.66   330.2 3166.99
   343.7 3178.75   348.4 3180.13   362.4 3180.58   369.7 3185.37   376.5 3191.26
   382.6 3197.62   390.5 3202.47   399.9 3205.36   418.6 3216.12   440.2 3224.75
#Mann= 6 ,-1,0
       0      .1       0     200     .06       0     210      .1       0
   294.2    .045       0   315.3     .06       0     430      .1       0
Bank Sta=294.2,315.3
XS Rating Curve= 0 ,0
Exp/Cntr(USF)=0,0
Exp/Cntr=0.3,0.1

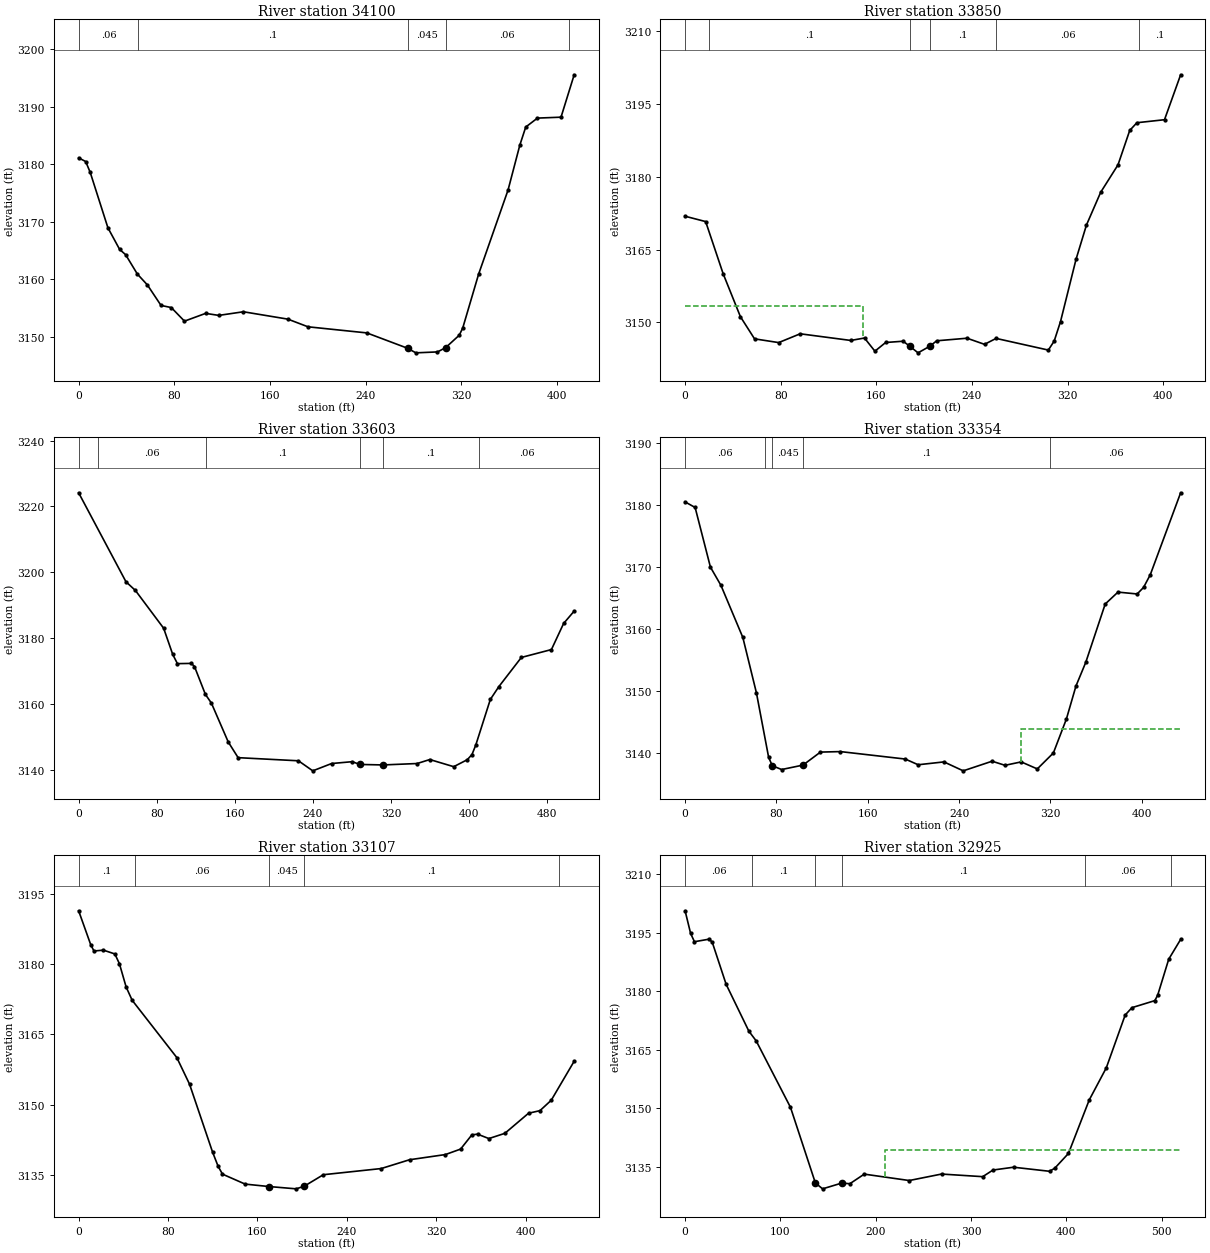
Type RM Length L Ch R = 1 ,34100   ,249.3,249.1,249.4
XS GIS Cut Line= 2
2331091.90021195635581.0909776272331333.27328437 635244.27118693
#Sta/Elev= 30
       0  3181.1     5.9 3180.46     9.7 3178.57    24.5 3168.95    34.3  3165.2
    39.3 3164.29    49.1 3160.93    57.5 3159.04    68.9 3155.48    77.5 3155.11
    88.5 3152.75   106.2  3154.1   117.2 3153.75   137.8 3154.38     175  3153.1
   191.8 3151.77     241 3150.71   275.13148.045     282 3147.25   300.1 3147.41
   306.9 3148.15   318.3 3150.31   321.2 3151.55   334.5 3160.92   359.1 3175.51
     369 3183.34   373.9 3186.45   383.7    3188   403.4 3188.16   414.4 3195.52
#Mann= 5 ,-1,0
       0     .06       0      50      .1       0   275.1    .045       0
   306.9     .06       0     410      .1       0
Bank Sta=275.1,306.9
XS Rating Curve= 0 ,0
Exp/Cntr=0.3,0.1

Type RM Length L Ch R = 1 ,33850   ,245.2,247.1,246.1
XS GIS Cut Line= 2
2331349.45028066635655.3103197192331584.96619082635314.079881693
#Sta/Elev= 30
       0 3171.85    17.2 3170.75    31.8 3160.04    46.3 3151.16    58.1 3146.61
    78.3 3145.84    96.3 3147.65   138.6 3146.28   150.1 3146.78   158.8 3144.07
   167.8 3145.86   182.4 3146.12   187.9 3145.11   194.9 3143.73   204.8  3145.1
   210.5 3146.21   235.9 3146.74   250.5 3145.48   260.2  3146.7   303.9  3144.3
   308.8 3146.15   314.1 3150.17   327.1    3163   335.8 3170.04   347.7 3176.78
   362.2 3182.43     372 3189.51     378  3191.1   401.1 3191.72   414.6 3200.97
#Mann= 6 ,-1,0
       0     .06       0      20      .1       0   187.9    .045       0
   204.8      .1       0     260     .06       0     380      .1       0
#XS Ineff= 2 , 0
          149.24 3153.28
Permanent Ineff=
       F       F
Bank Sta=187.9,204.8
XS Rating Curve= 0 ,0
Exp/Cntr(USF)=0,0
Exp/Cntr=0.3,0.1

Type RM Length L Ch R = 1 ,33603   ,240.1,248.9,247.3
XS GIS Cut Line= 2
2331516.27318694635849.6434277262331795.62865706635425.746961429
#Sta/Elev= 30
       0 3224.16    48.5 3197.15    58.2  3194.5    87.1 3183.04    96.4  3175.1
   101.2  3172.3   115.5 3172.37   118.7 3171.42   129.9 3162.95     136 3160.34
   153.3 3148.51   163.4 3143.76   225.2 3142.81   239.9 3139.76   259.2 3141.98
   280.4 3142.54     288  3141.7   311.9 3141.55   346.8 3141.98   359.8 3143.19
   384.3 3141.02   398.2 3143.14     403 3144.71   406.9 3147.59   421.8 3161.43
   430.5 3165.31   453.6 3174.18   484.4 3176.57   496.9  3184.5   507.7 3188.25
#Mann= 6 ,-1,0
       0      .1       0      20     .06       0     130      .1       0
     288    .045       0   311.9      .1       0     410     .06       0
Bank Sta=288,311.9
XS Rating Curve= 0 ,0
Exp/Cntr=0.3,0.1

Type RM Length L Ch R = 1 ,33354   ,242.6,246.9,249
XS GIS Cut Line= 2
2331692.50719444635865.9294415242331998.79682509 635558.15296801
#Sta/Elev= 30
       0 3180.44     8.8 3179.54    22.2 3169.93    31.4    3167    50.6  3158.6
    62.5 3149.68    73.2 3139.29    76.43137.945    84.6 3137.33   103.33138.045
   118.6 3140.14   136.1 3140.22   192.9 3139.02   204.2  3138.1   226.8 3138.56
   243.7 3137.12     269 3138.67   280.3 3138.01   294.5 3138.56   308.6 3137.43
   322.7    3140   334.1 3145.47   342.5 3150.79   351.1 3154.61   368.1 3163.99
   379.3 3165.91   396.1 3165.61   401.7 3166.66   407.6 3168.71   434.2 3181.91
#Mann= 5 ,-1,0
       0     .06       0      70      .1       0    76.4    .045       0
   103.3      .1       0     320     .06       0
#XS Ineff= 2 , 0
                          294.52         3143.94
Permanent Ineff=
       F       F
Bank Sta=76.4,103.3
XS Rating Curve= 0 ,0
Exp/Cntr(USF)=0,0
Exp/Cntr=0.3,0.1

Type RM Length L Ch R = 1 ,33107   ,182.5,182.6,181
XS GIS Cut Line= 2
2331802.64732411636034.8342419782332152.31880306635762.395249338
#Sta/Elev= 30
       0 3191.45    10.8 3184.21    13.7 3182.85    22.2 3183.03    32.4 3182.22
    36.5 3180.12    42.5 3175.15    47.9 3172.31    87.8 3160.07    99.2 3154.38
   119.8 3139.86   124.8  3136.8   128.7 3135.13     149    3133   170.4 3132.48
   194.6 3131.99   201.8 3132.55   218.9 3135.01   270.7 3136.33     296 3138.21
   328.1 3139.32   341.7 3140.49   351.8 3143.54   356.9 3143.68     367 3142.74
   381.3 3143.86   402.5 3148.16   412.7 3148.71   422.8 3150.94   443.3 3159.28
#Mann= 5 ,-1,0
       0      .1       0      50     .06       0   170.4    .045       0
   201.8      .1       0     430     .06       0
Bank Sta=170.4,201.8
XS Rating Curve= 0 ,0
Exp/Cntr=0.3,0.1

Type RM Length L Ch R = 1 ,32925   ,322.7,325,322.8
XS GIS Cut Line= 2
2331928.91521033 636178.166443642332314.00751294635828.758369843
#Sta/Elev= 30
       0 3200.62     5.8 3194.81     9.8 3192.69    25.3 3193.35    28.5 3192.55
    43.1 3181.75    66.9 3169.77    74.6 3167.27   110.6 3150.24   136.73130.864
   144.3 3129.35   164.4 3130.83   172.9 3130.66     188 3133.12   235.2 3131.48
   269.1 3133.14   312.3 3132.47   323.1 3134.17   344.7 3134.89   382.4 3133.85
   387.9 3134.63   402.3 3138.43   424.1 3152.14     442 3160.37   461.8  3173.9
   468.9 3175.79   492.9 3177.59   495.9 3178.98   507.5 3188.21     520 3193.28
#Mann= 6 ,-1,0
       0     .06       0      70      .1       0   136.7    .045       0
   164.4      .1       0     420     .06       0     510      .1       0
#XS Ineff= 2 , 0
                          210.29         3139.33
Permanent Ineff=
       F       F
Bank Sta=136.7,164.4
XS Rating Curve= 0 ,0
Exp/Cntr(USF)=0,0
Exp/Cntr=0.3,0.1

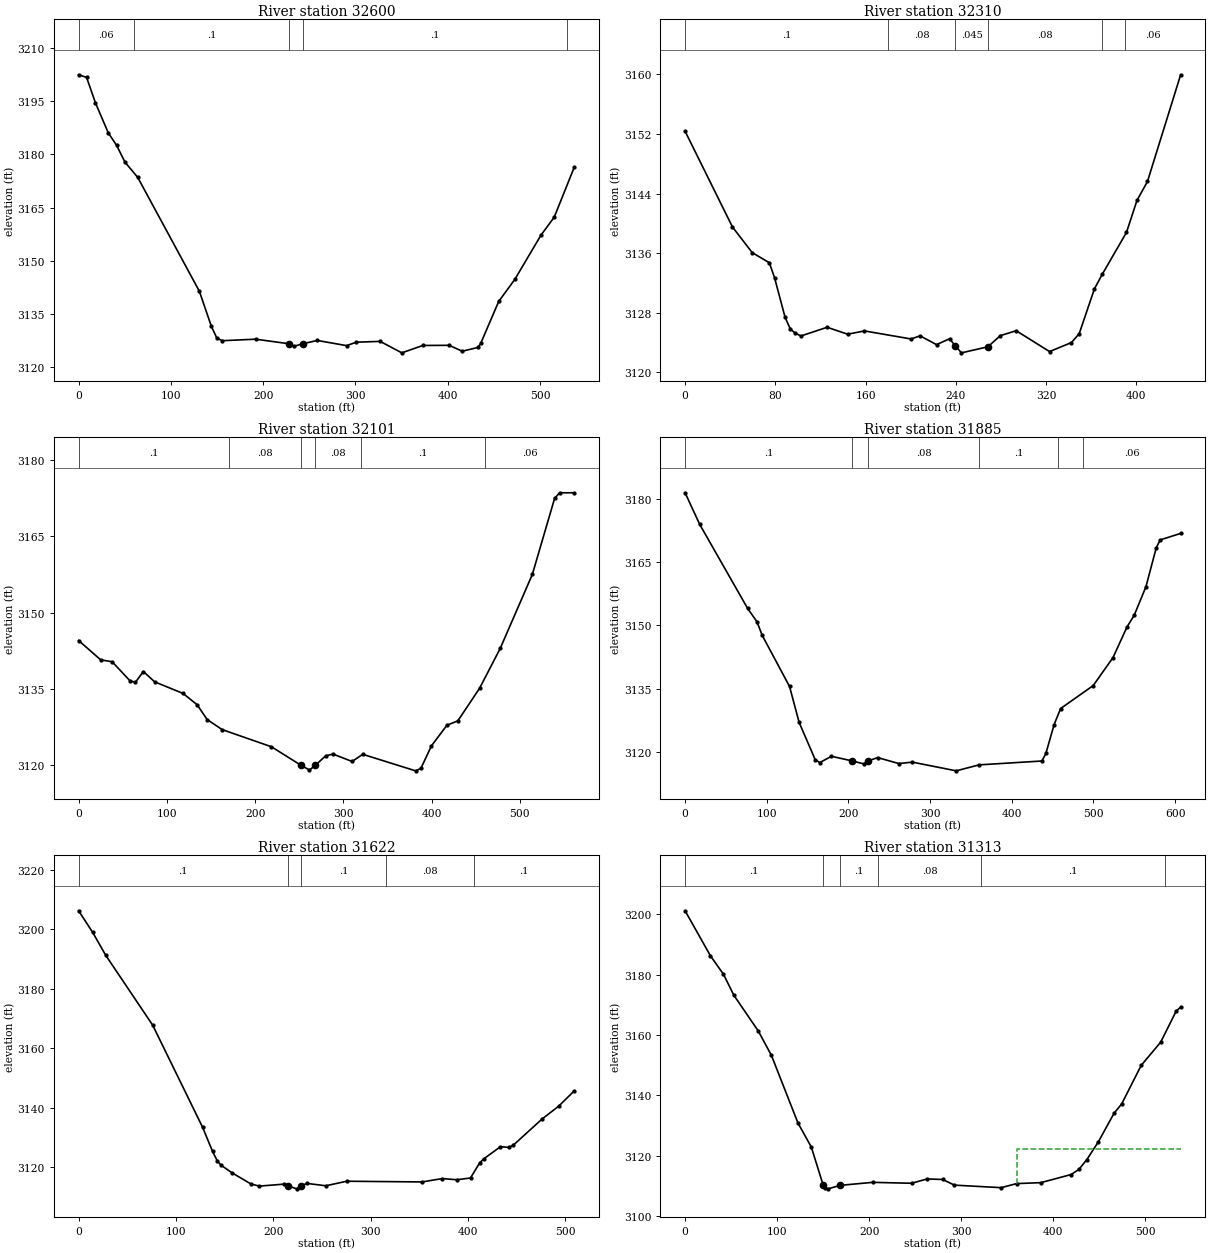
Type RM Length L Ch R = 1 ,32600   ,277.5,289.5,280.3
XS GIS Cut Line= 4
 2332084.2580439636320.9353405242332241.39747456636233.261318408
2332345.67903739636200.3595236972332540.40581543636047.172531057
#Sta/Elev= 30
       0 3202.46     8.6 3201.73    18.2 3194.57    32.1 3186.09    41.1 3182.59
    50.3 3177.79      64 3173.55   130.9  3141.4   143.8 3131.57   149.7 3128.25
   155.6 3127.47   191.8  3127.9   227.73126.627   233.2 3125.87   242.8 3126.61
   258.7 3127.54   290.5 3126.08   300.9 3127.05   326.8 3127.28   350.3 3124.05
   373.1 3126.13   401.6 3126.17   415.8 3124.51   432.9 3125.57   435.8 3126.71
   455.3 3138.54   472.8 3144.77   501.1 3157.23   515.5 3162.31   537.1 3176.33
#Mann= 5 ,-1,0
       0     .06       0      60      .1       0   227.7    .045       0
   242.8      .1       0  529.29     .06       0
Bank Sta=227.7,242.8
XS Rating Curve= 0 ,0
Exp/Cntr=0.3,0.1

Type RM Length L Ch R = 1 ,32310   ,200.3,209.1,209.5
XS GIS Cut Line= 2
2332342.80577572636465.3387796532332567.61641724636087.978059953
#Sta/Elev= 30
       0 3152.36      42 3139.51    59.5 3136.07    74.7 3134.71    79.3  3132.7
    88.6 3127.41    93.3 3125.81    97.4 3125.29   102.6 3124.88   125.9 3126.05
   144.1 3125.12     159 3125.56   200.4 3124.48   208.3  3124.9   222.9 3123.72
   234.5 3124.51   239.53123.567     245 3122.62   268.4 3123.43   279.5 3124.93
   293.5 3125.59   323.1 3122.79   342.5    3124   349.4  3125.2   362.9 3131.22
     370 3133.21   391.3 3138.79   400.6 3143.08   409.9 3145.62   439.3 3159.94
#Mann= 6 ,-1,0
       0      .1       0     180     .08       0   239.5    .045       0
   268.4     .08       0     370      .1       0     390     .06       0
Bank Sta=239.5,268.4
XS Rating Curve= 0 ,0
Exp/Cntr(USF)=0,0
Exp/Cntr=0.3,0.1

Type RM Length L Ch R = 1 ,32101   ,216.3,216.1,215.5
XS GIS Cut Line= 2
2332425.54536935636540.1567064712332843.46996453636165.203424993
#Sta/Elev= 30
       0 3144.53      25 3140.73      38 3140.36    58.4 3136.57    64.4 3136.33
    73.4 3138.44    86.1 3136.41   118.3 3134.13   134.3  3131.9   145.6    3129
   162.6 3127.02   218.5 3123.64   251.83120.019   261.5 3119.07     268 3119.96
     280 3121.87   288.3  3122.2   309.9 3120.75   321.9 3122.16   381.8 3118.91
   387.8 3119.39   399.8 3123.83   417.3 3127.87   429.7 3128.74   454.4 3135.17
   477.7 3142.98   514.1 3157.53   539.3 3172.46     545 3173.58   561.5 3173.58
#Mann= 6 ,-1,0
       0      .1       0     170     .08       0   251.8    .045       0
     268     .08       0     320      .1       0     460     .06       0
Bank Sta=251.8,268
XS Rating Curve= 0 ,0
Exp/Cntr=0.3,0.1

Type RM Length L Ch R = 1 ,31885   ,263.3,263,258.4
XS GIS Cut Line= 3
2332603.74669892636678.1059939522332883.42184224636410.474277852
2333006.53243165636228.484710905
#Sta/Elev= 30
       0 3181.53    17.9 3174.01    76.6 3154.03    88.1 3150.85    94.3 3147.68
   127.9 3135.49   139.6 3126.97   159.4 3118.05     165 3117.41   179.2  3118.9
   204.7 3117.79   218.8  3117.1   224.5 3117.82   235.8 3118.59   261.7 3117.17
   278.2 3117.51     332 3115.44     360 3116.86     437 3117.78   441.8 3119.59
   451.9 3126.45   459.8 3130.24   499.7  3135.7     524 3142.36   541.2 3149.67
   549.9  3152.4   564.3 3159.19     577  3168.5   581.8 3170.33   606.8 3171.87
#Mann= 6 ,-1,0
       0      .1       0   204.7    .045       0   224.5     .08       0
     360      .1       0   457.1     .08       0   487.1     .06       0
Bank Sta=204.7,224.5
XS Rating Curve= 0 ,0
Exp/Cntr(USF)=0,0
Exp/Cntr=0.3,0.1

Type RM Length L Ch R = 1 ,31622   ,300.8,308.9,308.5
XS GIS Cut Line= 3
 2332868.3546312636810.252962705 2332941.6679045636650.406143126
2333058.37354091636338.248225235
#Sta/Elev= 30
       0 3206.19    14.4 3198.94    27.8 3191.24    76.1  3167.7   127.4 3133.34
   137.6 3125.24   142.5 3122.01   146.4  3120.6   157.6 3118.04   177.2 3114.27
   185.7 3113.58   211.3 3114.25   214.6 3113.74   224.1 3112.66   228.7 3113.71
   234.7 3114.48     254 3113.69   275.4 3115.22   352.8 3114.98   373.6 3116.11
   388.6 3115.72   402.6 3116.31     412  3121.4   416.3 3122.77   433.4 3126.84
   441.9  3126.6   446.2 3127.24   476.1 3136.14   493.2 3140.47   509.1 3145.58
#Mann= 5 ,-1,0
       0      .1       0   214.6    .045       0   228.7      .1       0
  315.86     .08       0  405.86      .1       0
Bank Sta=214.6,228.7
XS Rating Curve= 0 ,0
Exp/Cntr=0.3,0.1

Type RM Length L Ch R = 1 ,31313   ,215.1,210.1,208.4
XS GIS Cut Line= 3
2333066.20275346636900.3962507042333179.41096937636722.153527782
2333285.39312894636412.637448113
#Sta/Elev= 30
       0 3201.16    27.5 3186.25    41.7  3180.1      53 3173.14    79.6 3161.25
    93.8  3153.2   122.6  3130.8   137.1 3122.83   149.83110.401   151.6 3109.28
   155.4 3108.97   168.33110.122   203.7 3111.12     246 3110.82   262.9 3112.25
   279.8 3112.07   292.5  3110.2   343.3 3109.36   360.2 3110.71   386.4 3111.02
   419.4 3113.72   427.8 3115.41   436.3 3118.63     449 3124.59   465.9    3134
   474.3 3137.15   495.5 3149.92   516.6 3157.59   533.5 3167.92   538.3  3169.2
#Mann= 6 ,-1,0
       0      .1       0   149.8    .045       0   168.3      .1       0
     210     .08       0  321.16      .1       0  521.16     .06       0
#XS Ineff= 2 , 0
                          360.54         3122.16
Permanent Ineff=
       F       F
Bank Sta=149.8,168.3
XS Rating Curve= 0 ,0
Exp/Cntr(USF)=0,0
Exp/Cntr=0.3,0.1

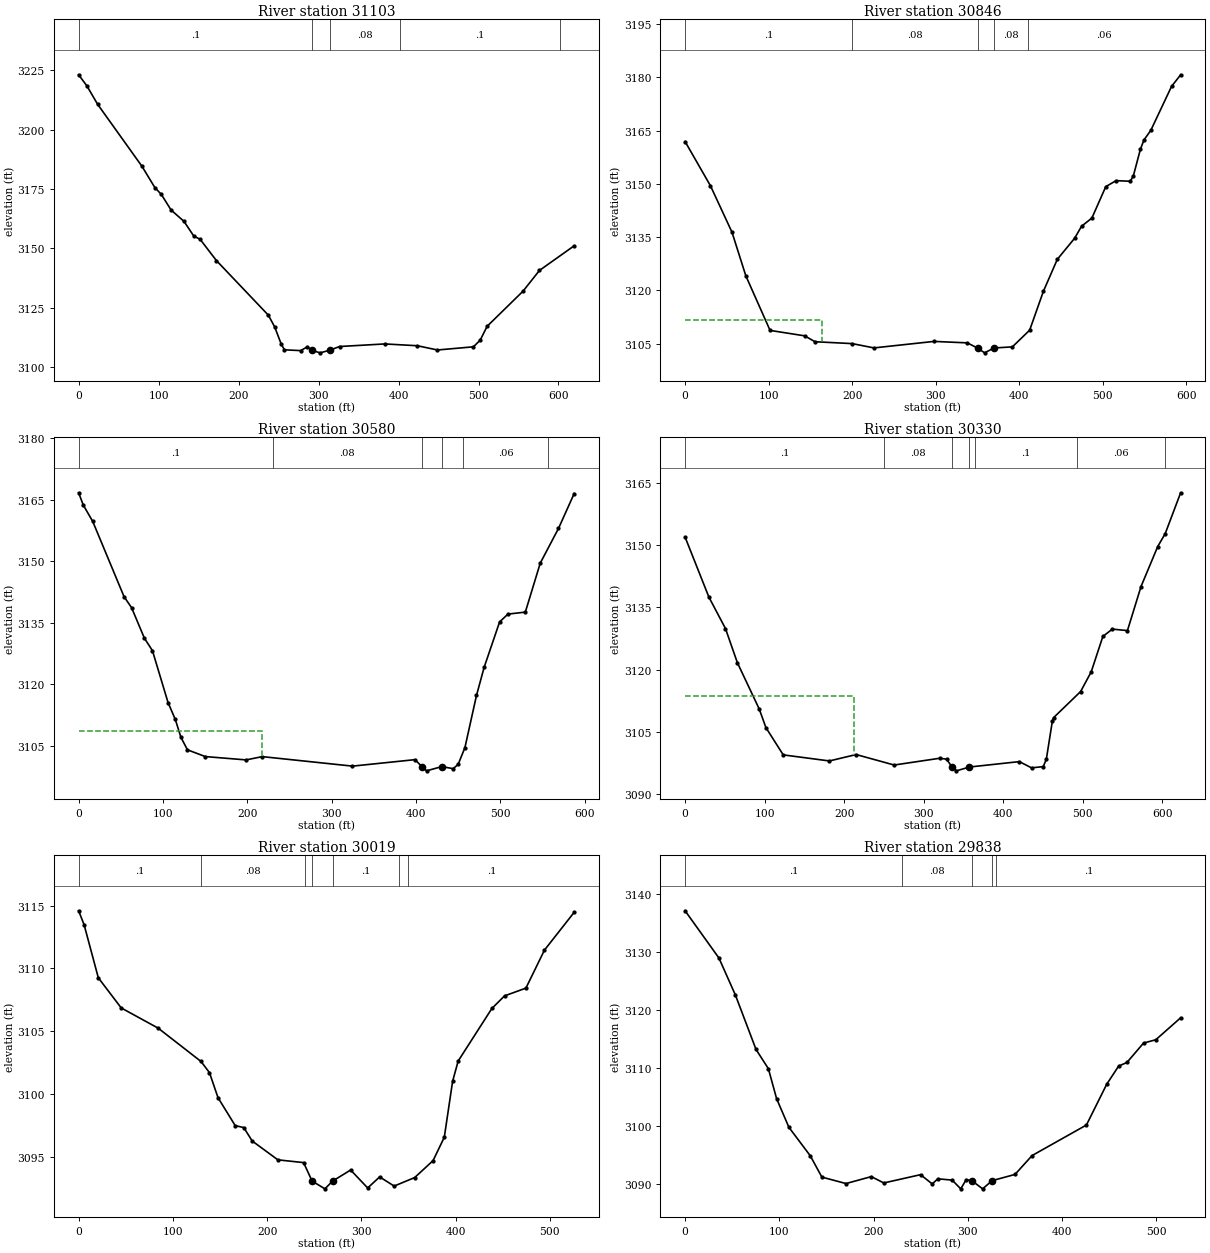
Type RM Length L Ch R = 1 ,31103   ,258.1,257.6,259.4
XS GIS Cut Line= 3
2333303.04110095637115.3309381152333364.37192581636728.302630652
2333418.37981451636507.049645952
#Sta/Elev= 30
       0 3223.08    10.3 3218.41    23.8 3210.62    79.1 3184.57    95.3 3175.58
   103.4 3172.69   115.6 3166.12   131.8 3161.31   143.9 3155.19     152 3153.74
   172.3 3144.82   237.3 3121.79   245.2 3116.82   253.3 3109.65   257.3 3107.23
   277.6  3106.9   285.7 3108.44   292.33106.964   301.9 3105.96     314 3107.06
   326.2 3108.62   382.9 3109.71   423.6 3108.95   448.6 3107.16   493.6  3108.5
   502.1 3111.31   510.8 3117.15   555.7 3131.95   576.2 3140.67   619.6 3151.05
#Mann= 5 ,-1,0
       0      .1       0   292.3    .045       0     314     .08       0
  401.86      .1       0  601.86     .06       0
Bank Sta=292.3,314
XS Rating Curve= 0 ,0
Exp/Cntr=0.3,0.1

Type RM Length L Ch R = 1 ,30846   ,263.3,265.4,268.1
XS GIS Cut Line= 2
2333505.24615401637115.3707538632333659.43726616636542.660908713
#Sta/Elev= 30
       0 3161.92    30.3 3149.48    56.1 3136.39    72.7 3124.08   101.7  3108.7
   143.1 3107.17   155.5 3105.51     200 3104.98     226 3103.77   297.9  3105.6
   337.8 3105.19   350.1 3103.71   358.5 3102.38   369.7 3103.75   391.7 3104.06
   412.4 3108.77   428.9 3119.76   445.5 3128.73   466.2 3134.67   474.5 3138.05
   486.9 3140.37   503.5 3149.22   515.9 3150.91   532.9 3150.73   536.6 3152.33
   544.9 3159.72   549.2 3162.37   557.4 3165.08   582.2 3177.45   593.1 3180.74
#Mann= 5 ,-1,0
       0      .1       0     200     .08       0   350.1    .045       0
   369.7     .08       0     410     .06       0
#XS Ineff= 2 , 0
          163.48 3111.56
Permanent Ineff=
       F       F
Bank Sta=350.1,369.7
XS Rating Curve= 0 ,0
Exp/Cntr(USF)=0,0
Exp/Cntr=0.3,0.1

Type RM Length L Ch R = 1 ,30580   ,244,250.4,260.1
XS GIS Cut Line= 3
2333621.64158266637209.7643175062333775.86096726636980.846631763
2333925.07927041636707.539869936
#Sta/Elev= 30
       0 3166.74     5.5 3163.74    16.7 3159.75    53.8  3141.4    62.8 3138.68
    77.9 3131.27    87.5  3128.2     106 3115.53   114.6 3111.41   121.3 3107.03
     129    3104   150.2 3102.35   198.5 3101.54   217.7 3102.34   324.6 3100.02
   398.7  3101.6   406.93099.912   412.4 3098.87   430.6 3099.91     444  3099.4
   449.9 3100.46   457.9 3104.54   471.6 3117.26   480.7 3124.15     499 3135.21
   508.9 3137.13   529.5 3137.61   547.2 3149.57   568.8 3158.03   587.4 3166.55
#Mann= 6 ,-1,0
       0      .1       0     230     .08       0   406.9    .045       0
   430.6     .08       0  456.02     .06       0  556.02      .1       0
#XS Ineff= 2 , 0
          217.75 3108.59
Permanent Ineff=
       F       F
Bank Sta=406.9,430.6
XS Rating Curve= 0 ,0
Exp/Cntr=0.3,0.1

Type RM Length L Ch R = 1 ,30330   ,311.7,310.8,290.3
XS GIS Cut Line= 4
 2333798.9435105637287.9179507992333920.09367005637041.946414741
2334033.90139569637007.069853658 2334133.0242535636799.646095639
#Sta/Elev= 30
       0 3151.88    29.9 3137.46    50.8 3129.87    65.7 3121.68    93.3 3110.49
   101.6 3106.06   123.4 3099.49   181.4 3098.03   215.1 3099.57   262.9 3097.05
   320.3 3098.68   328.7 3098.46   335.7 3096.57   341.2 3095.65   357.6 3096.57
   420.3 3097.87   435.6 3096.37   450.3 3096.66   454.2 3098.41   461.8 3107.63
   463.4 3108.46   497.3 3114.72   510.6 3119.44   525.3 3127.98   537.2 3129.75
   556.2 3129.39   573.3    3140   594.3 3149.62   603.7 3152.72   623.1 3162.55
#Mann= 7 ,-1,0
       0      .1       0     250     .08       0   335.7    .045       0
   357.6     .08       0  364.19      .1       0  493.22     .06       0
  603.22      .1       0
#XS Ineff= 2 , 0
           212.1 3113.72
Permanent Ineff=
       F       F
Bank Sta=335.7,357.6
XS Rating Curve= 0 ,0
Exp/Cntr(USF)=0,0
Exp/Cntr=0.3,0.1

Type RM Length L Ch R = 1 ,30019   ,182,180.4,176
XS GIS Cut Line= 2
2334041.45629015637427.5864822912334289.59615736636963.985664397
#Sta/Elev= 30
       0 3114.58     5.8 3113.47    20.9 3109.24    45.2 3106.84    84.4 3105.23
   129.8 3102.58   138.8 3101.69   147.9 3099.69   166.1 3097.47   175.2 3097.31
   184.2 3096.24   211.4 3094.74   238.7 3094.52   247.7 3093.05   261.3 3092.43
  269.453093.044   288.6 3093.93   306.7  3092.5   319.4 3093.38   334.8 3092.65
   356.6 3093.33   376.1 3094.68     388 3096.54   396.8 3100.99   402.7 3102.61
   438.5  3106.8   451.9  3107.8   474.6 3108.42   494.3 3111.45   525.8 3114.46
#Mann= 7 ,-1,0
       0      .1       0     130     .08       0     240      .1       0
   247.7    .045       0  269.45      .1       0     340     .08       0
     350      .1       0
Bank Sta=247.7,269.45
XS Rating Curve= 0 ,0
Exp/Cntr=0.3,0.1

Type RM Length L Ch R = 1 ,29838   ,236.7,240.4,239.9
XS GIS Cut Line= 2
2334207.01315776637517.9876422542334419.94374121637037.058221006
#Sta/Elev= 30
       0 3137.09    35.9 3128.96    53.4 3122.58    75.3 3113.21    88.4  3109.9
    97.1 3104.75   110.2  3099.8   132.8 3094.92   145.2 3091.23   170.8 3090.12
   197.7 3091.32   210.9 3090.22   249.9 3091.65   262.3 3090.06   268.3 3090.94
   283.5 3090.71   292.6 3089.21   298.4 3090.79   304.7 3090.58   315.8 3089.21
   325.9 3090.62   350.2 3091.69   368.3 3094.94     426  3100.2   447.5 3107.21
   460.2 3110.35     469 3110.97   486.6 3114.31   499.6 3114.88     526 3118.66
#Mann= 5 ,-1,0
       0      .1       0     230     .08       0   304.7    .045       0
   325.9     .08       0     330      .1       0
Bank Sta=304.7,325.9
XS Rating Curve= 0 ,0
Exp/Cntr(USF)=0,0
Exp/Cntr=0.3,0.1