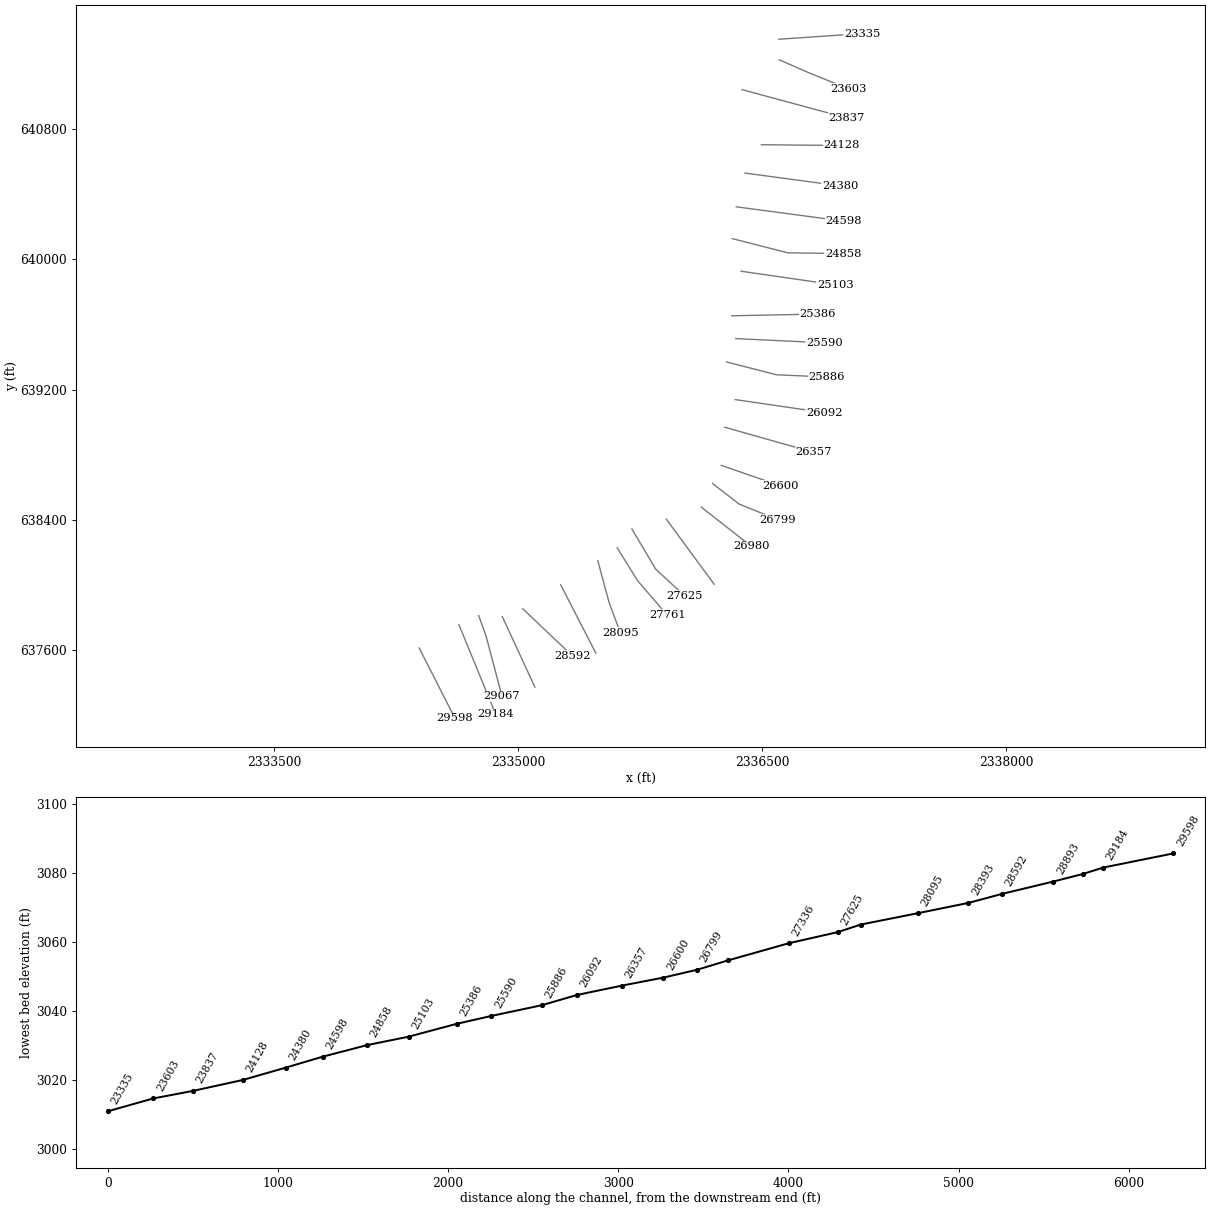
HEC-RAS study EFKGLADYFK.prj: EFKGLADYFK

--- EFKGLADYFK.g01 (geometry) --- (continued)

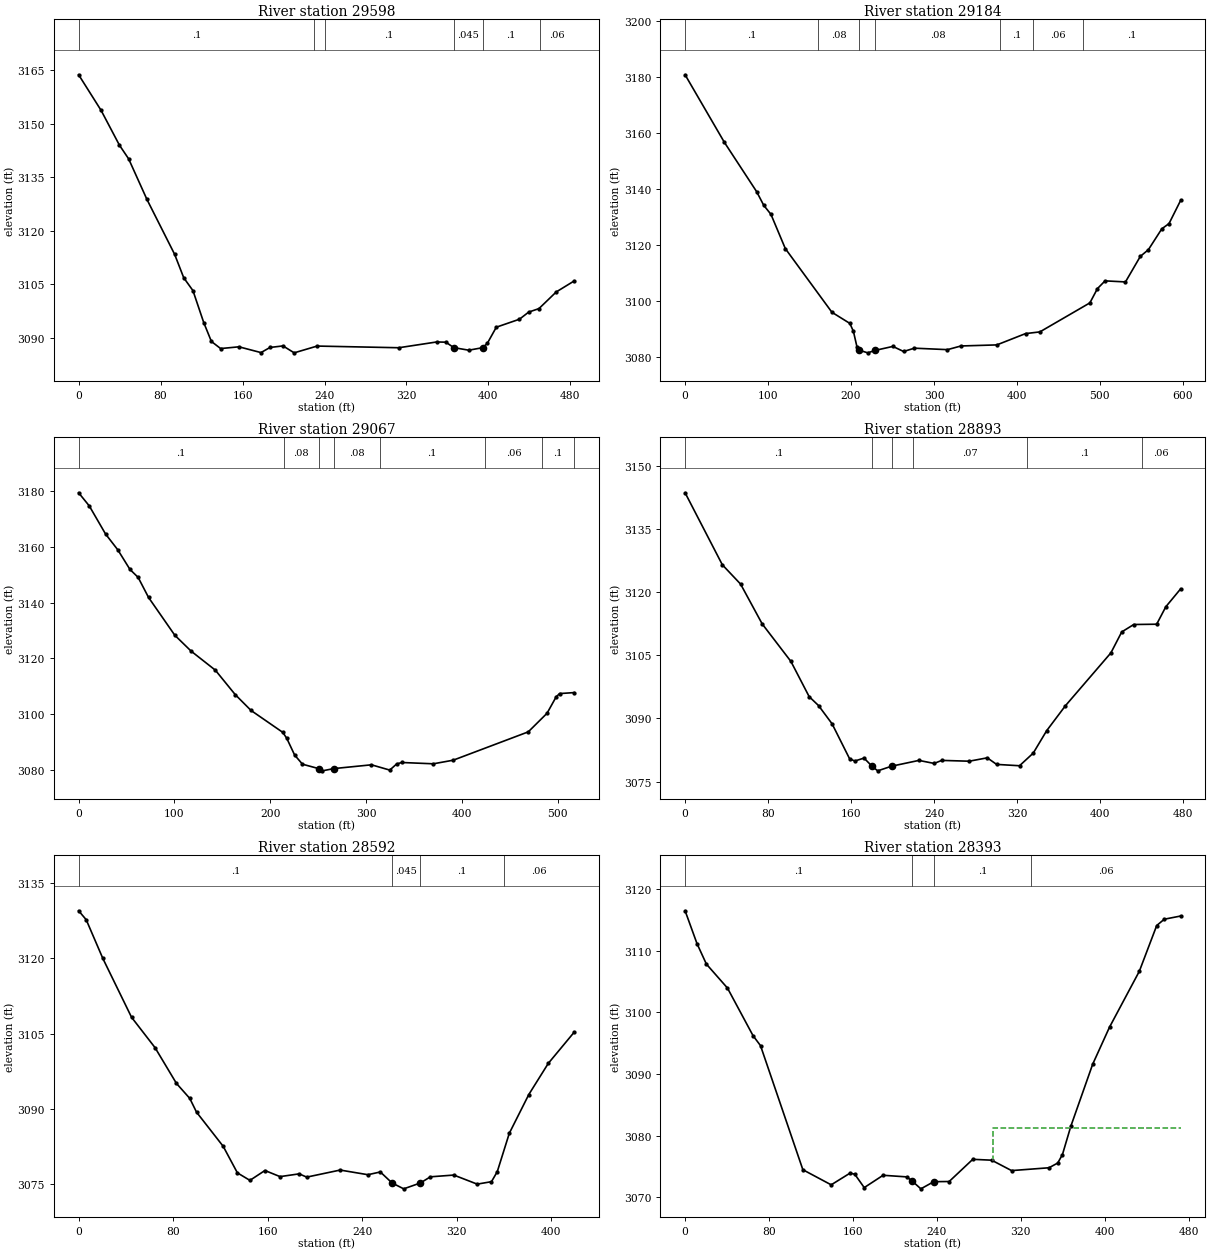
Type RM Length L Ch R = 1 ,29598   ,401.1,413.9,408.6
XS GIS Cut Line= 2
2334391.40281274637612.6546173552334610.85281274637181.605745495
#Sta/Elev= 30
       0 3163.68    21.9 3153.71    39.8 3143.95    48.8 3140.11    66.7 3128.71
    93.7 3113.33   102.6 3106.75   111.6 3103.14   122.1  3094.2   129.6 3088.89
   138.6  3086.9   156.5 3087.39     178 3085.77   186.8 3087.21   199.5 3087.64
   210.4  3085.7   232.8  3087.6   312.5 3087.13   349.5 3088.75   358.5 3088.69
   366.13087.169   380.8 3086.44   394.4 3087.15   398.9 3088.35   407.7 3092.89
   430.3 3095.13   439.3 3097.13   449.3  3098.1   466.2 3102.78   483.7 3105.86
#Mann= 6 ,-1,0
       0      .1       0     230     .08       0     240      .1       0
   366.1    .045       0   394.4      .1       0     450     .06       0
Bank Sta=366.1,394.4
XS Rating Curve= 0 ,0
Exp/Cntr=0.3,0.1

Type RM Length L Ch R = 1 ,29184   ,118.8,116.8,115.7
XS GIS Cut Line= 2
2334635.27250425637756.8994451692334861.98358239637204.185319519
#Sta/Elev= 30
       0 3180.76    47.3 3156.69    86.2  3139.1    94.8 3134.21   103.5 3130.98
   120.8 3118.78     177 3096.06   198.6 3092.09   202.9 3089.27   207.2 3083.72
  209.593082.563   220.2 3081.59   229.2 3082.47   250.5 3083.88   263.4 3082.07
   276.4 3083.25   316.3 3082.73   332.6 3084.04   375.8 3084.42   410.4 3088.45
   427.7 3089.06     488 3099.41   497.1  3104.5   506.3 3107.26   530.9 3106.88
   548.8 3115.99   558.5 3118.37   574.7 3125.82   583.4 3127.69   597.4 3135.95
#Mann= 7 ,-1,0
       0      .1       0     160     .08       0  209.59    .045       0
   229.2     .08       0     380      .1       0     420     .06       0
     480      .1       0
Bank Sta=209.59,229.2
XS Rating Curve= 0 ,0
Exp/Cntr(USF)=0,0
Exp/Cntr=0.3,0.1

Type RM Length L Ch R = 1 ,29067   ,171.9,174.6,174.2
XS GIS Cut Line= 3
2334757.05542499637811.608372596     2334802.737637685.459477009
2334900.65871328637315.030715632
#Sta/Elev= 30
       0 3179.34    11.1 3174.64    28.1 3164.58    40.9  3158.9    53.6 3151.88
    62.1 3149.05      73 3141.85   100.4 3128.32   117.4 3122.64   142.7 3115.82
   163.4 3107.09     180 3101.38   213.1 3093.54   217.2 3091.46   225.5 3085.41
   233.7 3082.13   250.6 3080.56   254.4 3079.76   266.5 3080.57   305.7 3081.92
   324.8 3080.03   331.9 3082.19   337.2 3082.75   370.3 3082.28     391 3083.57
   469.4 3093.72     489 3100.38   498.5 3106.25   502.1 3107.43   517.3 3107.78
#Mann= 8 ,-1,0
       0      .1       0  214.17     .08       0   250.6    .045       0
   266.5     .08       0  314.17      .1       0  424.17     .06       0
  484.17      .1       0  517.32     .06       0
Bank Sta=250.6,266.5
XS Rating Curve= 0 ,0
Exp/Cntr=0.3,0.1

Type RM Length L Ch R = 1 ,28893   ,295.1,300.3,304.4
XS GIS Cut Line= 2
2334902.08819505 637805.754509382335102.61125833  637372.1911293
#Sta/Elev= 30
       0 3143.63    35.9 3126.52    53.5 3121.93    74.3 3112.48     102 3103.56
   119.6 3095.19   128.6 3093.08   141.7 3088.73   158.7 3080.37   163.7  3079.9
   172.5 3080.59   180.23078.647   185.7 3077.56     199 3078.66   225.4 3080.04
   240.1 3079.32   247.4 3080.04   273.9 3079.85   291.3 3080.65   300.3 3079.09
   322.4 3078.77   335.6 3081.77   348.5 3087.08   366.6 3093.02   410.5  3105.6
   420.9 3110.56   432.5 3112.33   454.6  3112.4   463.4 3116.54   477.7  3120.8
#Mann= 6 ,-1,0
       0      .1       0   180.2    .045       0     199      .1       0
     220     .07       0     330      .1       0     440     .06       0
Bank Sta=180.2,199
XS Rating Curve= 0 ,0
Exp/Cntr(USF)=0,0
Exp/Cntr=0.3,0.1

Type RM Length L Ch R = 1 ,28592   ,201.2,199,193.9
XS GIS Cut Line= 2
2335027.64990726637853.6828177632335332.00579921637565.032534661
#Sta/Elev= 30
       0 3129.51     6.4 3127.73    20.5 3119.99    44.8 3108.25    64.7 3102.18
    82.8 3095.05    94.1 3092.05    99.8 3089.31   122.4 3082.48   134.4 3077.19
     145 3075.69   157.7 3077.66   170.5 3076.44   186.7 3076.99   193.1 3076.34
   221.4 3077.75   244.9 3076.82   255.4 3077.37   265.3 3075.18   275.2    3074
   289.3 3075.17   297.8  3076.4   317.6 3076.75   337.4 3074.94   349.5 3075.43
   354.4 3077.43   364.6  3085.1   381.1 3092.83   397.6 3099.05   419.5 3105.27
#Mann= 4 ,-1,0
       0      .1       0   265.3    .045       0   289.3      .1       0
     360     .06       0
Bank Sta=265.3,289.3
XS Rating Curve= 0 ,0
Exp/Cntr=0.3,0.1

Type RM Length L Ch R = 1 ,28393   ,297.5,298.2,293.1
XS GIS Cut Line= 2
 2335260.7753614638001.0731470542335476.96924882637580.922762079
#Sta/Elev= 30
       0 3116.49    11.4 3111.14    20.3 3107.84    40.4 3103.95    64.8 3096.22
    71.9 3094.61   112.3 3074.47   139.3 3072.02   157.3 3073.92   161.8 3073.74
   170.8 3071.57   188.8 3073.57   211.3 3073.31   216.63072.623   224.8 3071.37
   237.1 3072.53   251.8 3072.56   274.3 3076.16   292.3 3076.02   311.3 3074.33
     347 3074.79   355.3 3075.56   359.8 3076.93   367.8 3081.53   388.6 3091.58
   404.7 3097.61   433.1 3106.67   449.7  3114.1   456.9 3115.12   472.5 3115.64
#Mann= 4 ,-1,0
       0      .1       0   216.6    .045       0   237.1      .1       0
     330     .06       0
#XS Ineff= 2 , 0
                          293.67         3081.31
Permanent Ineff=
       F       F
Bank Sta=216.6,237.1
XS Rating Curve= 0 ,0
Exp/Cntr(USF)=0,0
Exp/Cntr=0.3,0.1

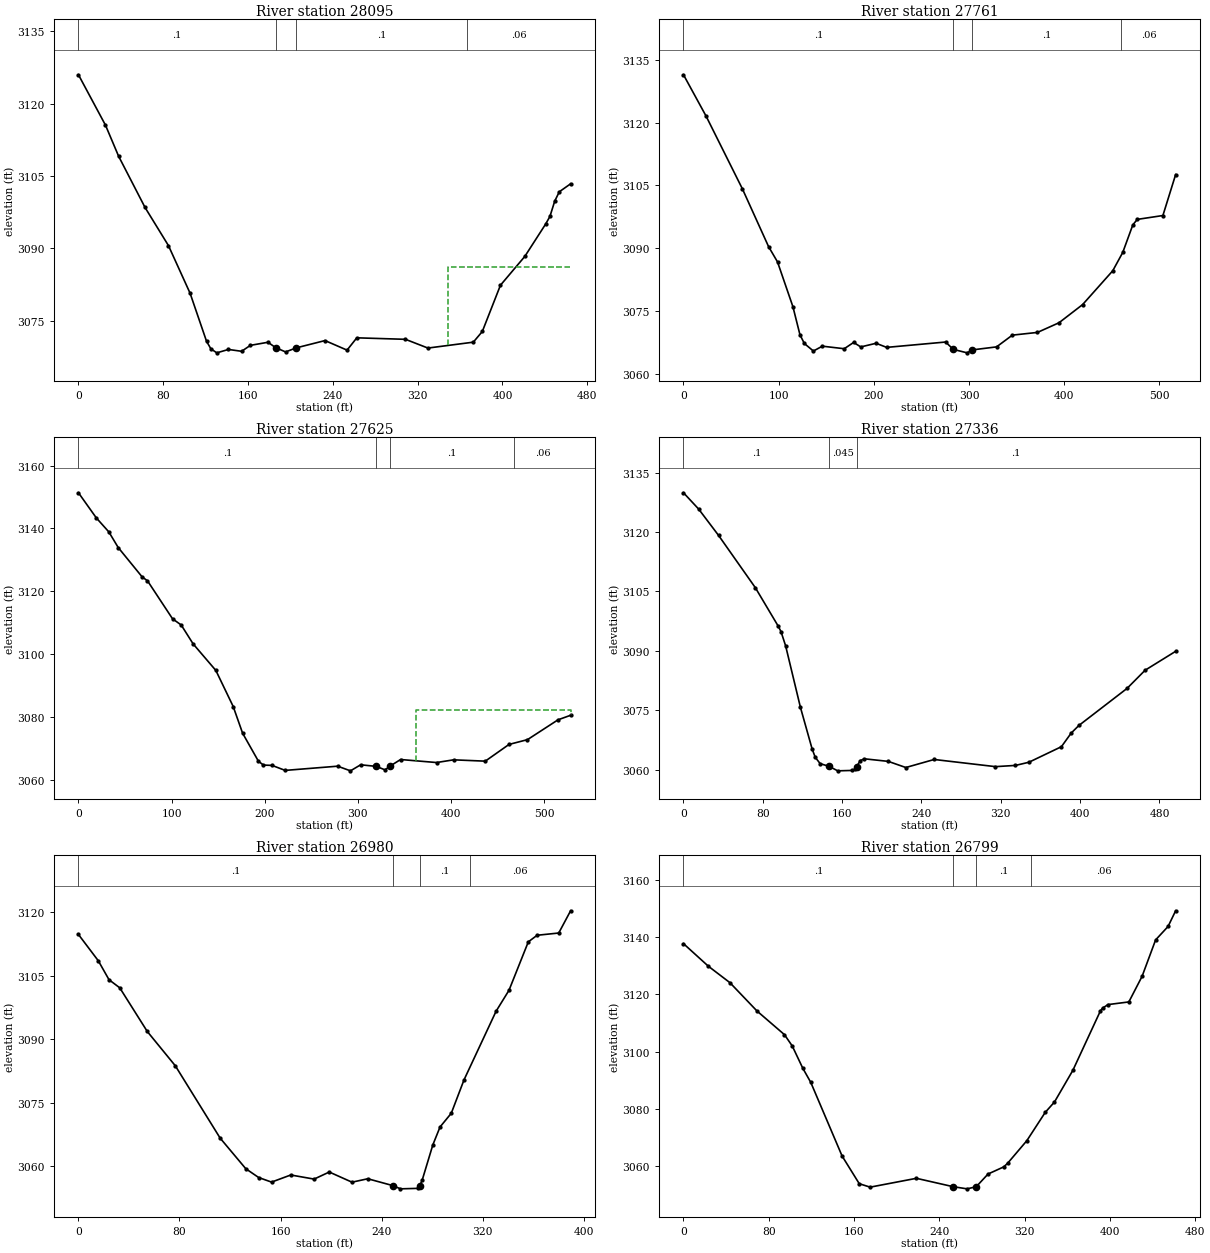
Type RM Length L Ch R = 1 ,28095   ,326.2,334.7,335.5
XS GIS Cut Line= 3
2335488.77721604 638149.802386232335558.06483306637892.722500812
2335627.26296726637707.197630139
#Sta/Elev= 30
       0 3125.97    25.5 3115.53    37.9 3109.09    62.8 3098.49    84.9 3090.59
   105.3 3080.73   120.8 3070.79   124.9 3069.22   130.5 3068.38   141.5 3069.08
   153.9  3068.7   162.2 3069.93   178.8 3070.57     186 3069.46   195.4 3068.57
   205.6 3069.42   232.6 3070.92   253.4 3068.94   262.6 3071.49   308.5 3071.18
   329.7 3069.37   372.5 3070.59     381  3072.8   398.1 3082.38   421.1 3088.35
   440.8 3095.07   444.8 3096.64   449.3 3099.79   453.6 3101.73   464.3 3103.39
#Mann= 4 ,-1,0
       0      .1       0     186    .045       0   205.6      .1       0
  366.25     .06       0
#XS Ineff= 2 , 0
                          349.07         3086.21
Permanent Ineff=
       F       F
Bank Sta=186,205.6
XS Rating Curve= 0 ,0
Exp/Cntr=0.3,0.1

Type RM Length L Ch R = 1 ,27761   ,135.2,136,136.5
XS GIS Cut Line= 3
2335607.46700436638229.0730913012335734.24629749638025.095347293
2335914.89770586637815.004450155
#Sta/Elev= 30
       0  3131.4    23.7 3121.56      62 3104.15    89.4 3090.43    98.8 3086.78
     115 3076.09   122.4  3069.4     127 3067.33   136.5 3065.53   145.9 3066.69
   168.9 3066.08   178.8 3067.58   186.3 3066.51   202.4 3067.38   213.5  3066.4
   275.5 3067.68   283.53065.922   298.1  3065.1   303.4  3065.8     329 3066.52
   345.6 3069.32     372 3069.97   394.6 3072.27   419.4  3076.6   451.1 3084.67
   461.6 3089.03   472.2 3095.61   476.9 3096.92   503.8 3097.84   517.2 3107.61
#Mann= 4 ,-1,0
       0      .1       0   283.5    .045       0   303.4      .1       0
  460.17     .06       0
Bank Sta=283.5,303.4
XS Rating Curve= 0 ,0
Exp/Cntr(USF)=0,0
Exp/Cntr=0.3,0.1

Type RM Length L Ch R = 1 ,27625   ,288.9,288.9,281.6
XS GIS Cut Line= 3
2335698.40801738638344.066342944 2335845.0083756638096.535028167
2336022.14077067637933.639869009
#Sta/Elev= 30
       0 3151.33    19.2 3143.33    32.6 3138.89    42.7  3133.9    68.4 3124.56
    74.1 3123.34     101 3111.25   110.3 3109.28   123.1 3103.27   147.5 3094.82
   166.1 3083.36   176.2 3074.87   193.2 3065.95   198.6 3064.73   207.8 3064.63
   221.9 3063.04   278.2 3064.38     292  3062.9   302.9 3064.82   319.73064.319
   329.1 3063.21     334 3064.32   345.8  3066.5   384.4 3065.54   402.7  3066.4
   436.7 3065.98   462.2  3071.3     482 3072.82   514.8 3079.13   528.3 3080.57
#Mann= 4 ,-1,0
       0      .1       0   319.7    .045       0     334      .1       0
  467.69     .06       0
#XS Ineff= 2 , 0
                          362.24         3082.36
Permanent Ineff=
       F       F
Bank Sta=319.7,334
XS Rating Curve= 0 ,0
Exp/Cntr=0.3,0.1

Type RM Length L Ch R = 1 ,27336   ,348.5,355.8,350.8
XS GIS Cut Line= 2
2335909.79172069638404.1901401062336203.85619887638004.394613588
#Sta/Elev= 30
       0 3129.93    15.3 3125.81    35.3 3119.18    72.5 3105.93    95.4 3096.28
    98.3 3094.87     103 3091.25   117.9 3075.73   129.7 3065.21   132.8 3063.12
   137.8 3061.49   146.9  3060.8   155.5 3059.67   169.8 3059.77   172.7 3060.01
   174.53060.736   178.4 3062.28   182.5 3062.71   206.5 3062.06   224.2 3060.51
   252.8 3062.54   314.6 3060.73   334.8 3061.04   348.3 3061.84   381.1 3065.77
     391 3069.22   398.7 3071.13   447.3  3080.5   465.5 3085.09   496.3 3089.87
#Mann= 3 ,-1,0
       0      .1       0   146.9    .045       0   174.5      .1       0
Bank Sta=146.9,174.5
XS Rating Curve= 0 ,0
Exp/Cntr(USF)=0,0
Exp/Cntr=0.3,0.1

Type RM Length L Ch R = 1 ,26980   ,176.7,181.1,182.7
XS GIS Cut Line= 2
2336123.82110771 638478.779858242336430.58876857638238.427108134
#Sta/Elev= 30
       0 3114.77    15.7 3108.57    24.2 3104.09    32.7 3102.18    54.5 3091.87
    76.7 3083.77   112.2 3066.69   132.5 3059.47   142.7 3057.39   152.9 3056.31
   168.1 3057.99   186.6 3057.02   198.6 3058.69   216.6 3056.29   229.1  3057.1
   249.1 3055.47     255 3054.72   268.5 3054.83   270.23055.477   272.1  3056.7
   280.6 3065.09   286.3 3069.32   295.2 3072.56   305.3 3080.45   330.7 3096.66
   340.9 3101.59   356.2 3113.03   363.2 3114.59   380.3 3115.12   389.7 3120.37
#Mann= 4 ,-1,0
       0      .1       0   249.1    .045       0   270.2      .1       0
     310     .06       0
Bank Sta=249.1,270.2
XS Rating Curve= 0 ,0
Exp/Cntr=0.3,0.1

Type RM Length L Ch R = 1 ,26799   ,202,198.3,200.8
XS GIS Cut Line= 3
 2336193.8084488638623.6435793782336356.97364685 638497.19055089
2336593.56318402638401.330997037
#Sta/Elev= 30
       0 3137.73    23.4 3129.82    43.5 3124.11      69 3114.17    94.7 3105.92
     102 3101.98   111.9 3094.19   119.4 3089.23   148.8 3063.47   164.9  3053.8
   175.1  3052.6   218.5 3055.69     253 3052.76     266 3052.01   274.6 3052.74
   285.7 3057.19   300.5  3059.7   304.1 3060.96   322.1 3068.85   339.4 3078.77
     348 3082.36   365.3 3093.46   391.1 3114.21   393.2  3115.2   398.2 3116.43
   417.8 3117.36   430.2  3126.3   442.9 3139.04   454.6 3143.75   461.7 3149.23
#Mann= 4 ,-1,0
       0      .1       0     253    .045       0   274.6      .1       0
  326.43     .06       0
Bank Sta=253,274.6
XS Rating Curve= 0 ,0
Exp/Cntr(USF)=0,0
Exp/Cntr=0.3,0.1

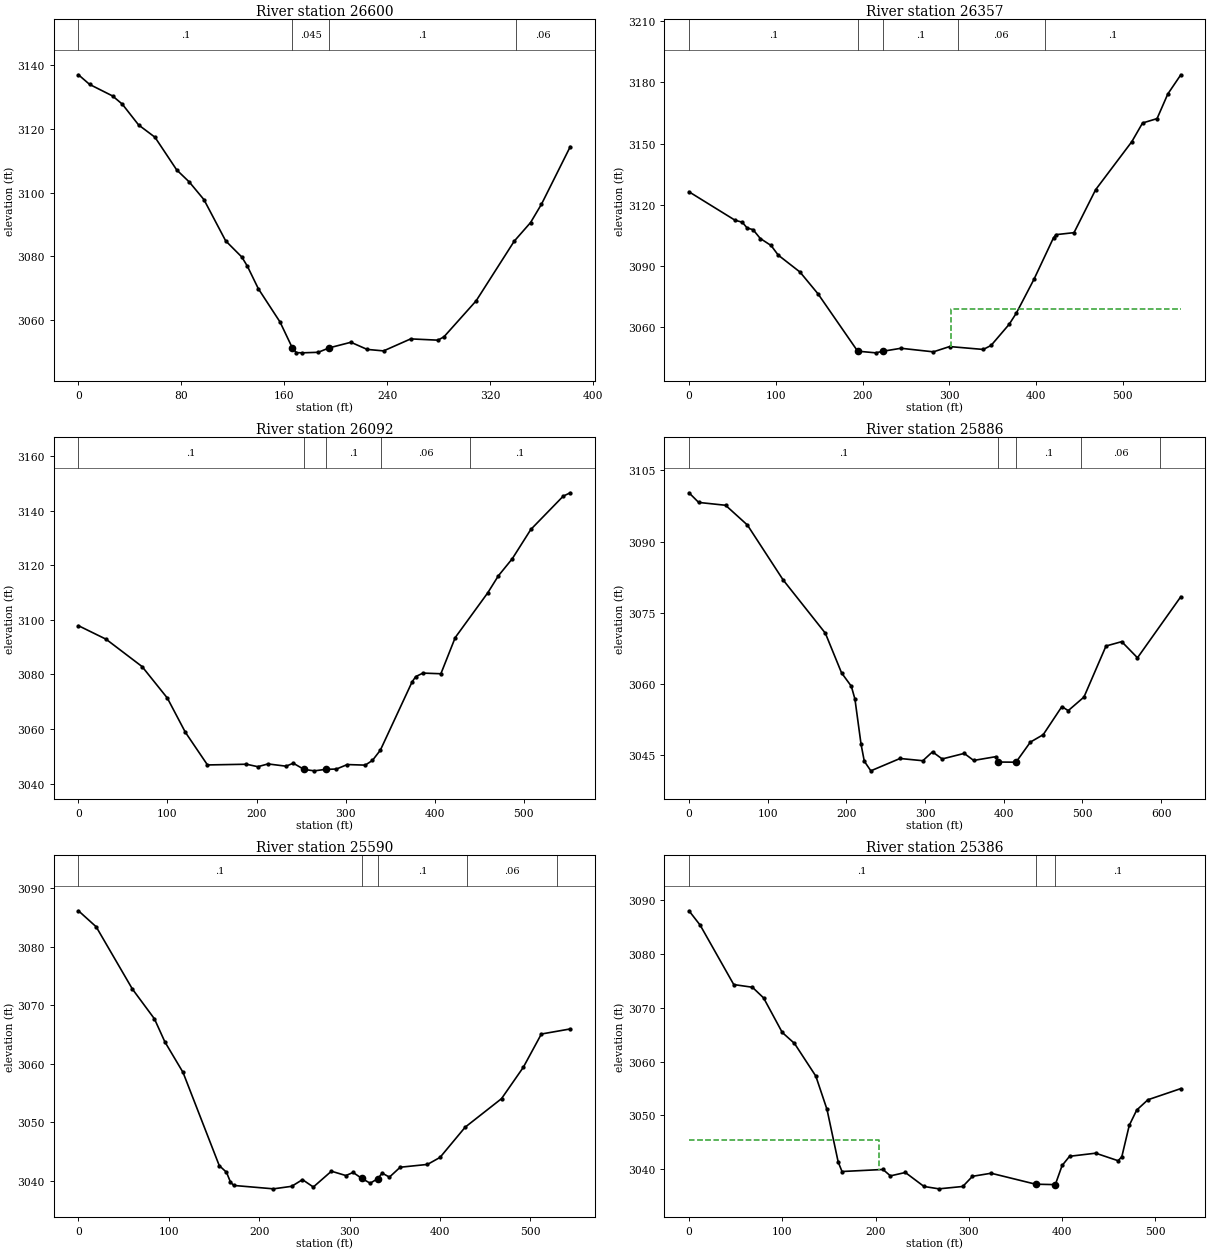
Type RM Length L Ch R = 1 ,26600   ,242.1,243.7,243.8
XS GIS Cut Line= 2
  2336247.994492638734.6927963892336609.36441278 638609.37692078
#Sta/Elev= 30
       0 3137.07     8.7 3134.04    26.5 3130.43    34.1 3127.85    46.8 3121.31
    59.5 3117.46    76.4  3107.2    86.2  3103.4    97.6 3097.86   114.5 3084.91
   127.1 3079.81   131.4 3076.94   139.9 3069.88   156.8 3059.41   166.4 3051.24
   169.5 3049.81   173.8 3049.74   186.5 3049.91   194.9 3051.29   211.9 3053.06
   224.5 3050.82   237.3 3050.35   258.4 3054.12   279.6 3053.72   284.3 3054.79
   309.3 3066.08   338.9 3084.81   351.6 3090.65   360.1 3096.42   382.5 3114.51
#Mann= 4 ,-1,0
       0      .1       0   166.4    .045       0   194.9      .1       0
     340     .06       0
Bank Sta=166.4,194.9
XS Rating Curve= 0 ,0
Exp/Cntr=0.3,0.1

Type RM Length L Ch R = 1 ,26357   ,256,264.3,259.1
XS GIS Cut Line= 2
2336269.13534525 638969.005056832336814.55268016638814.480983146
#Sta/Elev= 30
       0  3126.4      53 3112.47    61.4 3111.47    67.1 3108.61    73.8 3107.84
    82.2 3103.49    94.6 3100.06   102.9 3095.33   127.9 3087.06   148.7 3076.36
   194.4 3048.24   215.2 3047.42   223.5  3048.2   244.3 3049.66   281.7 3047.91
   300.4  3050.5   339.2 3049.08   348.2 3051.05     369 3061.39   377.3  3066.9
   397.6 3083.46   420.2 3103.89   423.1 3105.38   443.8 3106.36   468.7 3127.42
   510.4 3150.97   522.8 3160.13   539.5 3162.28   551.9 3174.37   566.9 3183.78
#Mann= 5 ,-1,0
       0      .1       0   194.4    .045       0   223.5      .1       0
     310     .06       0     410      .1       0
#XS Ineff= 2 , 0
                          301.53         3069.15
Permanent Ineff=
       F       F
Bank Sta=194.4,223.5
XS Rating Curve= 0 ,0
Exp/Cntr(USF)=0,0
Exp/Cntr=0.3,0.1

Type RM Length L Ch R = 1 ,26092   ,208.4,206,210.3
XS GIS Cut Line= 2
2336333.46467269639138.7834461452336880.01484712639059.153949269
#Sta/Elev= 30
       0 3097.87      31 3092.92    71.5 3082.89    99.8 3071.38     120 3058.87
   144.9 3046.87   188.7 3047.13   201.4 3046.23   212.9 3047.24   233.2 3046.41
   241.2 3047.51   253.4 3045.22   264.9 3044.71   277.6 3045.25   289.7 3045.37
   301.9 3047.01   322.1  3046.8   330.2 3048.55     339 3052.26   374.6 3077.24
   378.7 3079.21   386.8 3080.51     407 3080.27   423.1 3093.52   459.5 3109.85
   471.6 3116.16   487.2 3122.41     508 3133.12   544.4 3145.32   552.3 3146.55
#Mann= 5 ,-1,0
       0      .1       0   253.4    .045       0   277.6      .1       0
     340     .06       0     440      .1       0
Bank Sta=253.4,277.6
XS Rating Curve= 0 ,0
Exp/Cntr=0.3,0.1

Type RM Length L Ch R = 1 ,25886   ,290.3,296.5,288.1
XS GIS Cut Line= 3
2336280.30285895639369.8736862512336588.68508326639290.942521696
2336895.23169909639278.093262349
#Sta/Elev= 30
       0 3100.27    12.3 3098.24    46.5 3097.64    74.2 3093.49   119.6 3081.94
   173.3 3070.72   193.9 3062.37   206.3 3059.56   210.9 3056.86   218.7 3047.33
   222.8 3043.78   231.1 3041.75   268.2 3044.35   297.2 3043.88   309.5 3045.75
   321.8 3044.25   349.8 3045.42   361.8 3043.94   389.9 3044.73   393.33043.603
   415.6 3043.57   433.9  3047.8   450.2 3049.36   473.9 3055.27     482 3054.42
     502 3057.28     530 3068.02     550 3068.94     570 3065.54   625.1  3078.4
#Mann= 5 ,-1,0
       0      .1       0   393.3    .045       0   415.6      .1       0
  498.32     .06       0  598.32      .1       0
Bank Sta=393.3,415.6
XS Rating Curve= 0 ,0
Exp/Cntr(USF)=0,0
Exp/Cntr=0.3,0.1

Type RM Length L Ch R = 1 ,25590   ,194.7,204,200.1
XS GIS Cut Line= 2
 2336336.5656039639513.5447797082336880.16333287639487.852293952
#Sta/Elev= 30
       0 3086.13    19.6  3083.4    59.7 3072.76    84.1 3067.67    95.6 3063.75
   115.7 3058.53   155.8 3042.61   163.8 3041.47   168.2  3039.8   171.8 3039.22
   215.8 3038.64   235.9 3039.07   247.9 3040.21   259.9 3038.95   279.9 3041.65
   295.9 3040.91   303.9 3041.44   313.5 3040.42   322.8  3039.6   331.3 3040.39
     336 3041.33   344.1 3040.64     356 3042.33   386.2 3042.81   400.1 3044.01
   427.9 3049.17   468.1 3054.04   492.2 3059.39   512.2 3065.08   544.2 3065.95
#Mann= 5 ,-1,0
       0      .1       0   313.5    .045       0   331.3      .1       0
     430     .06       0     530      .1       0
Bank Sta=313.5,331.3
XS Rating Curve= 0 ,0
Exp/Cntr=0.3,0.1

Type RM Length L Ch R = 1 ,25386   ,280.5,283.3,277.7
XS GIS Cut Line= 2
2336312.19235783639653.9074182722336839.53905551639664.154608253
#Sta/Elev= 30
       0 3088.06      12 3085.38      48 3074.34      68 3073.84      80 3071.86
     100 3065.44   113.1  3063.4     136 3057.32     148 3051.12     160 3041.34
   164.1 3039.58     208 3039.96     216 3038.77     232  3039.4     252  3036.8
     268 3036.36   293.6  3036.8     304 3038.69     324 3039.26   371.73037.222
   392.83037.143   400.1  3040.7   408.1 3042.41   436.1 3042.99   460.1 3041.59
   464.1 3042.31   472.1 3048.16   480.1 3051.01   492.1 3052.92   527.4    3055
#Mann= 3 ,-1,0
       0      .1       0   371.7    .045       0   392.8      .1       0
#XS Ineff= 2 , 0
          203.84 3045.53
Permanent Ineff=
       F       F
Bank Sta=371.7,392.8
XS Rating Curve= 0 ,0
Exp/Cntr(USF)=0,0
Exp/Cntr=0.3,0.1

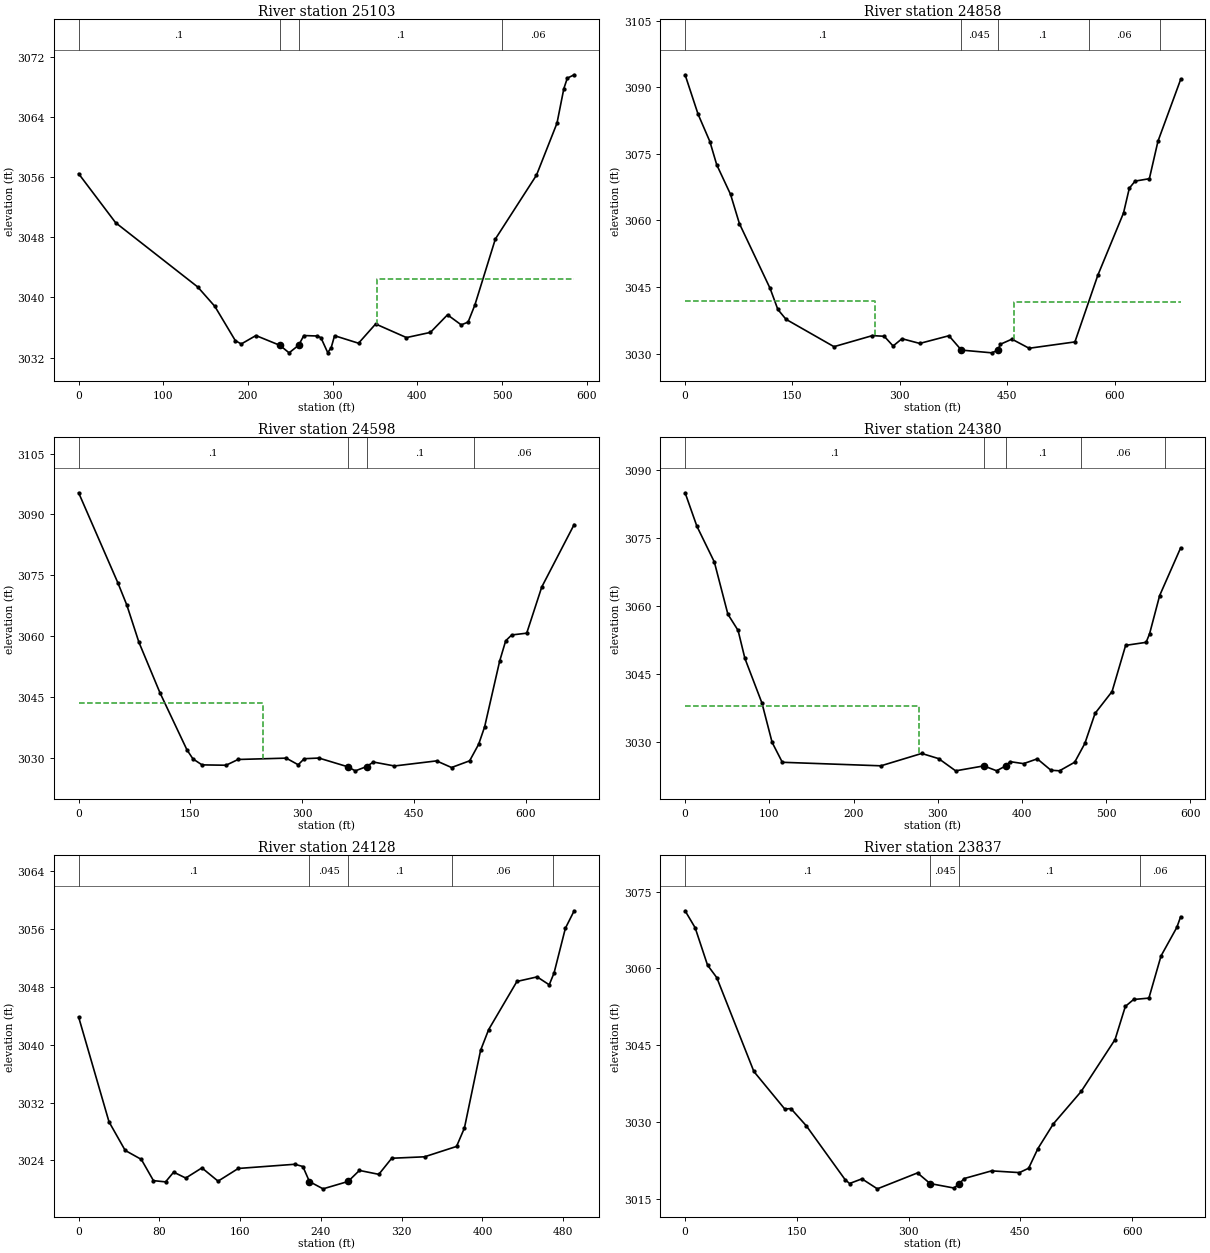
Type RM Length L Ch R = 1 ,25103   ,209.8,244.5,242.9
XS GIS Cut Line= 2
2336368.96628696639927.6390471592336948.21857368639843.764523462
#Sta/Elev= 30
       0 3056.46    43.7 3049.94   140.7 3041.39   160.9 3038.81   185.1 3034.25
   192.1 3033.81   209.4 3034.93   237.7 3033.63   248.6 3032.63   259.93033.649
     266 3034.93   282.1 3034.87   286.2 3034.64   294.2 3032.66   298.3 3033.32
   302.3 3034.91   330.6 3033.91   350.8 3036.47   387.2 3034.66   415.5 3035.35
   435.7 3037.69   451.9 3036.35     460 3036.72     468 3038.99   492.2 3047.77
   540.8 3056.27     565 3063.18   573.1 3067.78   577.2 3069.17   585.3 3069.62
#Mann= 4 ,-1,0
       0      .1       0   237.7    .045       0   259.9      .1       0
     500     .06       0
#XS Ineff= 2 , 0
                           352.4         3042.46
Permanent Ineff=
       F       F
Bank Sta=237.7,259.9
XS Rating Curve= 0 ,0
Exp/Cntr=0.3,0.1

Type RM Length L Ch R = 1 ,24858   ,257.6,259.9,257.3
XS GIS Cut Line= 3
2336314.62548551640128.1505331212336657.27240141 640040.44923917
2336995.84018736640036.370109219
#Sta/Elev= 30
       0 3092.79    18.1 3083.93    34.6 3077.76    44.2 3072.52    63.5 3065.86
    75.9 3059.27   118.8 3044.67   129.6 3039.94     141 3037.73     208 3031.57
   261.7 3034.06   278.2 3033.91   290.6 3031.72     303 3033.36   327.8  3032.3
   368.6 3034.03  385.983030.797   428.6 3030.18   436.6 3030.77   440.6 3032.12
   456.6 3033.26   480.6 3031.21   544.6 3032.64   576.6 3047.65   612.5 3061.67
   620.6 3067.25   628.7 3068.85   648.6 3069.39   660.6 3077.81   692.3 3091.73
#Mann= 5 ,-1,0
       0      .1       0  385.98    .045       0   436.6      .1       0
  563.69     .06       0  663.69      .1       0
#XS Ineff= 2 , 0
          265.52 3041.96  459.41          3041.7
Permanent Ineff=
       F       F
Bank Sta=385.98,436.6
XS Rating Curve= 0 ,0
Exp/Cntr(USF)=0,0
Exp/Cntr=0.3,0.1

Type RM Length L Ch R = 1 ,24598   ,218.6,218.2,218.4
XS GIS Cut Line= 2
2336340.01967196640323.2741281782336999.25059887640235.403957274
#Sta/Elev= 30
       0 3095.35    52.6 3073.19    64.7 3067.68    80.9 3058.53   109.1  3046.1
   145.4    3032   153.5 3029.77   165.6 3028.31   197.9 3028.22     214 3029.64
   278.6 3029.97   294.7 3028.34   302.8 3029.83   322.5 3029.99   360.9 3027.86
   371.4 3026.84   386.6  3027.9   395.6 3029.01   423.9 3028.04   480.4 3029.29
   500.5 3027.66   524.8 3029.31   536.9 3033.39   544.9 3037.67   565.1 3053.89
   573.2 3058.89   581.3 3060.32   601.4 3060.76   621.6 3072.14   665.1 3087.53
#Mann= 4 ,-1,0
       0      .1       0   360.9    .045       0   386.6      .1       0
     530     .06       0
#XS Ineff= 2 , 0
          247.71 3043.52
Permanent Ineff=
       F       F
Bank Sta=360.9,386.6
XS Rating Curve= 0 ,0
Exp/Cntr=0.3,0.1

Type RM Length L Ch R = 1 ,24380   ,250.6,252.2,250.4
XS GIS Cut Line= 2
2336393.79817941640530.581996604 2336976.8871441640452.172054209
#Sta/Elev= 30
       0 3085.07      14 3077.68    34.7 3069.79    50.8 3058.25    62.9 3054.67
      71 3048.49    91.2 3038.65   103.3 3029.95   115.4 3025.55   232.5 3024.77
   280.9  3027.5   301.1 3026.35   321.2 3023.66   354.63024.751   369.8 3023.68
   380.5 3024.73   385.8 3025.69   401.8 3025.25   418.1 3026.31   434.3 3023.79
   444.5 3023.67   462.5 3025.56   474.6 3029.72   486.7 3036.35   506.9 3041.18
     523 3051.37   547.3 3052.04   551.4 3053.91   563.4 3062.38   588.3  3072.9
#Mann= 5 ,-1,0
       0      .1       0   354.6    .045       0   380.5      .1       0
     470     .06       0     570      .1       0
#XS Ineff= 2 , 0
          278.12 3038.03
Permanent Ineff=
       F       F
Bank Sta=354.6,380.5
XS Rating Curve= 0 ,0
Exp/Cntr(USF)=0,0
Exp/Cntr=0.3,0.1

Type RM Length L Ch R = 1 ,24128   ,294.2,290.5,283.2
XS GIS Cut Line= 2
2336494.04901852640704.7947238012336984.80083631   640700.266541
#Sta/Elev= 30
       0 3043.79    30.1 3029.33    46.1 3025.39    62.1 3024.15    74.1 3021.22
    86.1 3021.05    94.1 3022.39   106.1 3021.58   122.1 3022.98   138.1 3021.15
   158.1  3022.9   214.1 3023.48   222.1 3023.17   228.6 3021.09   242.1 3020.09
  266.863021.106   278.1 3022.63   297.3 3022.09   310.1 3024.31   342.6 3024.51
   374.3 3025.94   382.1 3028.48   398.1 3039.19   406.1 3042.06   434.1  3048.7
   454.1 3049.33   466.1 3048.24   470.9 3049.88   482.1 3056.04   490.8 3058.45
#Mann= 5 ,-1,0
       0      .1       0   228.6    .045       0  266.86      .1       0
     370     .06       0     470      .1       0
Bank Sta=228.6,266.86
XS Rating Curve= 0 ,0
Exp/Cntr=0.3,0.1

Type RM Length L Ch R = 1 ,23837   ,237.1,234.5,228.8
XS GIS Cut Line= 2
2336375.11162813641043.2934548132337017.05399227640869.837598648
#Sta/Elev= 30
       0 3071.24    13.5 3067.92    30.1 3060.63    42.5 3058.19    92.3 3039.86
   133.7 3032.54     142 3032.62   162.7 3029.25   214.6 3018.77   220.7 3017.99
   237.3  3018.9     258 3016.95   311.9 3020.06   328.8 3017.98   360.8 3017.11
   367.9 3017.94   374.5 3018.96   411.3 3020.46   448.6 3020.12     461 3020.97
   473.5 3024.82   494.2 3029.64   531.5 3035.96     577  3046.1   590.8 3052.57
   601.9 3053.92   622.4 3054.19   638.7 3062.43   659.9    3068     665 3070.08
#Mann= 4 ,-1,0
       0      .1       0   328.8    .045       0   367.9      .1       0
     610     .06       0
Bank Sta=328.8,367.9
XS Rating Curve= 0 ,0
Exp/Cntr(USF)=0,0
Exp/Cntr=0.3,0.1

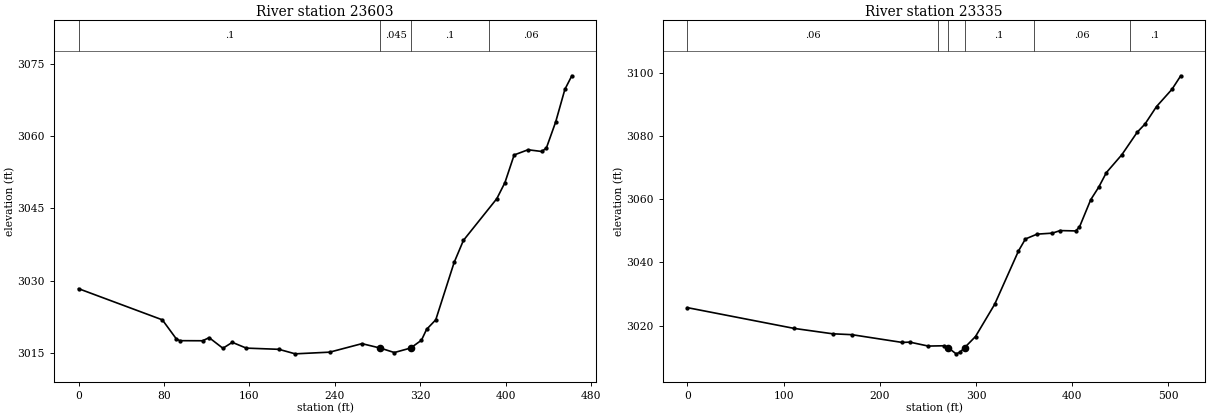
Type RM Length L Ch R = 1 ,23603   ,260.5,267.5,272.7
XS GIS Cut Line= 3
2336604.26294421 641226.309385242336782.74221363641148.233228814
2337030.22549823641047.712686441
#Sta/Elev= 30
       0 3028.31    78.5 3021.82    91.6 3017.85    94.9 3017.49   116.2 3017.47
   122.3 3018.12   135.2 3015.91     144 3017.14   157.1 3015.94   187.6 3015.69
   202.9 3014.75   235.2  3015.1   265.4 3016.87   282.7 3015.94   295.7 3015.02
  310.973015.958   321.1 3017.58   325.9 3019.84   334.5 3021.83   351.7 3033.76
   360.4 3038.35   391.7 3047.04   399.3 3050.39   407.9 3056.12   420.9  3057.2
   433.8 3056.84   438.1 3057.58   446.8    3063   455.4 3069.77   461.9 3072.59
#Mann= 4 ,-1,0
       0      .1       0   282.7    .045       0  310.97      .1       0
  384.81     .06       0
Bank Sta=282.7,310.97
XS Rating Curve= 0 ,0
Exp/Cntr=0.3,0.1

Type RM Length L Ch R = 1 ,23335   ,69.9,69.4,69.4
XS GIS Cut Line= 2
2336601.55270572641353.0131530472337113.24035313641387.790908539
#Sta/Elev= 30
       0 3025.67   110.9  3019.1     151 3017.39     171 3017.11   223.1 3014.66
   231.2 3014.75   250.4  3013.5   267.2  3013.6   271.2 3012.97   279.3 3011.04
   283.3 3011.54  288.273013.034   299.5 3016.53   319.4 3026.72   344.2 3043.64
   351.4 3047.43   363.5 3048.96   379.5 3049.28   387.5 3050.09   403.6 3049.98
   407.6 3051.22   419.3 3059.87   427.6 3063.84   435.6 3068.47   451.7 3074.14
   467.7 3081.28   475.7 3083.83   487.7 3089.38   503.8 3094.86   512.9 3099.13
#Mann= 6 ,-1,0
       0     .06       0     260      .1       0   271.2    .045       0
  288.27      .1       0     360     .06       0     460      .1       0
Bank Sta=271.2,288.27
XS Rating Curve= 0 ,0
Exp/Cntr(USF)=0,0
Exp/Cntr=0.3,0.1