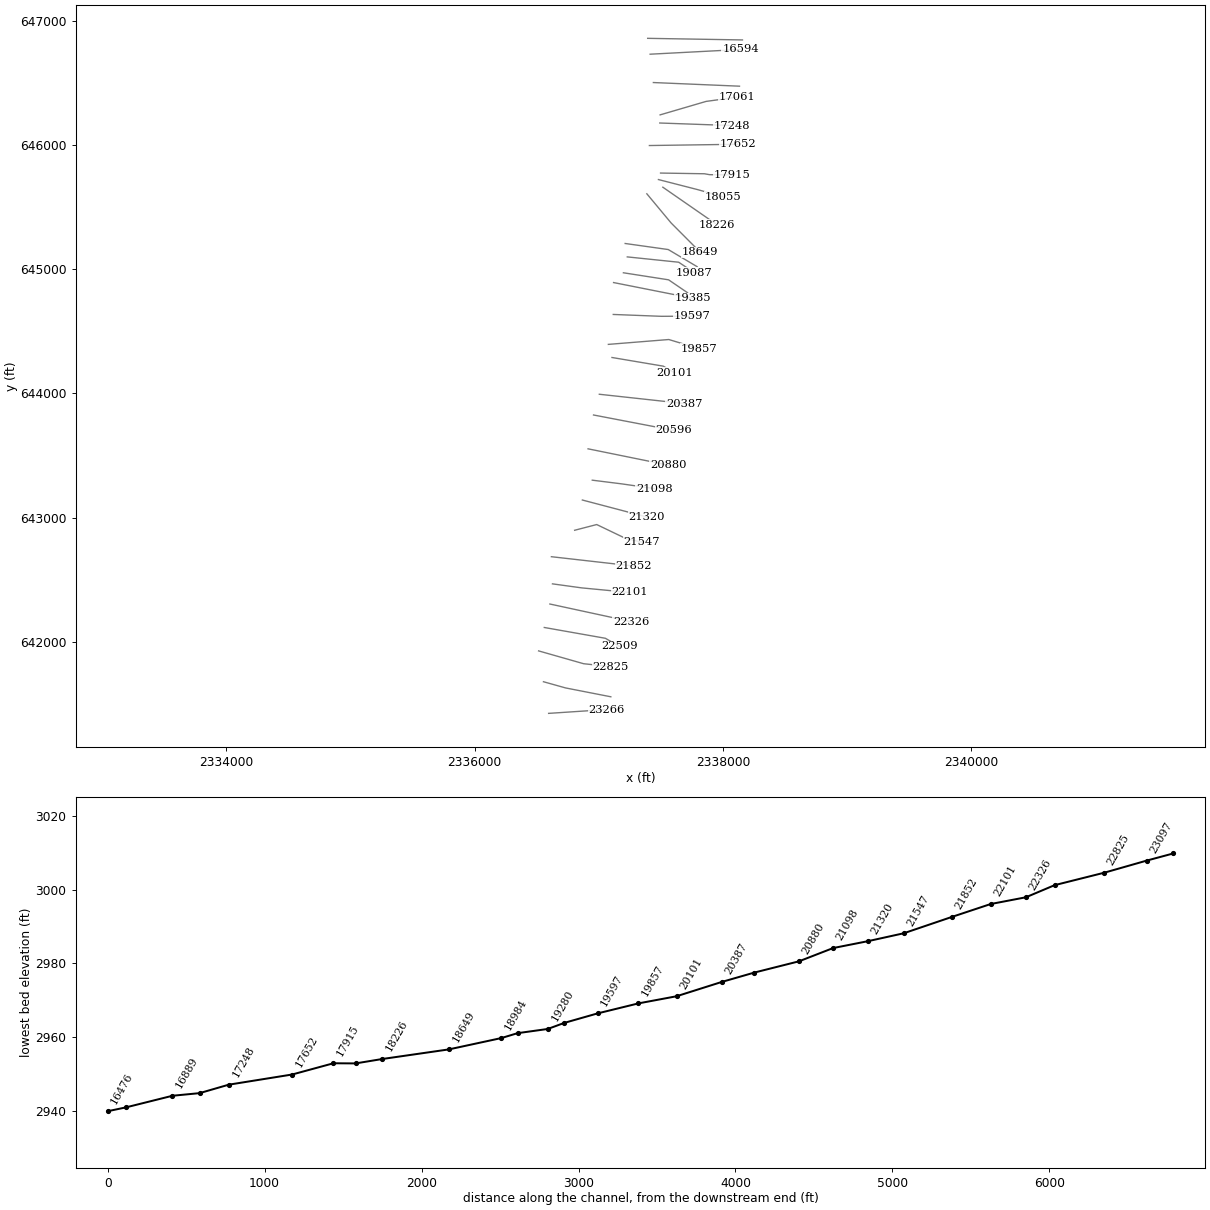
HEC-RAS study EFKGLADYFK.prj: EFKGLADYFK

--- EFKGLADYFK.g01 (geometry) --- (continued)

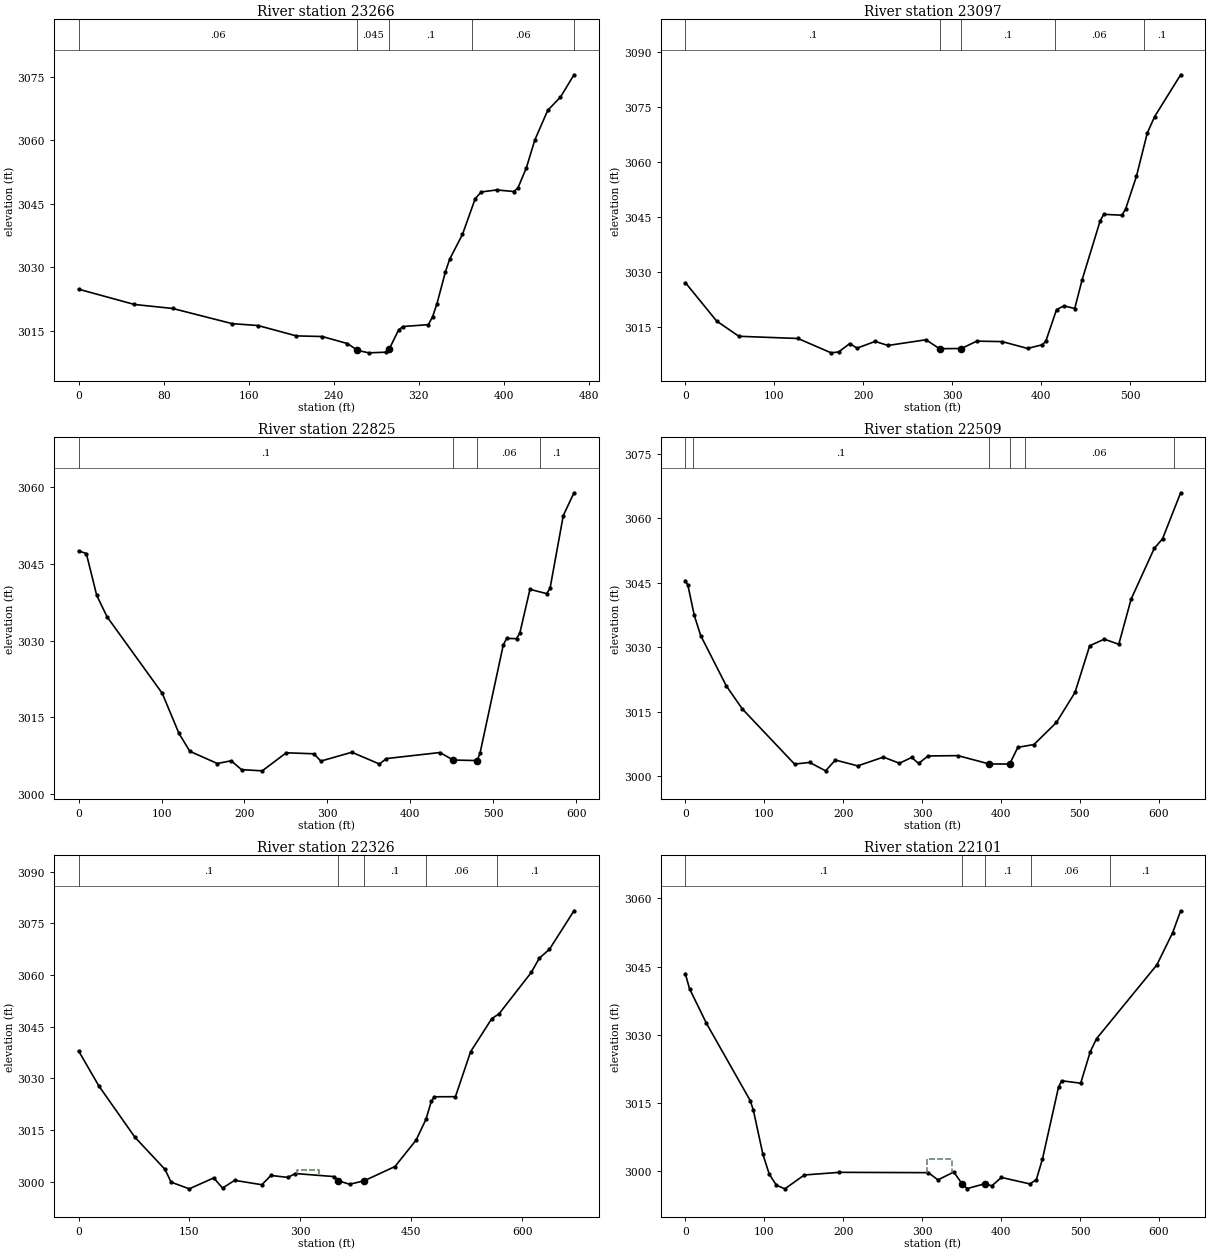
Type RM Length L Ch R = 1 ,23266   ,172,169.4,166.4
XS GIS Cut Line= 2
2336595.87105403641422.4731060522337060.82300628641453.221431551
#Sta/Elev= 30
       0 3024.86    52.4 3021.26    88.5 3020.31   144.6 3016.72   168.7 3016.29
   204.8 3013.84   229.2 3013.69   252.9 3012.03   262.3 3010.43   272.9 3009.84
   288.9 3009.99   292.4 3010.84     301 3015.23     305 3016.05     329 3016.49
     333 3018.38     337 3021.35   345.1    3029   349.1 3031.98   361.1  3037.8
   373.1 3046.25   378.8 3047.81   393.2 3048.29   409.2 3047.92   413.2 3048.72
   421.2 3053.51   429.2 3060.11   441.3 3067.08   453.3 3070.21     466 3075.47
#Mann= 5 ,-1,0
       0     .06       0   262.3    .045       0   292.4      .1       0
     370     .06       0  465.97      .1       0
Bank Sta=262.3,292.4
XS Rating Curve= 0 ,0
Exp/Cntr(USF)=0,0
Exp/Cntr=0.3,0.1

Type RM Length L Ch R = 1 ,23097   ,267.6,271.5,271.4
XS GIS Cut Line= 3
2336554.23693815641677.4035142452336732.53149132641627.407779708
 2337096.9367679641556.140248782
#Sta/Elev= 30
       0 3027.06    35.2 3016.57    60.2 3012.41   126.6 3011.81   163.8  3007.9
   172.3 3008.14   184.8 3010.43     193 3009.18   213.3 3011.01   227.7 3009.91
   270.4 3011.46   285.6 3009.03   310.2 3009.08   327.5 3011.09     356 3010.96
   384.5  3009.1   400.8 3010.08   404.9 3010.99   417.1 3019.69   425.4  3020.7
   437.5 3019.98   445.9 3027.87     466  3043.8   470.1 3045.64   490.5  3045.4
   494.6 3047.03   506.8 3055.96     519 3067.77   527.2 3072.24   556.5 3083.66
#Mann= 5 ,-1,0
       0      .1       0   285.6    .045       0   310.2      .1       0
  415.17     .06       0  515.17      .1       0
Bank Sta=285.6,310.2
XS Rating Curve= 0 ,0
Exp/Cntr=0.3,0.1

Type RM Length L Ch R = 1 ,22825   ,311.3,316.4,312.1
XS GIS Cut Line= 3
2336515.22338387641925.7578375972336877.81271286641822.520598091
2337096.92745876 641799.02783115
#Sta/Elev= 30
       0 3047.48     9.3 3046.94    21.8 3038.81    34.3 3034.62   100.8 3019.72
     121  3011.9   134.1 3008.41   167.3 3006.03     184 3006.56   196.5 3004.83
   221.5  3004.6   250.4 3008.12   283.8 3007.92   292.1  3006.5   329.5 3008.22
   362.8 3005.93   371.1 3006.99   435.7 3008.17   451.8  3006.7   480.53006.604
     484 3007.98   512.1 3029.11   516.2 3030.41   528.2 3030.36   532.2 3031.53
   544.3 3039.97   564.4 3039.14   568.5 3040.15   584.5 3054.36   597.4 3058.79
#Mann= 4 ,-1,0
       0      .1       0   451.8    .045       0   480.5     .06       0
     557      .1       0
Bank Sta=451.8,480.5
XS Rating Curve= 0 ,0
Exp/Cntr(USF)=0,0
Exp/Cntr=0.3,0.1

Type RM Length L Ch R = 1 ,22509   ,182.9,182.9,180.9
XS GIS Cut Line= 3
2336560.94451712642114.4066294162337053.02795907642027.411532251
2337164.04290455641963.342237155
#Sta/Elev= 30
       0 3045.53     3.3 3044.46    11.4 3037.44    19.5 3032.74      52 3021.01
    72.3 3015.64   138.5 3002.79   157.6 3003.18   177.9 3001.22   190.2 3003.74
   218.6 3002.38   251.1 3004.42   271.4 3002.99   286.9 3004.33   295.7 3002.96
   307.9 3004.69   345.6 3004.76   385.1 3002.83   411.2  3002.8   421.5 3006.69
     442 3007.35   470.4 3012.48     494 3019.48   512.6 3030.36   531.1 3031.89
   549.5  3030.7   565.1 3041.21   594.4 3053.02     605  3055.3   627.9 3065.99
#Mann= 6 ,-1,0
       0     .06       0      10      .1       0   385.1    .045       0
   411.2      .1       0     430     .06       0  619.71      .1       0
Bank Sta=385.1,411.2
XS Rating Curve= 0 ,0
Exp/Cntr=0.3,0.1

Type RM Length L Ch R = 1 ,22326   ,219.5,224.3,223.2
XS GIS Cut Line= 3
2336605.87071612642303.4550553012337129.19439351642190.289361524
2337260.54589347642159.930112573
#Sta/Elev= 30
       0 3037.96    27.4 3027.81      76 3012.96   116.9 3003.57   125.1 2999.87
   149.7 2997.93   182.8  3001.1   194.7 2998.15   211.1  3000.4   247.9 2999.12
   260.2 3001.82   283.1 3001.25   293.2 3002.37   346.1 3001.48   351.4 3000.28
   366.6 2999.26   386.4 3000.27     428 3004.41   456.6 3012.09     470 3018.16
   477.1  3023.3   481.2 3024.66   509.8 3024.69   530.3 3037.74     559 3047.37
   568.8 3048.75   612.4 3060.77   623.3 3064.93     637 3067.49   670.2 3078.68
#Mann= 5 ,-1,0
       0      .1       0   351.4    .045       0   386.4      .1       0
     470     .06       0  565.42      .1       0
#XS Ineff= 1 ,-1
  295.09  325.653003.314
Permanent Ineff=
       F
Bank Sta=351.4,386.4
XS Rating Curve= 0 ,0
Exp/Cntr(USF)=0,0
Exp/Cntr=0.3,0.1

Type RM Length L Ch R = 1 ,22101   ,246.2,249.2,247.9
XS GIS Cut Line= 3
2336626.78272898642465.8501751222336862.61097151642433.410824878
2337250.18211258642396.276915219
#Sta/Elev= 30
       0 3043.46     5.4 3040.13    26.7 3032.55    82.2 3015.53    86.2 3013.43
    98.3  3003.7   106.4 2999.31   115.4  2996.9   126.1  2996.1   150.8 2999.15
   195.2 2999.73   307.9 2999.66     320 2998.07   340.1  2999.8   350.6 2997.19
     357 2996.16     379  2997.2   388.3 2996.77   400.4 2998.61   436.5 2997.18
   444.6 2998.11   452.4 3002.67   472.7 3018.46   476.7 3019.88   500.8 3019.34
   512.9 3026.26   520.9 3029.15   597.3 3045.38   617.3 3052.47   627.4 3057.28
#Mann= 5 ,-1,0
       0      .1       0   350.6    .045       0     379      .1       0
  438.05     .06       0  538.05      .1       0
#XS Ineff= 1 ,-1
  306.27  337.93 3002.58
Permanent Ineff=
       F
Bank Sta=350.6,379
XS Rating Curve= 0 ,0
Exp/Cntr=0.3,0.1

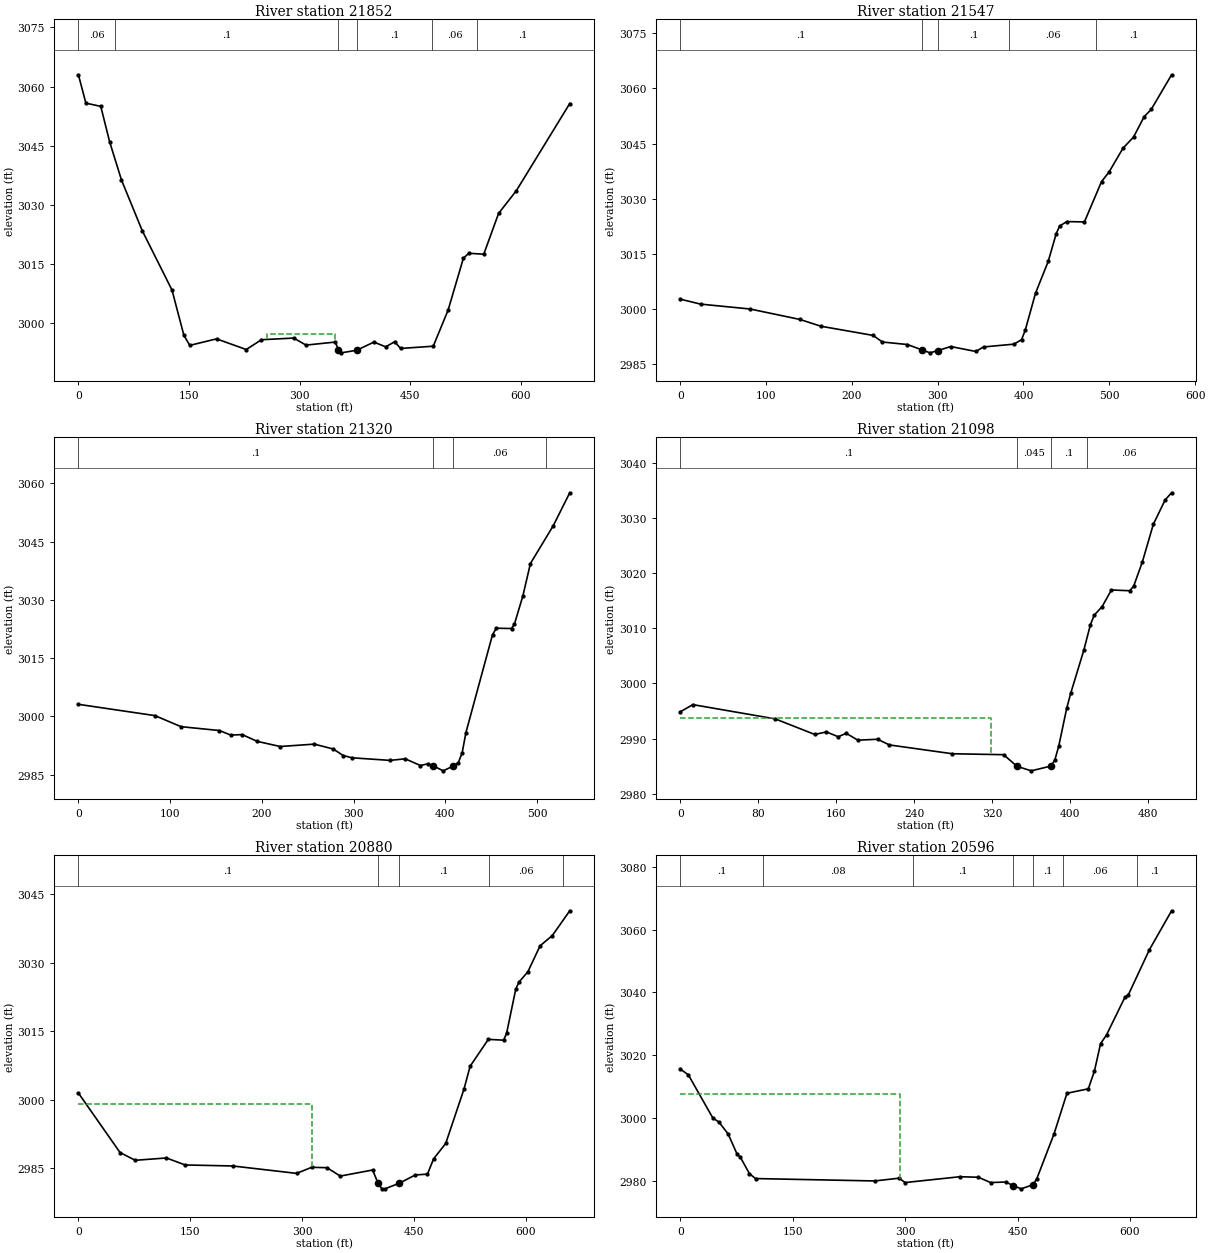
Type RM Length L Ch R = 1 ,21852   ,307.3,304.8,301.9
XS GIS Cut Line= 2
 2336618.1111804642684.5630320632337280.02283078642609.527324194
#Sta/Elev= 30
       0 3062.97    10.1 3055.79    30.3 3054.97    42.3 3046.02    58.4 3036.31
    86.6 3023.47   126.9 3008.46     143    2997     151 2994.46   187.3 2996.11
   227.5 2993.41   248.2 2995.89   291.9 2996.31   308.6 2994.53   348.3  2995.3
   352.6 2993.32   356.3 2992.57   377.3 2993.22   400.6 2995.29   416.7 2994.09
   428.8 2995.39   436.8 2993.68   481.1 2994.25   501.3 3003.41     522 3016.54
   529.4 3017.78   549.6 3017.54   569.7 3027.87   593.8 3033.63   666.2 3055.69
#Mann= 6 ,-1,0
       0     .06       0      50      .1       0   352.6    .045       0
   377.3      .1       0     480     .06       0     540      .1       0
#XS Ineff= 1 ,-1
  255.35  348.322997.234
Permanent Ineff=
       F
Bank Sta=352.6,377.3
XS Rating Curve= 0 ,0
Exp/Cntr(USF)=0,0
Exp/Cntr=0.3,0.1

Type RM Length L Ch R = 1 ,21547   ,226.4,227.6,232.3
XS GIS Cut Line= 4
2336805.37522118 642897.584496622336983.11672027642943.673146159
2337217.82928917642831.0572581092337343.33748446 642802.88050106
#Sta/Elev= 30
       0 3002.75    23.6  3001.4    81.4 3000.07   139.3 2997.24   164.1 2995.38
   224.7  2992.9   235.6  2991.1   264.7 2990.42   281.42988.989   291.1 2988.16
   300.1 2988.77   315.2 2989.87   344.5 2988.53   353.4 2989.76   388.9 2990.52
   397.8 2991.75   402.1 2994.37   414.1 3004.42   428.8 3012.99   438.1 3020.51
   442.1 3022.62   450.5 3023.82     471 3023.73     491 3034.71   499.6 3037.25
     516 3043.77   528.3 3046.79   540.6 3052.33   548.8 3054.28   572.6 3063.71
#Mann= 5 ,-1,0
       0      .1       0   281.4    .045       0   300.1      .1       0
  383.62     .06       0  483.95      .1       0
Bank Sta=281.4,300.1
XS Rating Curve= 0 ,0
Exp/Cntr=0.3,0.1

Type RM Length L Ch R = 1 ,21320   ,220.9,222.1,224.8
XS GIS Cut Line= 2
2336867.56826673643141.2613901062337385.63813083643004.915385176
#Sta/Elev= 30
       0 3003.13    83.4 3000.23   111.9 2997.38   153.7 2996.39   166.1 2995.22
   178.5 2995.34     195  2993.6     220 2992.28   257.1 2992.89   277.8 2991.64
   288.7 2989.96   298.5 2989.37   339.8 2988.71   356.3 2989.11   372.9 2987.39
   381.2 2987.84   386.9  2987.3   397.7 2986.02   408.9 2987.28   414.2 2988.12
   418.4 2990.66   422.5 2995.87   451.5 3021.06   455.7 3022.71   472.2 3022.63
   475.4 3023.78   484.6 3031.03   492.8 3039.34   517.7 3049.07   535.7 3057.55
#Mann= 4 ,-1,0
       0      .1       0   386.9    .045       0   408.9     .06       0
     510      .1       0
Bank Sta=386.9,408.9
XS Rating Curve= 0 ,0
Exp/Cntr(USF)=0,0
Exp/Cntr=0.3,0.1

Type RM Length L Ch R = 1 ,21098   ,218.6,217.7,217.4
XS GIS Cut Line= 3
2336947.38768325643301.0943965262337182.68909979643271.631476303
2337446.66363661643233.777760064
#Sta/Elev= 30
       0 2994.86    12.9 2996.16    97.5 2993.57   137.9 2990.75   149.9 2991.21
     162 2990.33   170.1 2990.96   182.2 2989.71   202.4 2989.88   214.4 2988.85
     279 2987.25   331.6 2987.08   345.22984.975   359.9 2984.15   380.1 2985.02
   384.1 2986.11   388.2 2988.72   396.2 2995.46   400.3 2998.19   413.8 3006.03
   420.5 3010.62   424.4 3012.38   432.6 3013.95   442.1 3016.96   460.9 3016.82
   464.9 3017.64   473.9 3022.09   485.1 3028.89   497.3 3033.33   503.8 3034.59
#Mann= 4 ,-1,0
       0      .1       0   345.2    .045       0   380.1      .1       0
  417.14     .06       0
#XS Ineff= 2 , 0
          318.49 2993.79
Permanent Ineff=
       F       F
Bank Sta=345.2,380.1
XS Rating Curve= 0 ,0
Exp/Cntr=0.3,0.1

Type RM Length L Ch R = 1 ,20880   ,284.1,284,284.1
XS GIS Cut Line= 2
2336913.53998399643553.6789277792337559.17560793643422.466914349
#Sta/Elev= 30
       0 3001.49    55.8 2988.49    76.2 2986.79     118  2987.3   143.1 2985.77
   206.8 2985.55   292.5 2983.93   312.9 2985.26   333.3 2985.17   351.1 2983.34
   394.5 2984.67   401.72981.783   406.8 2980.58   410.9 2980.55   430.1 2981.77
   451.7 2983.58     468 2983.77   476.2 2987.09   492.5 2990.48     517 3002.36
   525.2 3007.35   549.6 3013.23   570.1 3013.05   574.1 3014.55   586.4  3024.2
   590.5  3025.7   602.7 3028.02     619 3033.68   635.4 3035.92   658.8 3041.34
#Mann= 5 ,-1,0
       0      .1       0   401.7    .045       0   430.1      .1       0
     550     .06       0     650      .1       0
#XS Ineff= 2 , 0
             313 2999.17
Permanent Ineff=
       F       F
Bank Sta=401.7,430.1
XS Rating Curve= 0 ,0
Exp/Cntr(USF)=0,0
Exp/Cntr=0.3,0.1

Type RM Length L Ch R = 1 ,20596   ,207.6,208.8,210.1
XS GIS Cut Line= 2
     2336957.541      643826.2622337601.34937805643702.775214732
#Sta/Elev= 30
       0 3015.63    10.8 3013.77    43.4 3000.07    51.6 2998.74    63.8 2994.99
      76 2988.44    80.1 2987.61    92.3 2982.32   100.4 2980.77   259.5 2980.01
   291.9 2980.89     300  2979.5   373.3 2981.36   397.8 2981.18     414  2979.5
   434.4 2979.67     444 2978.55   454.8  2977.5   470.6 2978.81   475.7 2980.73
   498.7    2995   515.9 3007.91   544.4 3009.33   552.5 3014.91   560.7 3023.66
   568.8 3026.53   593.3 3038.51   597.8 3039.23   625.8 3053.54   655.5 3065.98
#Mann= 7 ,-1,0
       0      .1       0     110     .08       0     310      .1       0
     444    .045       0   470.6      .1       0     510     .06       0
     610      .1       0
#XS Ineff= 2 , 0
          293.22 3007.64
Permanent Ineff=
       F       F
Bank Sta=444,470.6
XS Rating Curve= 0 ,0
Exp/Cntr=0.3,0.1

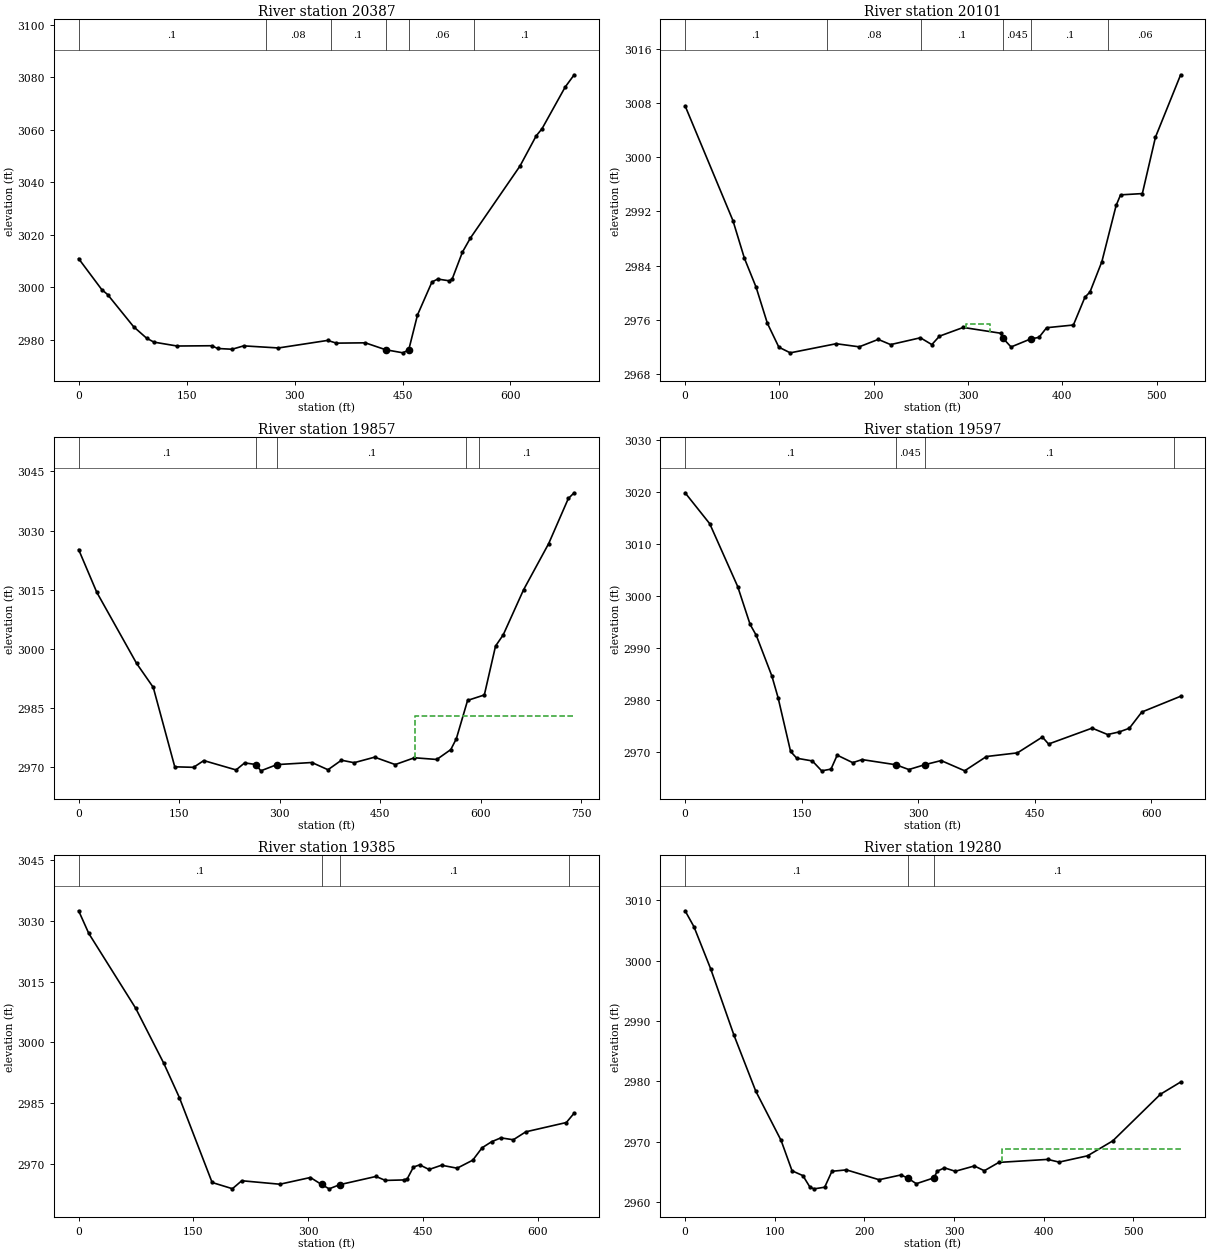
Type RM Length L Ch R = 1 ,20387   ,287.9,286.8,286.4
XS GIS Cut Line= 2
2337004.18731624643993.3184891862337688.57467472643918.534440081
#Sta/Elev= 30
       0 3010.87    32.2 2999.04    40.2 2997.19    76.4  2984.9    94.4 2980.54
   104.6 2979.03   136.8 2977.54   185.1 2977.65   193.1  2976.6   213.2 2976.31
   229.3  2977.6   277.6  2976.8     346 2979.68   358.1 2978.64   398.3 2978.76
   426.5 2976.13   450.7 2974.94   458.7 2976.15   470.8 2989.38   490.9 3001.96
   498.9 3003.08     515 3002.41   519.1 3003.15   533.3 3013.39   544.2 3018.67
   613.2 3046.18   635.7 3057.68   643.8  3060.4     676 3076.31   688.5 3080.99
#Mann= 6 ,-1,0
       0      .1       0     260     .08       0     350      .1       0
   426.5    .045       0   458.7     .06       0     550      .1       0
Bank Sta=426.5,458.7
XS Rating Curve= 0 ,0
Exp/Cntr(USF)=0,0
Exp/Cntr=0.3,0.1

Type RM Length L Ch R = 1 ,20101   ,232.1,243.3,239.2
XS GIS Cut Line= 3
2337106.18462624644289.4318939452337519.13039988644219.761418813
 2337611.2627788644166.045412476
#Sta/Elev= 30
       0 3007.64    50.7 2990.66    62.9 2985.07    75.3 2980.78    87.2 2975.46
    99.4 2971.91   111.5 2971.07   160.2 2972.42   184.6 2971.96   204.8 2973.06
   217.9 2972.29   249.5  2973.3   261.6 2972.29   269.7 2973.54   294.9 2974.83
   334.7 2973.97   336.62973.299   345.6 2971.94   366.4 2973.13   375.2 2973.36
   383.3 2974.79   411.7 2975.19   423.9  2979.3   429.3 2980.08   441.9 2984.58
     457 2992.89   461.7 2994.46   484.8 2994.65   498.7    3003   525.4 3012.24
#Mann= 6 ,-1,0
       0      .1       0     150     .08       0     250      .1       0
   336.6    .045       0   366.4      .1       0  448.78     .06       0
#XS Ineff= 1 ,-1
  298.05  322.76  2975.4
Permanent Ineff=
       F
Bank Sta=336.6,366.4
XS Rating Curve= 0 ,0
Exp/Cntr=0.3,0.1

Type RM Length L Ch R = 1 ,19857   ,252.8,260.4,252.4
XS GIS Cut Line= 3
2337077.14006273644395.0847754672337563.94980999644434.253375822
2337804.55692646644361.511689449
#Sta/Elev= 30
       0 3025.18    27.1 3014.35    86.5 2996.35   111.4 2990.27   143.5 2970.15
   171.6 2970.02   186.8 2971.73     235 2969.36   247.8 2971.14   264.7 2970.73
   271.9 2969.13     296 2970.71   348.2 2971.24   372.2 2969.41   392.3 2971.82
   411.2 2971.19   441.8 2972.59   472.6 2970.72   501.2 2972.44   534.6 2972.01
   555.5 2974.51   563.8 2977.26   580.6 2986.97   605.6 2988.35   622.3 3000.72
   633.8 3003.58   664.1 3014.97   701.7 3026.71     731 3038.12   739.7 3039.56
#Mann= 5 ,-1,0
       0      .1       0   264.7    .045       0     296      .1       0
  578.38     .06       0  598.38      .1       0
#XS Ineff= 2 , 0
                          502.43         2983.02
Permanent Ineff=
       F       F
Bank Sta=264.7,296
XS Rating Curve= 0 ,0
Exp/Cntr(USF)=0,0
Exp/Cntr=0.3,0.1

Type RM Length L Ch R = 1 ,19597   ,214.7,211.7,208.7
XS GIS Cut Line= 3
2337116.52458209644636.1391831452337505.79707508644621.150314555
2337754.10707048644622.550713612
#Sta/Elev= 30
       0  3019.8    31.7 3013.86    67.7  3001.8    83.7 2994.52    91.7  2992.4
   111.7 2984.62   119.7 2980.46   135.8 2970.13   143.8 2968.83   163.8 2968.31
   175.8 2966.41   187.8 2966.74   195.8 2969.42   215.8 2967.98   227.8 2968.57
   271.3 2967.58     288 2966.66   308.8  2967.6   329.6 2968.38   359.9 2966.42
   387.9 2969.16   427.8 2969.86   459.9  2972.9   467.9 2971.56   523.9 2974.61
   543.9 2973.38     559 2973.89   571.9 2974.59   587.9  2977.7   637.9 2980.73
#Mann= 4 ,-1,0
       0      .1       0   271.3    .045       0   308.8      .1       0
  629.56     .06       0
Bank Sta=271.3,308.8
XS Rating Curve= 0 ,0
Exp/Cntr=0.3,0.1

Type RM Length L Ch R = 1 ,19385   ,104.1,105.3,105.2
XS GIS Cut Line= 2
2337119.10642025644893.0855514032337754.19729743644767.186478835
#Sta/Elev= 30
       0 3032.51    13.3  3026.9    74.5 3008.45   111.2 2994.86   131.6 2986.39
   174.4 2965.41   200.9 2963.87   213.1 2965.84   262.9 2964.98   302.8 2966.64
   317.3 2964.92   327.3 2963.84   341.1 2964.87   388.5  2966.9   400.7 2965.92
   425.2 2966.04   429.3 2966.31   437.4 2969.22   445.6 2969.76   457.8 2968.62
   474.1 2969.67   494.5 2968.94   514.9 2970.92   527.1 2973.98   539.4 2975.46
   551.6 2976.43   567.9 2975.96   584.2 2977.92   637.2 2980.22   647.4 2982.54
#Mann= 4 ,-1,0
       0      .1       0   317.3    .045       0   341.1      .1       0
     640     .06       0
Bank Sta=317.3,341.1
XS Rating Curve= 0 ,0
Exp/Cntr(USF)=0,0
Exp/Cntr=0.3,0.1

Type RM Length L Ch R = 1 ,19280   ,189.1,192.4,185.2
XS GIS Cut Line= 3
2337198.34591227644971.8963209152337562.33284683644915.150028222
2337714.73717578644811.385378725
#Sta/Elev= 30
       0 3008.27     9.9 3005.62    28.5 2998.66    54.5 2987.66    78.8 2978.39
   107.1 2970.21   119.3 2965.18   131.4 2964.38   139.5 2962.42   144.1 2962.19
   155.7 2962.46   163.8  2965.1     180 2965.33   216.4  2963.7   240.7 2964.49
   248.3 2963.99   257.9 2963.04  277.672964.015   281.2 2965.11   289.3 2965.67
   301.4  2965.1   322.7 2965.98   333.8 2965.19     350 2966.57   404.5 2967.07
   417.2 2966.62   448.9 2967.66   477.1 2970.14   530.3 2977.87   552.8 2979.89
#Mann= 3 ,-1,0
       0      .1       0   248.3    .045       0  277.67      .1       0
#XS Ineff= 2 , 0
                          353.28         2968.83
Permanent Ineff=
       F       F
Bank Sta=248.3,277.67
XS Rating Curve= 0 ,0
Exp/Cntr(USF)=0,0
Exp/Cntr=0.3,0.1

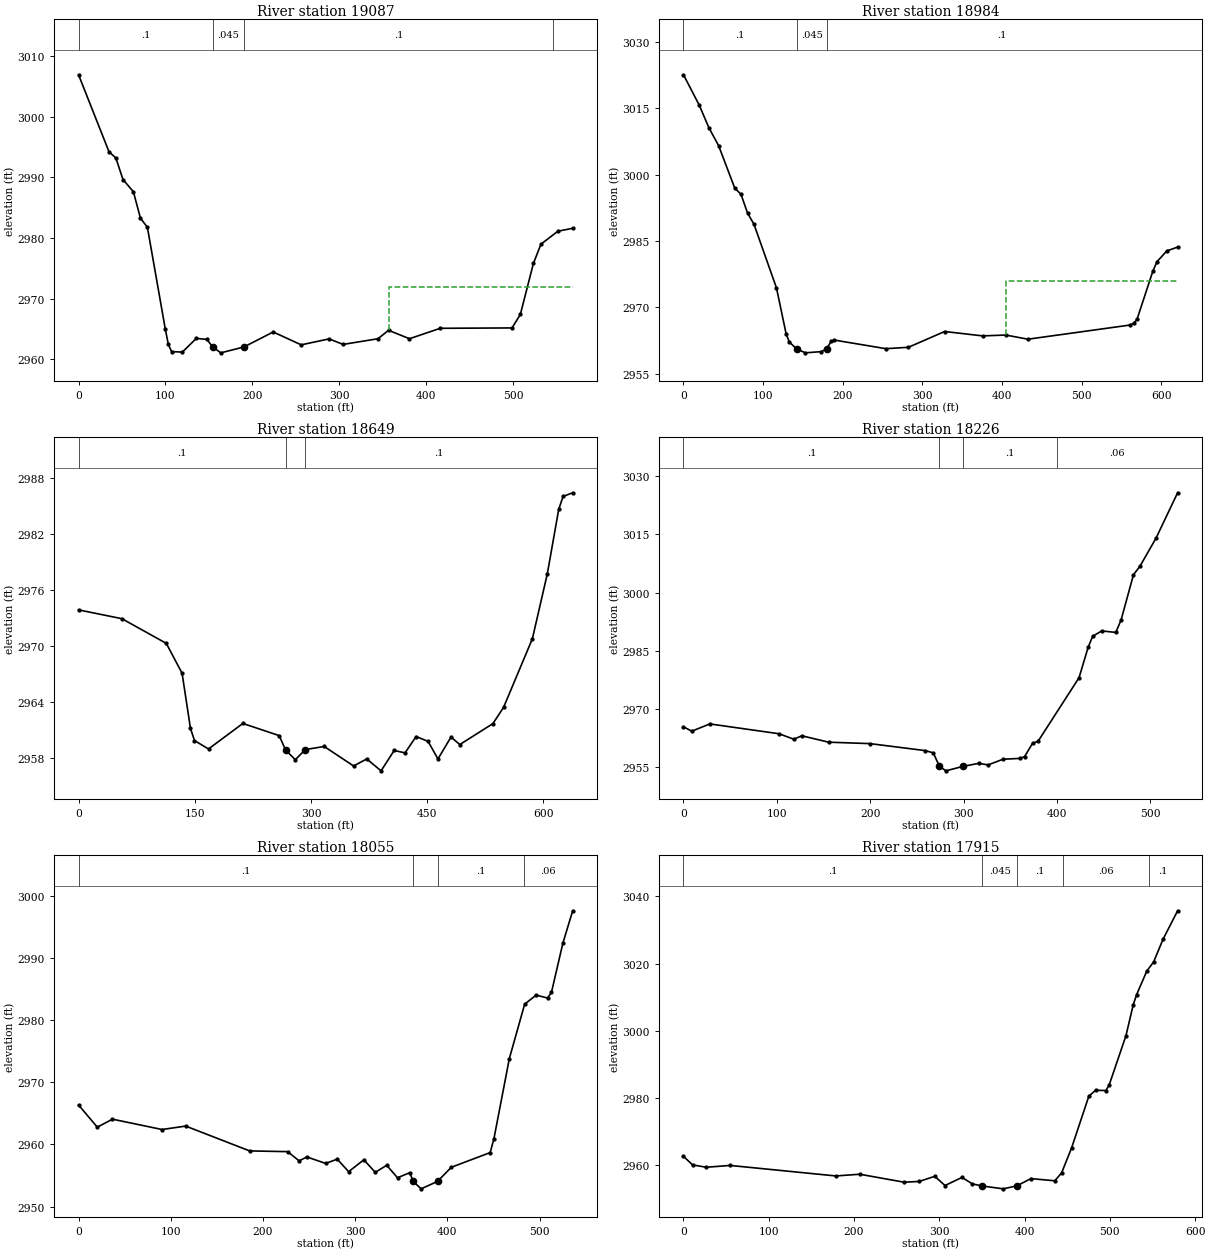
Type RM Length L Ch R = 1 ,19087   ,109.9,103.5,108
XS GIS Cut Line= 3
2337229.38374288645099.8590847972337643.39897925645057.015759955
2337770.29981628644972.737896045
#Sta/Elev= 30
       0 3006.93      35 2994.24      43 2993.18    51.1 2989.65    63.1 2987.63
    71.2 2983.27    79.2 2981.77    99.7 2965.06   103.3 2962.44     107 2961.26
   119.4 2961.17   135.5 2963.43   147.6 2963.27   154.4 2962.01   163.7 2961.05
   190.22962.015     224 2964.49   256.2 2962.37   288.3 2963.35   304.4 2962.44
   344.6 2963.38   356.7 2964.77   380.8 2963.38   416.2  2965.1   498.8 2965.16
   508.4  2967.4   523.4 2975.81   532.1 2978.98   551.6 2981.12   568.6  2981.6
#Mann= 4 ,-1,0
       0      .1       0   154.4    .045       0   190.2      .1       0
  546.23     .06       0
#XS Ineff= 2 , 0
                          356.81         2971.93
Permanent Ineff=
       F       F
Bank Sta=154.4,190.2
XS Rating Curve= 0 ,0
Exp/Cntr=0.3,0.1

Type RM Length L Ch R = 1 ,18984   ,346.5,334.7,322.4
XS GIS Cut Line= 3
 2337212.5380971 645207.851414312337559.41846129645159.117168929
2337791.87267883645021.259816055
#Sta/Elev= 30
       0 3022.54    19.8 3015.68    31.9 3010.57    44.1 3006.54    64.3 2996.97
    72.3 2995.51    80.4 2991.32    88.5 2988.78   116.8 2974.38   128.9    2964
   132.9 2962.15   142.1 2960.62   153.1 2959.72   173.3    2960   179.7 2960.64
   185.4  2962.3   189.5  2962.6   254.1 2960.66   282.4 2960.97   327.9 2964.54
   375.6 2963.55   404.8 2963.74   432.5  2962.8   560.4 2965.99   565.8  2966.4
   569.7 2967.39   589.3 2978.12   594.6 2980.32   606.9 2982.74   620.5 2983.61
#Mann= 3 ,-1,0
       0      .1       0   142.1    .045       0   179.7      .1       0
#XS Ineff= 2 , 0
                           405.2         2975.93
Permanent Ineff=
       F       F
Bank Sta=142.1,179.7
XS Rating Curve= 0 ,0
Exp/Cntr(USF)=0,0
Exp/Cntr=0.3,0.1

Type RM Length L Ch R = 1 ,18649   ,421.7,423.3,425.2
XS GIS Cut Line= 3
2337387.07030049645608.1798276832337582.71926375645373.017409864
2337816.90668974645137.985026975
#Sta/Elev= 30
       0 2973.86    55.9 2972.92   113.2 2970.28   133.6 2967.08   144.4 2961.19
   149.6 2959.88   167.7 2958.98     212 2961.71   258.9 2960.41   267.1 2958.88
   279.7 2957.83   292.6 2958.91     317 2959.25   354.9 2957.16   371.9 2957.91
   390.4 2956.64   407.3 2958.82   421.3 2958.56   435.6 2960.31   451.1 2959.79
   463.8 2957.91   480.7 2960.26     492 2959.45   534.7 2961.69   548.5 2963.43
   585.7 2970.78     605 2977.74   619.7 2984.63   625.3    2986   637.7 2986.39
#Mann= 3 ,-1,0
       0      .1       0   267.1    .045       0   292.6      .1       0
Bank Sta=267.1,292.6
XS Rating Curve= 0 ,0
Exp/Cntr=0.3,0.1

Type RM Length L Ch R = 1 ,18226   ,166.1,170.6,173.9
XS GIS Cut Line= 2
2337515.91166799645661.2478770162337951.01886278645359.845497288
#Sta/Elev= 30
       0  2965.4     8.9 2964.27    28.2 2966.14   102.5  2963.6   118.1  2962.2
   126.8 2963.08   155.5 2961.43   199.8 2961.06     259 2959.26   267.6 2958.67
   274.1 2955.25   281.1 2954.04   299.2 2955.18   316.2 2955.97   326.3 2955.57
   342.3 2957.03   360.4 2957.25   365.3 2957.68   373.9 2961.13   379.9 2961.69
   423.7 2978.06   433.4 2985.86   438.3 2988.74     448 2990.13   463.1 2989.74
   468.8 2992.99     482 3004.62   488.9 3006.79   506.2 3014.07   529.3 3025.76
#Mann= 4 ,-1,0
       0      .1       0   274.1    .045       0   299.2      .1       0
     400     .06       0
Bank Sta=274.1,299.2
XS Rating Curve= 0 ,0
Exp/Cntr(USF)=0,0
Exp/Cntr=0.3,0.1

Type RM Length L Ch R = 1 ,18055   ,139.5,140.9,142.4
XS GIS Cut Line= 3
2337480.48185226645722.8701093562337793.46466402645642.591870374
2337998.37881539645585.189275141
#Sta/Elev= 30
       0 2966.32    20.3 2962.76    36.8 2964.04    90.5 2962.38   116.2 2962.93
   185.5 2958.94   226.8 2958.82   239.2 2957.34   247.6 2957.97   268.1 2956.92
   280.5 2957.62   292.9  2955.6   309.4 2957.51   321.8 2955.49   334.2 2956.63
   345.9 2954.62   359.2 2955.44   362.92954.026   371.6 2952.84   389.3 2954.04
   404.3 2956.31   446.4 2958.67   450.5 2960.92   467.2 2973.79   483.8 2982.53
   496.2 2983.99   508.7 2983.52   512.9 2984.45   525.3 2992.37   535.9 2997.55
#Mann= 4 ,-1,0
       0      .1       0   362.9    .045       0   389.3      .1       0
  483.11     .06       0
Bank Sta=362.9,389.3
XS Rating Curve= 0 ,0
Exp/Cntr=0.3,0.1

Type RM Length L Ch R = 1 ,17915   ,254.4,262.9,261.4
XS GIS Cut Line= 4
2337497.47994089645775.2616931882337850.92827824645769.587063919
2337892.27200577645762.2911120012338076.29212637645759.859128029
#Sta/Elev= 30
       0 2962.55    10.7 2960.01    26.7 2959.31    54.7 2959.85   178.7 2956.72
   206.7 2957.23   258.7 2954.86   276.4 2955.08   294.7 2956.61   306.7 2953.87
   326.7 2956.29   338.7 2954.36   350.3 2953.73   375.1 2952.88   391.3 2953.81
   407.4 2955.93   435.4 2955.28   443.4 2957.61   455.1 2965.02   475.4 2980.48
   483.3 2982.25   495.4 2982.16   499.4 2983.94   518.9 2998.48   527.4 3007.65
   531.4 3010.72   543.4 3017.77   551.4 3020.48   562.3 3027.17   579.5 3035.71
#Mann= 5 ,-1,0
       0      .1       0   350.3    .045       0   391.3      .1       0
  445.48     .06       0  545.48      .1       0
Bank Sta=350.3,391.3
XS Rating Curve= 0 ,0
Exp/Cntr(USF)=0,0
Exp/Cntr=0.3,0.1

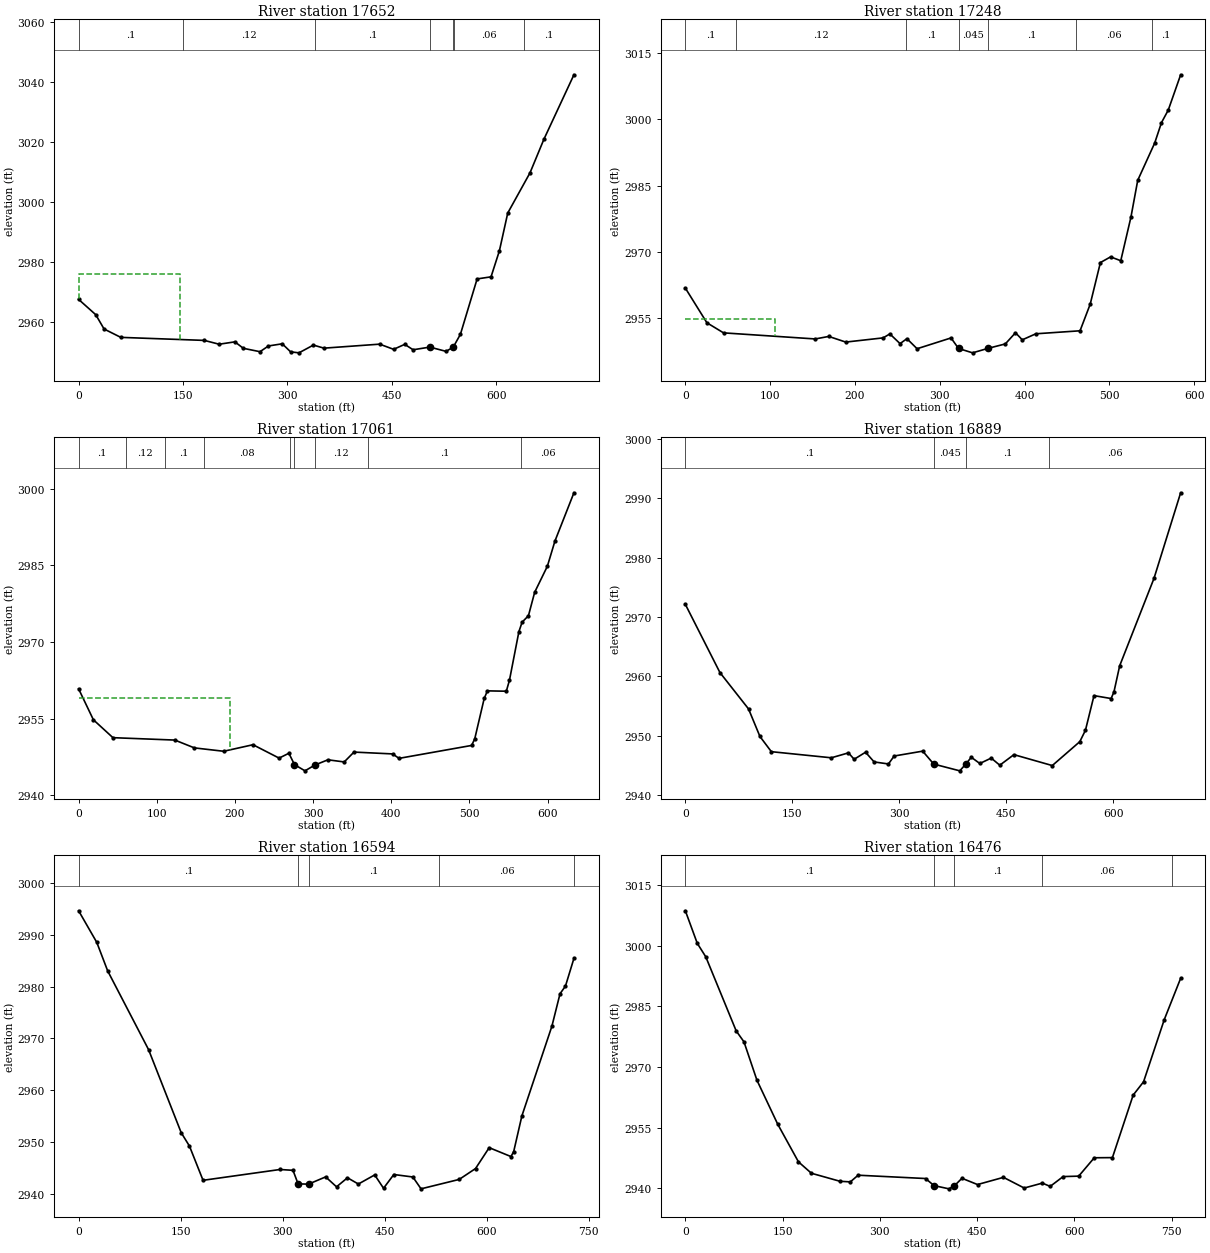
Type RM Length L Ch R = 1 ,17652   ,370.8,404,382.4
XS GIS Cut Line= 2
 2337407.6201291645996.9920205752338119.25796722646007.223367972
#Sta/Elev= 30
       0 2967.62    24.6 2962.53    36.6 2957.76    60.6 2954.98   180.6 2953.97
   201.9  2952.7   224.6 2953.49   236.6 2951.34   260.6 2950.21   272.8 2952.12
   292.6 2952.84   304.6 2950.16   316.6 2949.83   337.3 2952.41   352.6 2951.39
   432.6 2952.72   452.6    2951   468.6 2952.66   480.6 2950.85   504.6 2951.74
     528 2950.32  538.322951.736   548.6    2956   572.6 2974.44   592.6 2975.13
   604.6 2983.79   616.6 2996.37   648.6 3009.76   668.6 3020.95   711.7  3042.4
#Mann= 7 ,-1,0
       0      .1       0     150     .12       0     340      .1       0
   504.6    .045       0  538.32      .1       0     540     .06       0
     640      .1       0
#XS Ineff= 2 , 0
          145.17 2976.03
Permanent Ineff=
       F       F
Bank Sta=504.6,538.32
XS Rating Curve= 0 ,0
Exp/Cntr(USF)=0,0
Exp/Cntr=0.3,0.1

Type RM Length L Ch R = 1 ,17248   ,179.6,186.4,190.8
XS GIS Cut Line= 2
2337491.18285162646178.4667257872338074.67080372646157.893838207
#Sta/Elev= 30
       0 2961.75    25.4 2953.89      45  2951.6   153.1 2950.22   169.1 2950.79
   189.1 2949.51   233.1 2950.46   241.1 2951.36   253.1 2949.16   261.2 2950.28
   273.2    2948   313.2 2950.45  322.072948.059   338.6 2947.07   356.32948.058
   377.2 2949.09   389.2 2951.63   397.2 2950.02   413.2 2951.39   465.3 2952.07
   477.3 2958.12   489.3 2967.54   501.3 2968.83   513.3 2967.96   525.3 2977.85
   533.3 2986.19   553.3 2994.64   561.3 2999.27   569.3 3002.12   583.9 3010.12
#Mann= 7 ,-1,0
       0      .1       0      60     .12       0     260      .1       0
  322.07    .045       0   356.3      .1       0     460     .06       0
     550      .1       0
#XS Ineff= 2 , 0
          105.57 2954.85
Permanent Ineff=
       F       F
Bank Sta=322.07,356.3
XS Rating Curve= 0 ,0
Exp/Cntr(USF)=0,0
Exp/Cntr=0.3,0.1

Type RM Length L Ch R = 1 ,17061   ,176.8,172.3,173.5
XS GIS Cut Line= 3
2337494.03136499646244.0150491072337864.44348747646352.471745457
2338109.87746765646386.126985042
#Sta/Elev= 30
       0 2960.81    18.9 2954.76    43.9 2951.26   123.1 2950.79   148.1 2949.26
   185.6  2948.6   223.1 2949.88   256.5 2947.26     269 2948.21   276.22945.983
   289.6 2944.77   302.42945.915     319 2946.93   339.8 2946.51   352.3 2948.44
   401.8 2948.08   409.9 2947.21   502.8 2949.74   506.8 2951.03   518.9 2958.93
     523 2960.42   547.2 2960.35   551.2 2962.48   563.3 2972.01   567.4 2973.86
   575.5 2975.12   583.5 2979.72   599.7  2984.8   609.4 2989.73   633.7 2999.18
#Mann= 9 ,-1,0
       0      .1       0      60     .12       0     110      .1       0
     160     .08       0     270     .12       0   276.2    .045       0
   302.4     .12       0     370      .1       0  565.96     .06       0
#XS Ineff= 2 , 0
           193.5 2958.99
Permanent Ineff=
       F       F
Bank Sta=276.2,302.4
XS Rating Curve= 0 ,0
Exp/Cntr=0.3,0.1

Type RM Length L Ch R = 1 ,16889   ,293.1,295.1,302.8
XS GIS Cut Line= 2
2337439.67192484 646504.470156332338133.53192954646475.100420682
#Sta/Elev= 30
       0 2972.13    48.5 2960.63    88.6  2954.5   104.6 2949.85   120.6 2947.29
   204.7 2946.26   228.7 2947.09   236.7 2946.01   252.7  2947.2   264.7 2945.56
   284.8 2945.22   292.8 2946.56   332.8 2947.38   348.3  2945.2   384.8 2944.06
   393.72945.264   400.9 2946.35   412.9  2945.3   428.9 2946.21   440.9 2945.01
   460.7 2946.79   514.5 2944.95   553.1 2948.98     561  2950.9     573 2956.74
     597 2956.25     601 2957.38     609 2961.77   657.1  2976.5   694.5 2990.94
#Mann= 4 ,-1,0
       0      .1       0   348.3    .045       0   393.7      .1       0
     510     .06       0
Bank Sta=348.3,393.7
XS Rating Curve= 0 ,0
Exp/Cntr(USF)=0,0
Exp/Cntr=0.3,0.1

Type RM Length L Ch R = 1 ,16594   ,113.8,118,121
XS GIS Cut Line= 2
2337413.54576256646732.7729054472338140.59076114646770.787333176
#Sta/Elev= 30
       0 2994.68    26.7 2988.57    42.7 2983.06   102.8 2967.84   150.8 2951.77
   162.9 2949.19   182.9 2942.57     296 2944.66   315.1  2944.5   322.6 2941.88
   337.9 2941.83   363.1 2943.23   379.1 2941.31   395.2 2943.06   411.2 2941.85
   435.2 2943.61   448.2 2941.03   463.3 2943.69   491.3 2943.21   503.3 2940.92
   559.4 2942.74   583.4 2944.84   603.5 2948.88   635.5 2947.16   639.5 2948.12
   651.5    2955   695.7 2972.38   707.6 2978.64   715.6 2980.12     728 2985.46
#Mann= 5 ,-1,0
       0      .1       0   322.6    .045       0   337.9      .1       0
     530     .06       0  728.04      .1       0
Bank Sta=322.6,337.9
XS Rating Curve= 0 ,0
Exp/Cntr=0.3,0.1

Type RM Length L Ch R = 1 ,16476   ,387.1,401,391.7
XS GIS Cut Line= 2
2337393.78171289 646860.578201072338157.39483976646847.728941724
#Sta/Elev= 30
       0  3008.6    18.4 3000.55    31.5 2997.22    78.4  2978.9    90.4  2976.2
   110.4 2966.71   142.4 2955.85   174.4 2946.53   194.4 2943.71   238.4 2941.73
   254.4 2941.58   266.4 2943.23   370.4 2942.41   383.4 2940.66   406.5 2939.86
   414.9 2940.62   426.5 2942.47   450.5 2940.92   490.5  2942.7   522.5 2940.06
   550.5 2941.28   562.5 2940.46   582.5 2942.89   606.5    2943   630.5 2947.54
   658.5 2947.58   690.5 2963.04   706.5 2966.32   738.5 2981.72   763.7 2991.91
#Mann= 5 ,-1,0
       0      .1       0   383.4    .045       0   414.9      .1       0
     550     .06       0     750      .1       0
Bank Sta=383.4,414.9
XS Rating Curve= 0 ,0
Exp/Cntr(USF)=0,0
Exp/Cntr=0.3,0.1