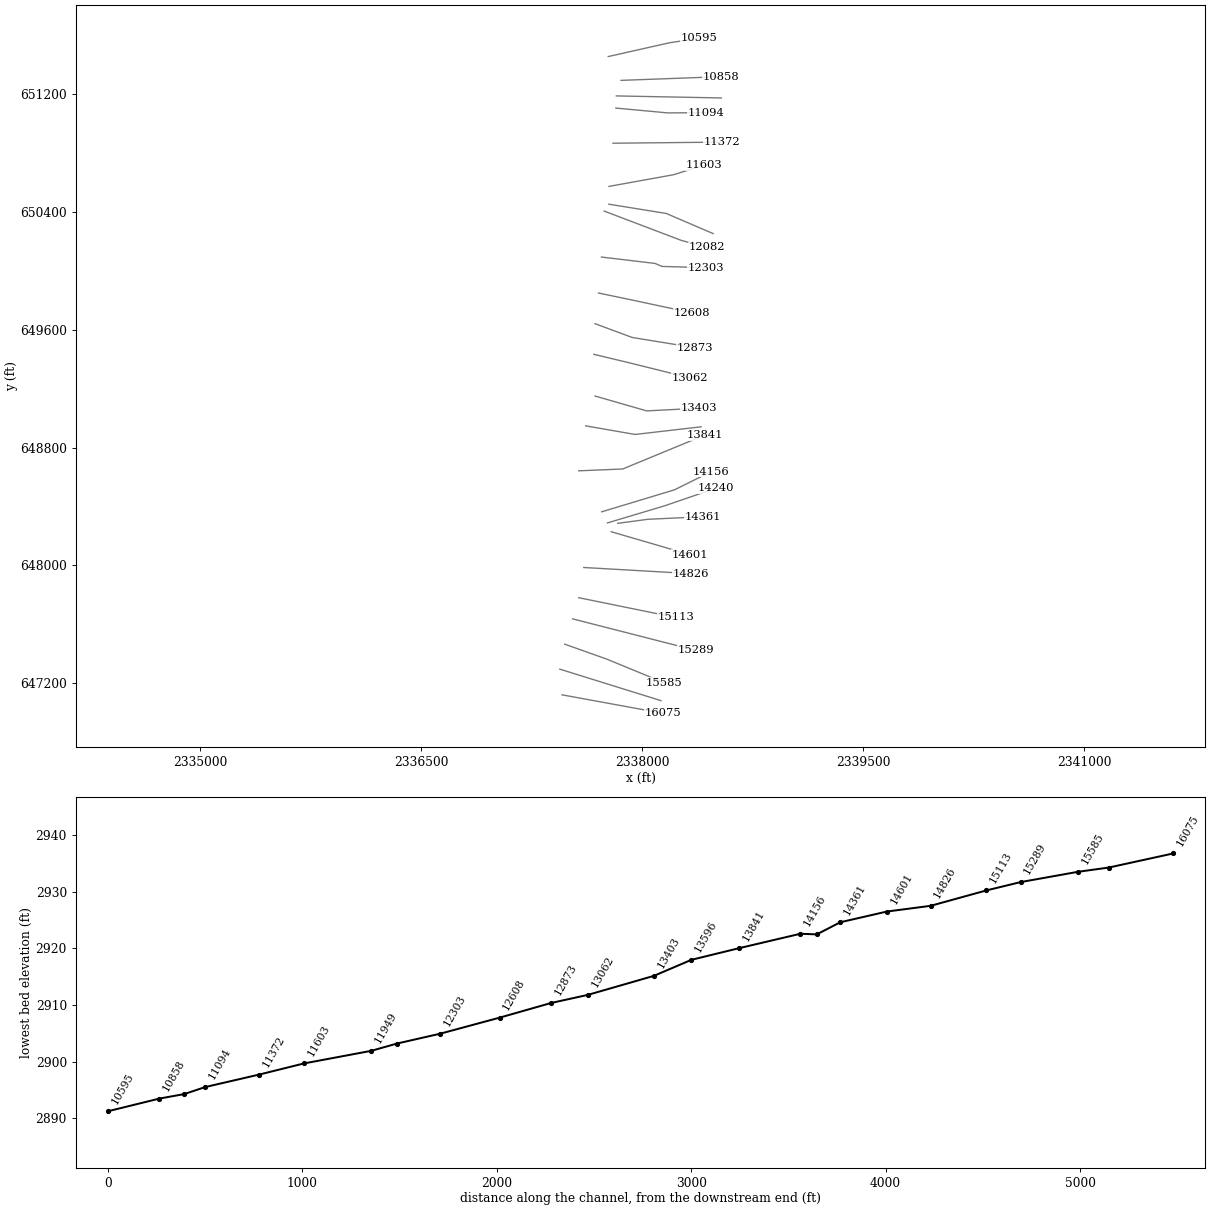
HEC-RAS study EFKGLADYFK.prj: EFKGLADYFK

--- EFKGLADYFK.g01 (geometry) --- (continued)

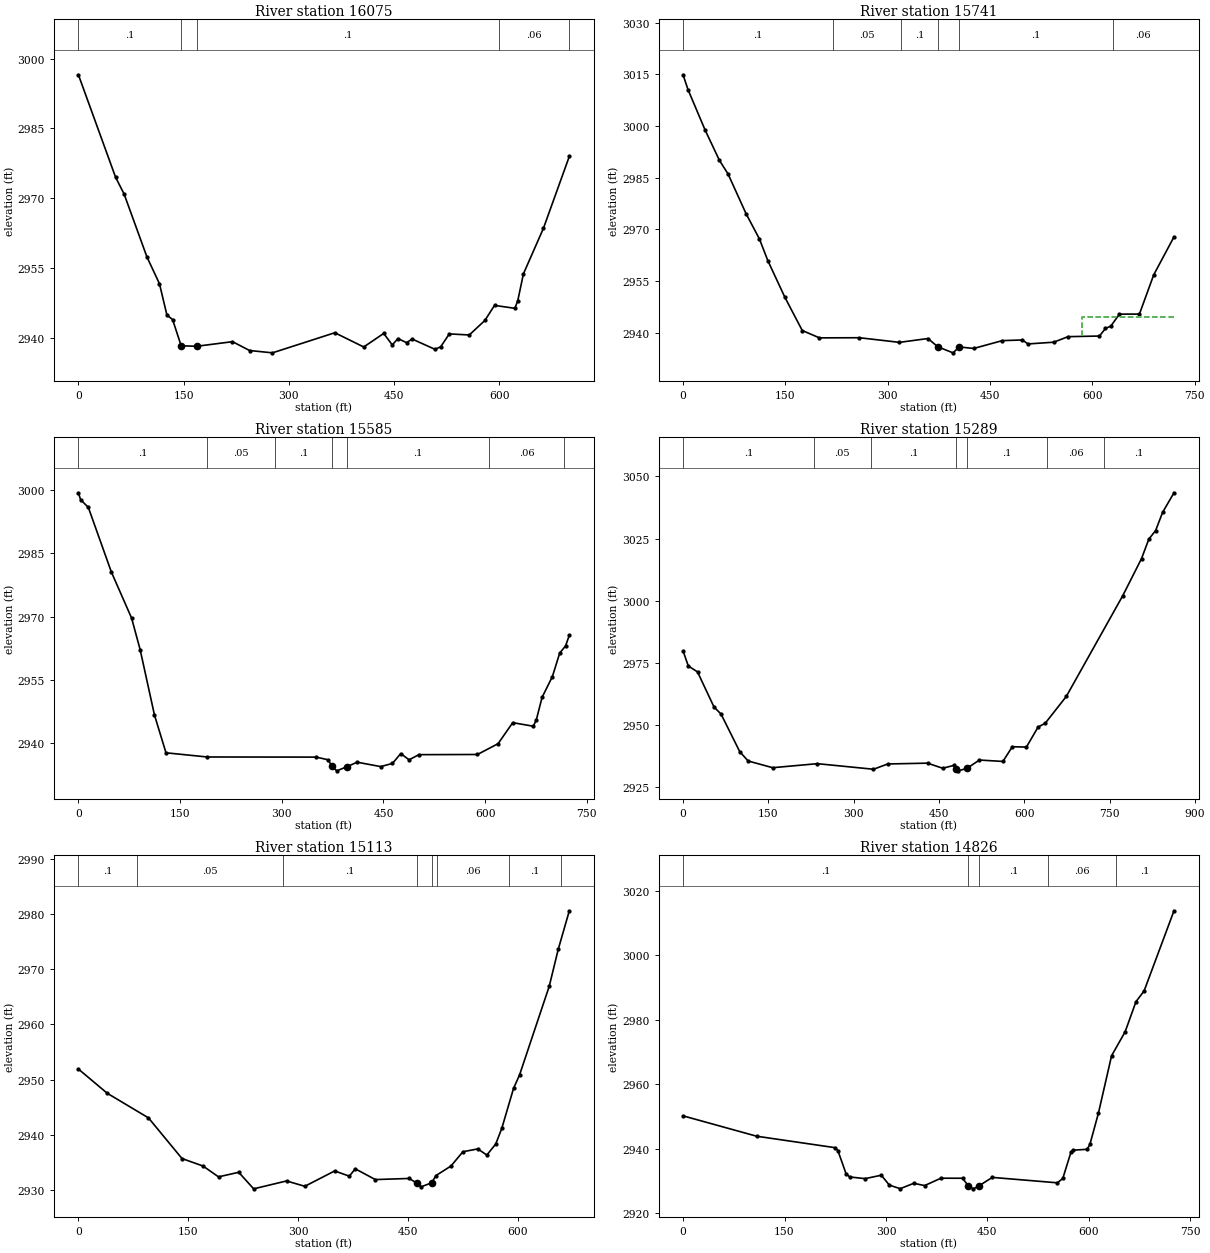
Type RM Length L Ch R = 1 ,16075   ,329.5,333.5,333.9
XS GIS Cut Line= 2
2337456.02621603647119.5600516212338144.52229581646993.463427225
#Sta/Elev= 30
       0 2996.51      53 2974.49    65.2 2970.86    97.7 2957.36   115.6 2951.58
   126.2 2944.86   134.3 2943.89   146.5 2938.26   168.6 2938.15   219.7 2939.14
   244.1 2937.24   276.7 2936.74   365.6 2941.06   406.8    2938   435.3 2940.91
   447.5 2938.44   455.6 2939.81   467.8 2938.93   475.9  2939.7   508.5 2937.49
   516.6 2938.05   528.8 2940.81   557.3 2940.58   579.6 2943.71   593.3 2946.94
   622.3 2946.31   626.4 2947.92   634.5 2953.72     663  2963.5   699.9 2978.95
#Mann= 5 ,-1,0
       0      .1       0   146.5    .045       0   168.6      .1       0
     600     .06       0  699.95      .1       0
Bank Sta=146.5,168.6
XS Rating Curve= 0 ,0
Exp/Cntr=0.3,0.1

Type RM Length L Ch R = 1 ,15741   ,157.4,156.5,157.3
XS GIS Cut Line= 2
2337441.24133196647293.8828547882338128.59154982647079.733540681
#Sta/Elev= 30
       0 3014.85     7.3 3010.52    32.4  2998.8    53.3 2990.05    65.9 2986.12
    92.3 2974.62     112 2967.25   124.3 2960.97   149.4  2950.3   174.8 2940.71
     200 2938.58   258.6 2938.62   317.3 2937.28   359.2 2938.39   373.5    2936
   395.8 2934.24     405 2935.95   426.2 2935.51   468.1 2937.78   497.5 2937.97
   505.8 2936.82   543.5 2937.32   564.5 2938.93   610.6 2939.11   619.4  2941.3
   627.3    2942   639.9 2945.46   669.2 2945.47   690.2 2956.86   719.9 2967.86
#Mann= 6 ,-1,0
       0      .1       0     220     .05       0     320      .1       0
   373.5    .045       0     405      .1       0     630     .06       0
#XS Ineff= 2 , 0
                          585.27         2944.63
Permanent Ineff=
       F       F
Bank Sta=373.5,405
XS Rating Curve= 0 ,0
Exp/Cntr(USF)=0,0
Exp/Cntr=0.3,0.1

Type RM Length L Ch R = 1 ,15585   ,295.4,295.8,296.5
XS GIS Cut Line= 3
2337474.42965087647463.6750997932337763.00248631647360.938994996
2338149.31818958647201.639678246
#Sta/Elev= 30
       0 2999.33     3.3 2997.67    14.6 2995.89    48.6 2980.58    78.5 2969.65
    91.1 2962.18   112.2 2946.72   129.2 2937.77     190 2936.78   350.9 2936.75
   368.2 2936.12   374.4 2934.53   381.1  2933.5   395.9 2934.46   411.2 2935.55
     446  2934.5   463.3 2935.26   475.5 2937.58   487.8 2936.11   502.3 2937.33
   588.7 2937.37   619.1 2939.93   640.7 2944.91     671 2944.06   675.4  2945.5
     684  2950.9   699.2 2955.81     710 2961.38   718.6 2963.06   724.2 2965.61
#Mann= 7 ,-1,0
       0      .1       0     190     .05       0     290      .1       0
   374.4    .045       0   395.9      .1       0  606.32     .06       0
  716.32      .1       0
Bank Sta=374.4,395.9
XS Rating Curve= 0 ,0
Exp/Cntr=0.3,0.1

Type RM Length L Ch R = 1 ,15289   ,176,176.3,176.7
XS GIS Cut Line= 2
2337527.59186184 647635.83095312 2338363.4649911647421.681639013
#Sta/Elev= 30
       0 2979.89     9.2 2973.82    25.4 2971.45    54.3 2957.37    66.7 2954.51
    99.7 2939.37   114.4 2935.64   157.5 2932.94     236 2934.56   334.7 2932.32
   359.8 2934.44   429.7 2934.77   456.3 2932.72   475.5 2933.84   480.1 2932.49
   483.7 2931.68     499 2932.69   520.9 2936.02   562.2 2935.46   578.7 2941.37
   603.5 2941.23   624.1 2949.29   636.5 2950.79   673.7 2961.61   772.8 3002.05
   805.8 3016.96   818.7 3024.81   830.6 3028.24     843 3035.61   862.9 3043.43
#Mann= 7 ,-1,0
       0      .1       0     230     .05       0     330      .1       0
   480.1    .045       0     499      .1       0     640     .06       0
     740      .1       0
Bank Sta=480.1,499
XS Rating Curve= 0 ,0
Exp/Cntr(USF)=0,0
Exp/Cntr=0.3,0.1

Type RM Length L Ch R = 1 ,15113   ,284.2,287.1,287.4
XS GIS Cut Line= 3
2337569.56811441647779.4300144782338136.76284357647663.747771186
2338227.15861869647648.251532395
#Sta/Elev= 30
       0 2951.92    39.4 2947.53    95.7 2943.07   141.5  2935.7   170.3 2934.34
   191.4 2932.38     219 2933.21   239.4 2930.21   284.3 2931.64   309.3 2930.67
     350 2933.45   370.1 2932.51   378.2 2933.84   405.6 2931.89   451.7 2932.09
     462 2931.29     468 2930.57   482.5  2931.3   488.5 2932.62   508.9 2934.34
   525.2 2936.93   545.6 2937.45   557.9 2936.33   570.1 2938.34   578.3 2941.15
   594.4 2948.41   602.6 2950.85   643.2 2966.94   655.4 2973.59   670.6  2980.6
#Mann= 8 ,-1,0
       0      .1       0      80     .05       0     280      .1       0
     462    .045       0   482.5      .1       0     490     .06       0
  588.87      .1       0  658.87     .06       0
Bank Sta=462,482.5
XS Rating Curve= 0 ,0
Exp/Cntr=0.3,0.1

Type RM Length L Ch R = 1 ,14826   ,235.9,224.9,218.7
XS GIS Cut Line= 2
2337603.58032814647984.6870938432338328.32890484647943.284675985
#Sta/Elev= 30
       0 2950.14   108.8 2943.82     225 2940.26     229 2939.32     241 2932.19
   246.4 2931.18   269.2 2930.66   293.1 2931.71   305.1 2928.64   321.1 2927.54
   341.1 2929.21   357.2  2928.5   381.2 2930.79   413.3 2930.78   421.8 2928.39
   429.3 2927.49   437.3  2928.4   457.3 2931.04   553.6 2929.36   561.5 2930.73
   573.5 2938.83   576.2 2939.48   597.6 2939.76   601.6 2941.32   614.1 2950.92
   633.6 2968.78   653.7 2976.25   669.7 2985.58   681.7  2988.9   725.9 3013.78
#Mann= 5 ,-1,0
       0      .1       0   421.8    .045       0   437.3      .1       0
     540     .06       0     640      .1       0
Bank Sta=421.8,437.3
XS Rating Curve= 0 ,0
Exp/Cntr(USF)=0,0
Exp/Cntr=0.3,0.1

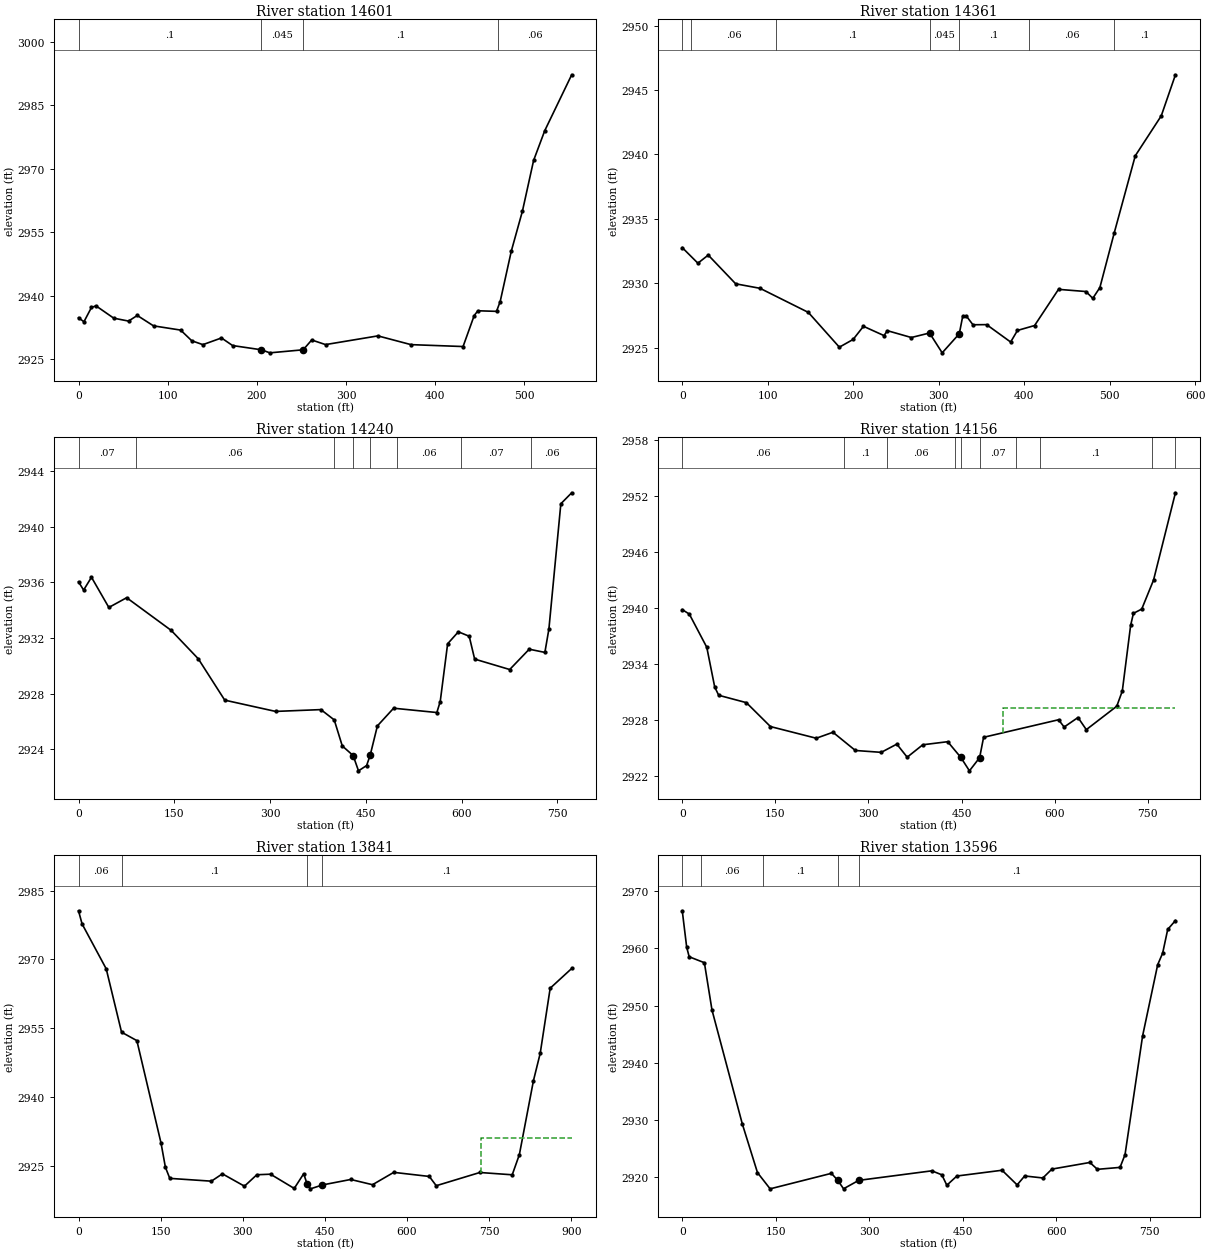
Type RM Length L Ch R = 1 ,14601   ,237.6,239.6,243.6
XS GIS Cut Line= 2
2337790.28388273648227.6321642912338321.12336158648072.712765233
#Sta/Elev= 30
       0 2934.78     6.1 2933.83    14.5 2937.21    19.6 2937.59    39.5 2934.68
    56.1 2933.99    65.9 2935.32    84.1 2932.86   114.5 2931.86     127 2929.33
   139.5 2928.42   160.3    2930   172.8  2928.2   205.1  2927.2   214.5 2926.48
   251.9  2927.2   261.5 2929.52     277 2928.43   335.7 2930.49   372.8 2928.42
   431.2 2927.97   443.7 2935.31   447.8 2936.43   468.7 2936.29   472.8  2938.6
   485.3 2950.55   497.8 2960.03   510.3 2971.99   522.8 2979.03     553 2992.24
#Mann= 4 ,-1,0
       0      .1       0   205.1    .045       0   251.9      .1       0
     470     .06       0
Bank Sta=205.1,251.9
XS Rating Curve= 0 ,0
Exp/Cntr=0.3,0.1

Type RM Length L Ch R = 1 ,14361   ,115.1,121.1,115
XS GIS Cut Line= 3
2337834.02343921648284.7185809412338037.70309029648311.974943402
 2338408.7631981648329.751041986
#Sta/Elev= 30
       0 2932.76    18.3 2931.55    30.4 2932.18    62.5 2929.95      91  2929.6
   147.5 2927.73   183.8 2925.03   199.9 2925.63     212 2926.65     236 2925.93
     240 2926.31     268 2925.78   289.3 2926.13   304.1 2924.59   324.1 2926.07
   328.1 2927.42   332.1 2927.47   340.1 2926.77   356.1 2926.78   384.2 2925.43
   392.2 2926.33   412.2 2926.71   440.2 2929.52   472.3 2929.35   480.3 2928.82
   488.6 2929.66   505.5 2933.93     530 2939.89   560.4 2942.99     577 2946.18
#Mann= 7 ,-1,0
       0     .07       0      10     .06       0     110      .1       0
   289.3    .045       0   324.1      .1       0   405.5     .06       0
   505.5      .1       0
Bank Sta=289.3,324.1
XS Rating Curve= 0 ,0
Exp/Cntr(USF)=0,0
Exp/Cntr=0.3,0.1

Type RM Length L Ch R = 1 ,14240   ,84.1,84,83.2
XS GIS Cut Line= 4
2337764.46384197648287.5768198632338152.71984884648403.663414882
2338231.73677486648430.9779078272338500.00411629648522.676562716
#Sta/Elev= 30
       0 2936.03       8 2935.44    20.3 2936.36    47.5 2934.19    75.4 2934.89
   145.2 2932.54   187.6  2930.5     229 2927.53   308.6 2926.72   379.6 2926.85
   400.5 2926.11   413.1 2924.24   430.1 2923.55   438.5 2922.45   451.2 2922.83
   456.82923.574   468.1 2925.68   493.5 2926.95   561.2 2926.64   566.5 2927.43
   578.1 2931.58   594.9 2932.44   611.9 2932.12   620.4 2930.48   675.3 2929.73
   705.9 2931.19   730.4 2930.96   736.7 2932.64   755.4 2941.64   772.4 2942.43
#Mann= 8 ,-1,0
       0     .07       0      90     .06       0     400      .1       0
   430.1    .045       0   456.8      .1       0  498.84     .06       0
  598.84     .07       0  708.84     .06       0
Bank Sta=430.1,456.8
XS Rating Curve= 0 ,0
Exp/Cntr(USF)=0,0
Exp/Cntr=0.3,0.1

Type RM Length L Ch R = 1 ,14156   ,308.2,315.1,314.2
XS GIS Cut Line= 3
2337725.25780628648362.897662005 2338220.2052077648512.554788738
2338468.78755293648635.836604919
#Sta/Elev= 30
       0 2939.82    11.4 2939.34    39.5 2935.79    52.3 2931.53    58.7 2930.65
   103.3 2929.86   142.1  2927.3   215.9 2926.05   242.8 2926.69   278.9 2924.74
   320.6 2924.54   345.7 2925.42   362.4 2924.02   387.5 2925.35   427.7 2925.68
   448.82923.999   462.7 2922.56   479.1 2923.97   485.5 2926.15   606.3 2928.03
   615.3 2927.25   637.6 2928.27     651 2926.97   700.1 2929.48     709 2931.11
   722.4 2938.13   726.9 2939.42   740.3 2939.88   759.3 2942.98   794.6 2952.33
#Mann= 10 ,-1,0
       0     .06       0     260      .1       0     330     .06       0
     440     .07       0   448.8    .045       0   479.1     .07       0
  537.08     .06       0  577.08      .1       0  757.08     .06       0
  794.55      .1       0
#XS Ineff= 2 , 0
                          516.45         2929.32
Permanent Ineff=
       F       F
Bank Sta=448.8,479.1
XS Rating Curve= 0 ,0
Exp/Cntr=0.3,0.1

Type RM Length L Ch R = 1 ,13841   ,248.9,245.7,230.5
XS GIS Cut Line= 3
2337569.65220285648641.5265352922337868.07963412648653.961011595
2338424.52244868  648883.9988232
#Sta/Elev= 30
       0  2980.6     6.5 2977.74    50.6 2967.95    78.6 2954.15   106.6 2952.31
   150.7    2930   158.7 2924.73   166.7  2922.3   242.7 2921.69   262.8 2923.29
   303.1  2920.6   325.7 2923.09   350.7 2923.21     394 2920.11   411.3 2923.31
   417.6 2921.05   423.7 2920.02   445.52920.868   497.2 2922.06     537 2920.92
   575.8 2923.61   640.7 2922.72   653.4  2920.7     733 2923.58   792.2 2923.08
   805.2 2927.47     831 2943.62   843.3 2949.55   861.5 2963.73   900.8 2968.03
#Mann= 4 ,-1,0
       0     .06       0      80      .1       0   417.6    .045       0
   445.5      .1       0
#XS Ineff= 2 , 0
                          734.31         2930.99
Permanent Ineff=
       F       F
Bank Sta=417.6,445.5
XS Rating Curve= 0 ,0
Exp/Cntr(USF)=0,0
Exp/Cntr=0.3,0.1

Type RM Length L Ch R = 1 ,13596   ,192.7,193,188.2
XS GIS Cut Line= 3
2337617.22756466648946.9444009742337952.45341572648888.696083469
2338400.46954992648940.524800325
#Sta/Elev= 30
       0 2966.57     7.1  2960.2    11.1 2958.53    35.5 2957.49    47.7 2949.22
    96.4 2929.29   120.7 2920.79     141 2917.96   239.3 2920.67   249.7 2919.42
   258.8 2917.97   283.1 2919.44   400.4 2921.11   416.5 2920.41   424.5 2918.59
   440.6  2920.2   513.1 2921.21   537.3 2918.65   549.4 2920.21   578.6 2919.86
   593.1 2921.41     654 2922.57   666.1 2921.37   702.4 2921.71   710.4 2923.93
   738.6 2944.69   762.8 2957.14   770.8 2959.17   778.9 2963.31   791.3 2964.86
#Mann= 5 ,-1,0
       0      .1       0      30     .06       0     130      .1       0
   249.7    .045       0   283.1      .1       0
Bank Sta=249.7,283.1
XS Rating Curve= 0 ,0
Exp/Cntr=0.3,0.1

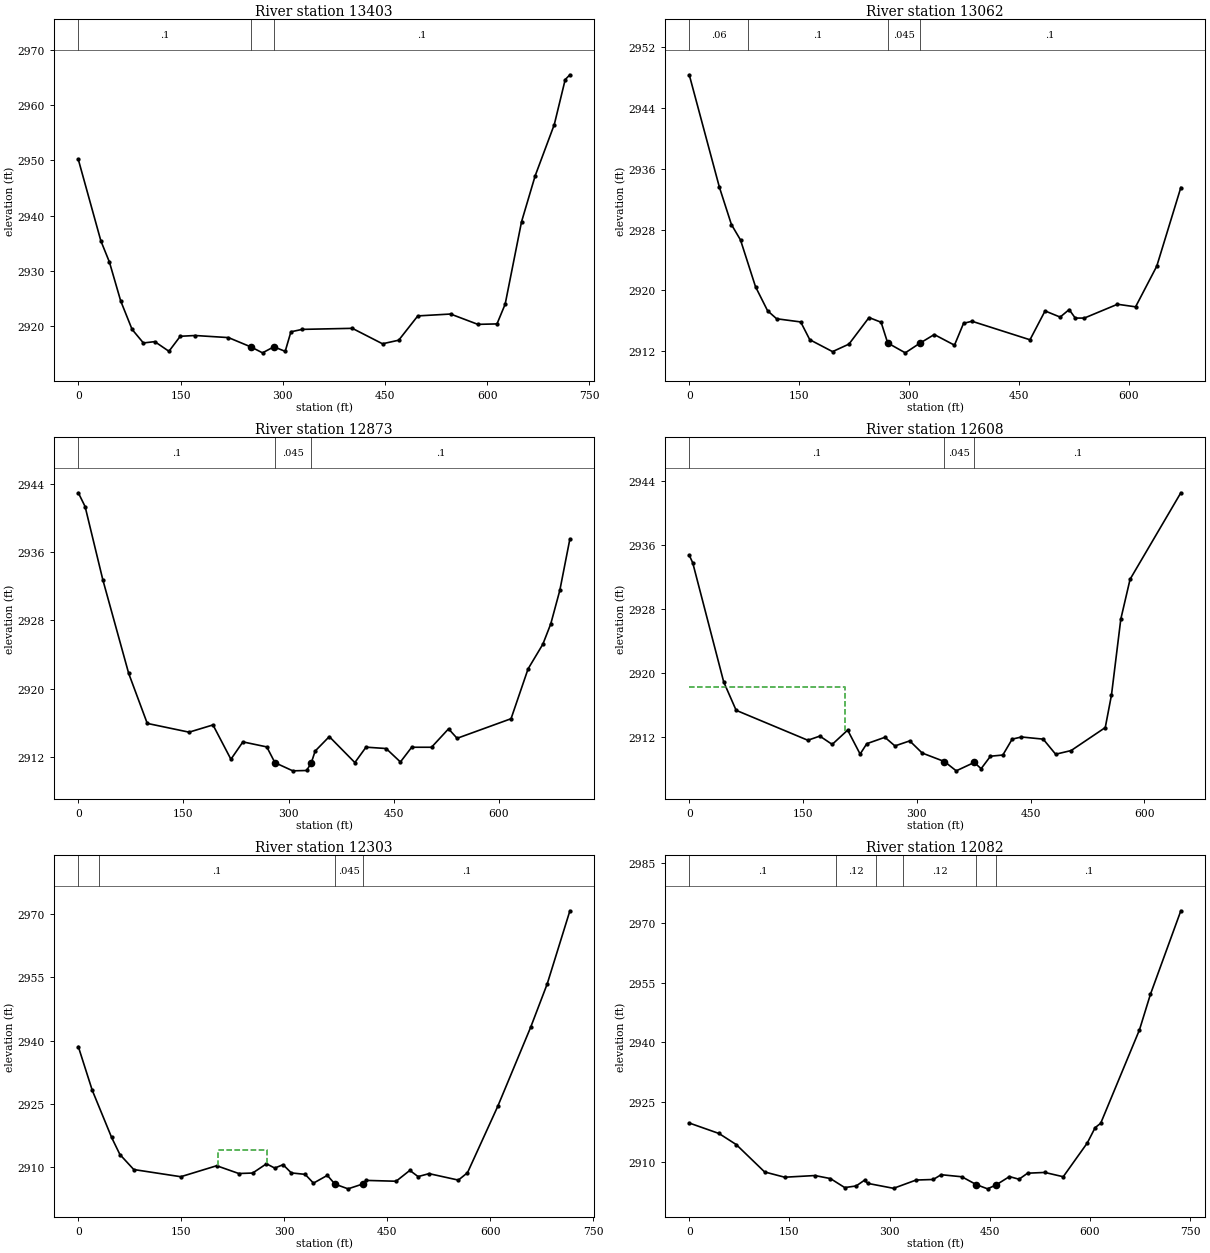
Type RM Length L Ch R = 1 ,13403   ,328,340.1,330.4
XS GIS Cut Line= 3
2337680.39510986649149.6960705172338030.99632916649048.737604224
 2338387.1043739649067.093689005
#Sta/Elev= 30
       0 2950.16    33.1 2935.41    45.6 2931.59    62.2 2924.53    78.9 2919.38
    95.5 2916.92   112.2 2917.16     133 2915.41   149.6 2918.13   171.5 2918.27
   220.4 2917.89   253.7 2916.18   270.3 2915.13     287 2916.22   303.6  2915.4
     312 2918.94   328.6 2919.38   402.1 2919.57   446.4 2916.77   470.2 2917.42
   498.2 2921.82   546.3 2922.16   586.3 2920.29   614.4 2920.37   626.4 2923.95
   650.4 2938.86   670.4 2947.19   698.5 2956.49   714.5 2964.63   721.4  2965.5
#Mann= 3 ,-1,0
       0      .1       0   253.7    .045       0     287      .1       0
Bank Sta=253.7,287
XS Rating Curve= 0 ,0
Exp/Cntr(USF)=0,0
Exp/Cntr=0.3,0.1

Type RM Length L Ch R = 1 ,13062   ,185,189.1,186.4
XS GIS Cut Line= 3
2337672.13385829649433.1105710922337907.65514266649376.638190757
2338324.14461849649273.394952606
#Sta/Elev= 30
       0  2948.4    41.2 2933.58    57.6 2928.67      70 2926.64    90.5 2920.48
     107 2917.31   119.3 2916.26   152.2 2915.84   164.6  2913.5   195.7 2911.93
   218.1 2912.92   245.5 2916.42     262  2915.8     271 2913.07     295 2911.77
   314.8 2913.03   334.6 2914.18   362.2 2912.78   374.6 2915.66   386.1 2915.93
   465.3 2913.49   485.9 2917.29   506.5 2916.48   518.8 2917.47   527.1 2916.35
   539.5 2916.35   584.8 2918.17   609.5 2917.83   638.4 2923.18   671.3 2933.55
#Mann= 4 ,-1,0
       0     .06       0      80      .1       0     271    .045       0
   314.8      .1       0
Bank Sta=271,314.8
XS Rating Curve= 0 ,0
Exp/Cntr=0.3,0.1

Type RM Length L Ch R = 1 ,12873   ,266.5,264.9,261.4
XS GIS Cut Line= 3
2337679.93910653649641.363594636 2337932.8451635649547.543605759
 2338359.1142434649478.198396588
#Sta/Elev= 30
       0 2942.99     9.7 2941.37      35 2932.77    71.9 2921.78    98.4 2915.91
   158.1 2914.88   192.2 2915.73   217.8  2911.7   234.9 2913.74     269 2913.15
   280.6  2911.3   306.1 2910.34   325.8 2910.38   332.42911.251     338 2912.66
   358.2 2914.36   394.7 2911.31   410.6 2913.12   439.3 2912.96   459.7 2911.38
   475.8 2913.11   504.1 2913.11   528.4 2915.27   540.6 2914.16   617.6 2916.46
   641.9 2922.31     663 2925.21   674.3  2927.6   687.2 2931.53   701.6 2937.58
#Mann= 3 ,-1,0
       0      .1       0   280.6    .045       0   332.4      .1       0
Bank Sta=280.6,332.4
XS Rating Curve= 0 ,0
Exp/Cntr(USF)=0,0
Exp/Cntr=0.3,0.1

Type RM Length L Ch R = 1 ,12608   ,305.6,305.6,298.2
XS GIS Cut Line= 3
2337703.71204857649849.511333176 2337907.7789038649807.163571563
2338337.58271328649715.313857345
#Sta/Elev= 30
       0 2934.75     4.6  2933.8    45.4 2918.89    61.8 2915.33   156.3 2911.58
   172.1  2912.1   188.4 2911.06   208.8 2912.85   225.2 2909.85     234 2911.15
   257.9 2911.95   271.1 2910.87   290.6  2911.5     307 2909.98   336.4 2908.91
   351.9 2907.75   375.6  2908.8   384.7 2908.02     397 2909.58   413.3 2909.73
   425.6 2911.72   437.9 2911.99   466.5 2911.72   482.9 2909.83   503.3 2910.29
   548.3 2913.17   556.5 2917.25   568.8 2926.76     581 2931.74   647.9 2942.57
#Mann= 3 ,-1,0
       0      .1       0   336.4    .045       0   375.6      .1       0
#XS Ineff= 2 , 0
          205.77 2918.27
Permanent Ineff=
       F       F
Bank Sta=336.4,375.6
XS Rating Curve= 0 ,0
Exp/Cntr=0.3,0.1

Type RM Length L Ch R = 1 ,12303   ,217.4,221.2,221.8
XS GIS Cut Line= 4
2337723.97305134650094.0644801852338087.64138491650050.689516973
2338134.65974171650030.4229838692338433.29759719650021.915144219
#Sta/Elev= 30
       0 2938.61    20.3 2928.27    48.5  2917.1    60.6 2913.05    80.8 2909.49
   149.3 2907.79   201.6 2910.39   233.8 2908.55     254 2908.66   274.1 2910.85
   286.2 2909.84   298.3 2910.64   310.4 2908.69   330.5 2908.35   342.6 2906.27
   362.8 2908.11   373.9 2906.04     393 2904.92  414.482906.069     419 2906.92
     463 2906.72     483 2909.29     495 2907.82     511 2908.52   553.7 2906.99
     567 2908.74     611 2924.43   659.1 2943.22   683.1 2953.44   716.2 2970.78
#Mann= 4 ,-1,0
       0     .06       0      30      .1       0   373.9    .045       0
  414.48      .1       0
#XS Ineff= 1 ,-1
  203.05  274.51 2914.07
Permanent Ineff=
       F
Bank Sta=373.9,414.48
XS Rating Curve= 0 ,0
Exp/Cntr(USF)=0,0
Exp/Cntr=0.3,0.1

Type RM Length L Ch R = 1 ,12082   ,133.5,132.9,132.3
XS GIS Cut Line= 3
2337742.59878304650406.1976982632338266.97772564650206.914481307
2338435.98202002650161.013947601
#Sta/Elev= 30
       0 2919.73    44.5  2917.1    70.4 2914.31   112.9 2907.43   142.9 2906.11
   188.1 2906.53   211.4 2905.77   232.8 2903.51   249.9 2903.91   262.7 2905.39
     267 2904.57   305.9 2903.32   339.7  2905.4   365.4 2905.54   377.2 2906.74
   408.2 2906.22   429.9 2904.25   446.7 2903.19   459.6 2904.19   479.5 2906.27
   493.8  2905.6   506.6 2907.12   532.4 2907.31     560 2906.23     596 2914.71
   607.8 2918.57   616.1 2919.66   674.2 2943.16   690.5 2952.03   736.1 2973.05
#Mann= 6 ,-1,0
       0      .1       0     220     .12       0     280      .1       0
     320     .12       0   429.9    .045       0   459.6      .1       0
Bank Sta=429.9,459.6
XS Rating Curve= 0 ,0
Exp/Cntr=0.3,0.1

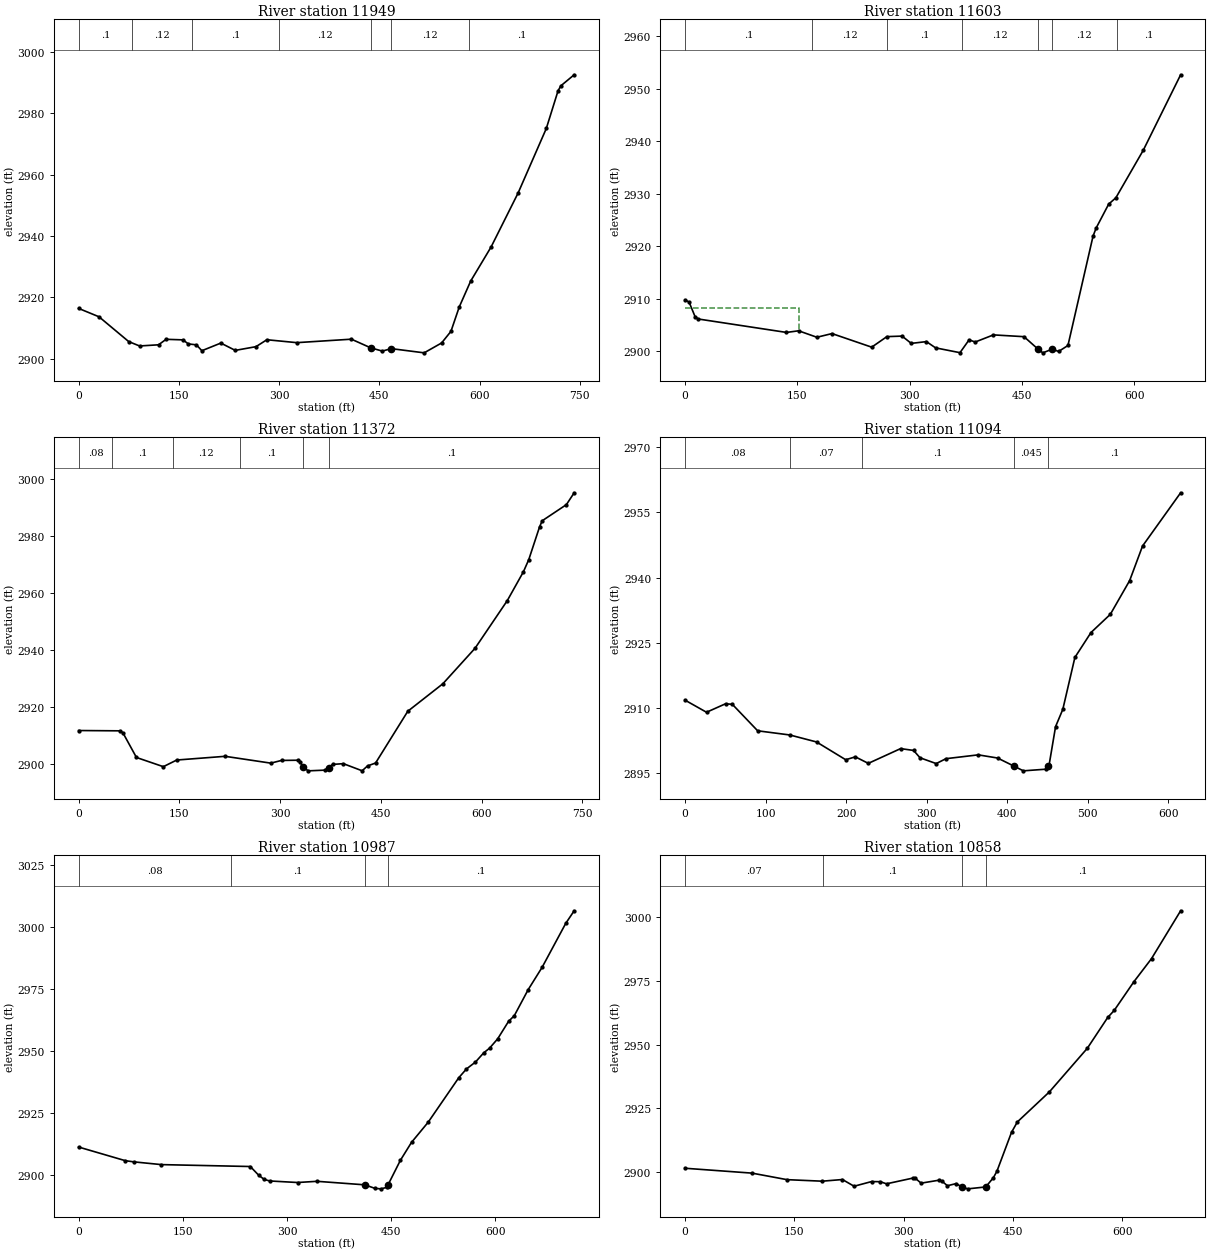
Type RM Length L Ch R = 1 ,11949   ,332.9,345.5,350
XS GIS Cut Line= 3
2337774.11254156650453.1627543582338163.71192755650390.317798426
 2338482.4147704650253.259563419
#Sta/Elev= 30
       0 2916.38    30.5 2913.65      75 2905.56    91.2 2904.14   119.6 2904.52
   130.9 2906.31   156.1 2906.13   164.2 2904.81   176.3  2904.5   184.4 2902.59
   212.8 2905.08   234.4  2902.7   265.4 2903.91   281.7 2906.17   326.4 2905.22
   408.2 2906.35     4372903.542   454.5 2902.47   467.9 2903.27   517.1  2901.9
   543.2 2905.12   557.2  2908.9   569.6 2916.85   586.7 2925.28   617.2 2936.38
   657.7    2954   699.9 2975.03   717.4 2987.26   721.6 2988.92   741.6 2992.53
#Mann= 7 ,-1,0
       0      .1       0      80     .12       0     170      .1       0
     300     .12       0     437    .045       0   467.9     .12       0
  584.64      .1       0
Bank Sta=437,467.9
XS Rating Curve= 0 ,0
Exp/Cntr(USF)=0,0
Exp/Cntr=0.3,0.1

Type RM Length L Ch R = 1 ,11603   ,235.7,231.2,222.2
XS GIS Cut Line= 3
     2337774.971      650574.0982338213.99787691650653.491097034
2338419.73144248650717.991057944
#Sta/Elev= 30
       0 2909.75     5.3 2909.36    13.4 2906.55    17.5 2906.13   135.4 2903.57
   151.6 2903.88     176 2902.65   196.2 2903.35   249.2 2900.76   269.5 2902.77
   289.8 2902.87     302 2901.48   322.3 2901.82   334.5 2900.63   367.1 2899.71
   379.3 2902.16   387.4 2901.74   411.8  2903.1   452.6 2902.76   471.8 2900.33
   477.8 2899.68   490.3 2900.39   498.8 2899.94   511.3 2901.08   544.8 2921.91
     549 2923.48   565.7 2928.02   575.3 2929.23   611.9 2938.29   661.8 2952.67
#Mann= 7 ,-1,0
       0      .1       0     170     .12       0     270      .1       0
     370     .12       0   471.8    .045       0   490.3     .12       0
  576.15      .1       0
#XS Ineff= 2 , 0
          151.72 2908.31
Permanent Ineff=
       F       F
Bank Sta=471.8,490.3
XS Rating Curve= 0 ,0
Exp/Cntr=0.3,0.1

Type RM Length L Ch R = 1 ,11372   ,267,278.3,269.4
XS GIS Cut Line= 2
2337802.05365412650867.4820858992338539.82221937650875.036030253
#Sta/Elev= 30
       0 2911.84    62.1 2911.73    66.1 2910.97    86.1 2902.39   126.1 2899.17
   146.1  2901.5   218.1  2902.8   286.1 2900.41   302.1 2901.36   326.1 2901.43
   330.1  2900.9   334.1 2898.89   342.1 2897.71   366.1 2897.95   372.3 2898.85
   378.1 2899.96   394.1 2900.23   422.1 2897.73   430.1 2899.43   442.1 2900.45
   490.1  2918.6   542.3 2928.23   590.2 2940.67   638.2 2957.37   662.2 2967.47
   670.2 2971.74   686.2 2983.17   690.2 2985.36   726.2 2991.01   737.8 2995.17
#Mann= 6 ,-1,0
       0     .08       0      50      .1       0     140     .12       0
     240      .1       0   334.1    .045       0   372.3      .1       0
Bank Sta=334.1,372.3
XS Rating Curve= 0 ,0
Exp/Cntr(USF)=0,0
Exp/Cntr=0.3,0.1

Type RM Length L Ch R = 1 ,11094   ,107.5,106.7,106.3
XS GIS Cut Line= 3
 2337821.6796442651106.2668811692338172.86896595651073.600129951
2338435.49368312651074.780129951
#Sta/Elev= 30
       0 2911.77    26.6 2908.99    50.3 2910.95    58.7 2910.81    90.1 2904.72
     130 2903.76   163.2 2902.15   199.4 2898.06   211.4 2898.72   227.5 2897.22
   267.6 2900.62   283.7  2900.2   291.7 2898.51   311.8 2897.17   323.9  2898.3
     364 2899.18     388 2898.45     408 2896.62     420  2895.5     448 2895.88
  451.092896.644     452 2896.87     460 2905.68     469 2909.66     484 2921.62
     504 2927.35     528 2931.54     552 2939.31     568 2947.27   615.3 2959.53
#Mann= 5 ,-1,0
       0     .08       0     130     .07       0     220      .1       0
     408    .045       0  451.09      .1       0
Bank Sta=408,451.09
XS Rating Curve= 0 ,0
Exp/Cntr=0.3,0.1

Type RM Length L Ch R = 1 ,10987   ,127.7,128.7,129.5
XS GIS Cut Line= 2
2337824.98711587651188.8580161382338538.36908116651175.076773626
#Sta/Elev= 30
       0 2911.16    67.2 2905.65    79.2 2905.18   119.2 2904.06   247.2 2903.29
   259.2 2899.79   267.2 2898.07   275.2 2897.45   315.2 2896.83   343.3 2897.31
   412.22895.889   426.7 2894.45   435.3 2894.27   443.3 2894.83   445.52895.883
   463.3 2905.81   479.3 2913.05   503.3  2921.2   547.3 2939.16   558.4 2942.72
   571.3 2945.49   583.3 2949.24   591.6  2951.1   603.3 2954.87     619 2961.94
   627.3 2964.25   647.3 2974.78   667.3 2983.77   701.4 3001.57   713.5 3006.64
#Mann= 4 ,-1,0
       0     .08       0     220      .1       0   412.2    .045       0
   445.5      .1       0
Bank Sta=412.2,445.5
XS Rating Curve= 0 ,0
Exp/Cntr(USF)=0,0
Exp/Cntr=0.3,0.1

Type RM Length L Ch R = 1 ,10858   ,258.7,263.8,265.5
XS GIS Cut Line= 2
2337856.35432134651294.477013003 2338536.2093132651319.656827516
#Sta/Elev= 30
       0 2901.54    91.9 2899.63   139.9 2897.07   188.2 2896.47     216 2897.12
     232 2894.49     256 2896.32     268 2896.27   276.5 2895.44   312.9  2897.7
     316 2897.62     324  2895.7   348.1 2896.84   352.1 2896.62   360.1 2894.69
   372.1 2895.52   380.1 2894.19   388.1 2893.47   412.7 2894.21   423.2 2897.82
   428.1 2900.38   448.1 2915.61   456.1 2919.69   500.2 2931.51   552.2 2948.59
   580.2 2960.67   589.1 2963.43   616.2 2974.71   640.3 2983.73   680.3  3002.5
#Mann= 4 ,-1,0
       0     .07       0     190      .1       0   380.1    .045       0
   412.7      .1       0
Bank Sta=380.1,412.7
XS Rating Curve= 0 ,0
Exp/Cntr(USF)=0,0
Exp/Cntr=0.3,0.1

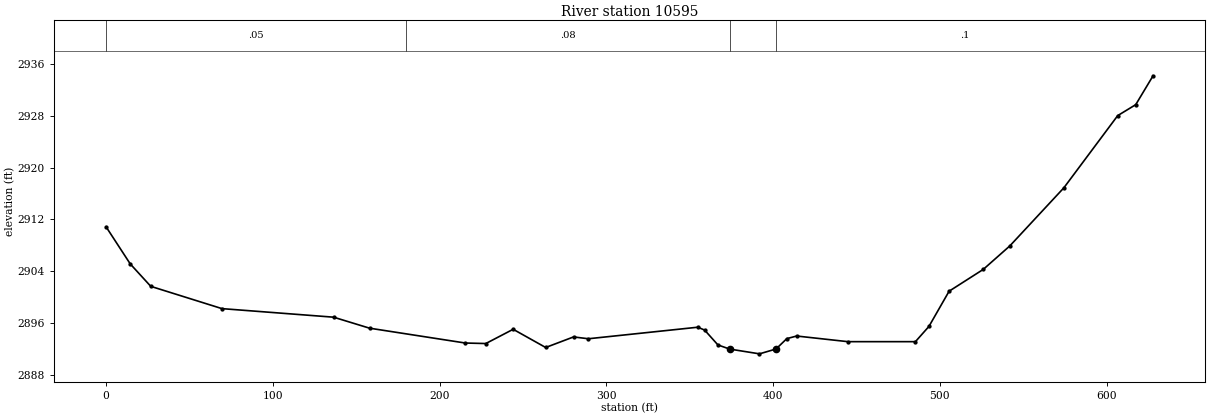
Type RM Length L Ch R = 1 ,10595   ,197.5,200,193.5
XS GIS Cut Line= 3
2337770.00355756651456.2998001412338186.62844315651550.169585805
 2338385.1523411651580.140356991
#Sta/Elev= 30
       0 2910.85    14.5 2905.12    26.8 2901.66    69.5 2898.22   136.4  2896.9
     158  2895.2   215.4 2892.91   227.7 2892.83   244.1 2895.03   263.6 2892.22
   280.3 2893.85   289.2 2893.57   354.8 2895.35   358.9 2894.91   366.9 2892.61
     374 2891.97   391.8 2891.24   401.72891.986   408.2 2893.59   414.1 2893.99
   444.8 2893.12   485.3 2893.12   493.4 2895.47   505.5 2900.91     526 2904.28
   541.9  2907.9   574.3 2916.87   606.6 2928.02   617.4 2929.71   627.8 2934.17
#Mann= 4 ,-1,0
       0     .05       0     180     .08       0     374    .045       0
   401.7      .1       0
Bank Sta=374,401.7
XS Rating Curve= 0 ,0
Exp/Cntr=0.3,0.1