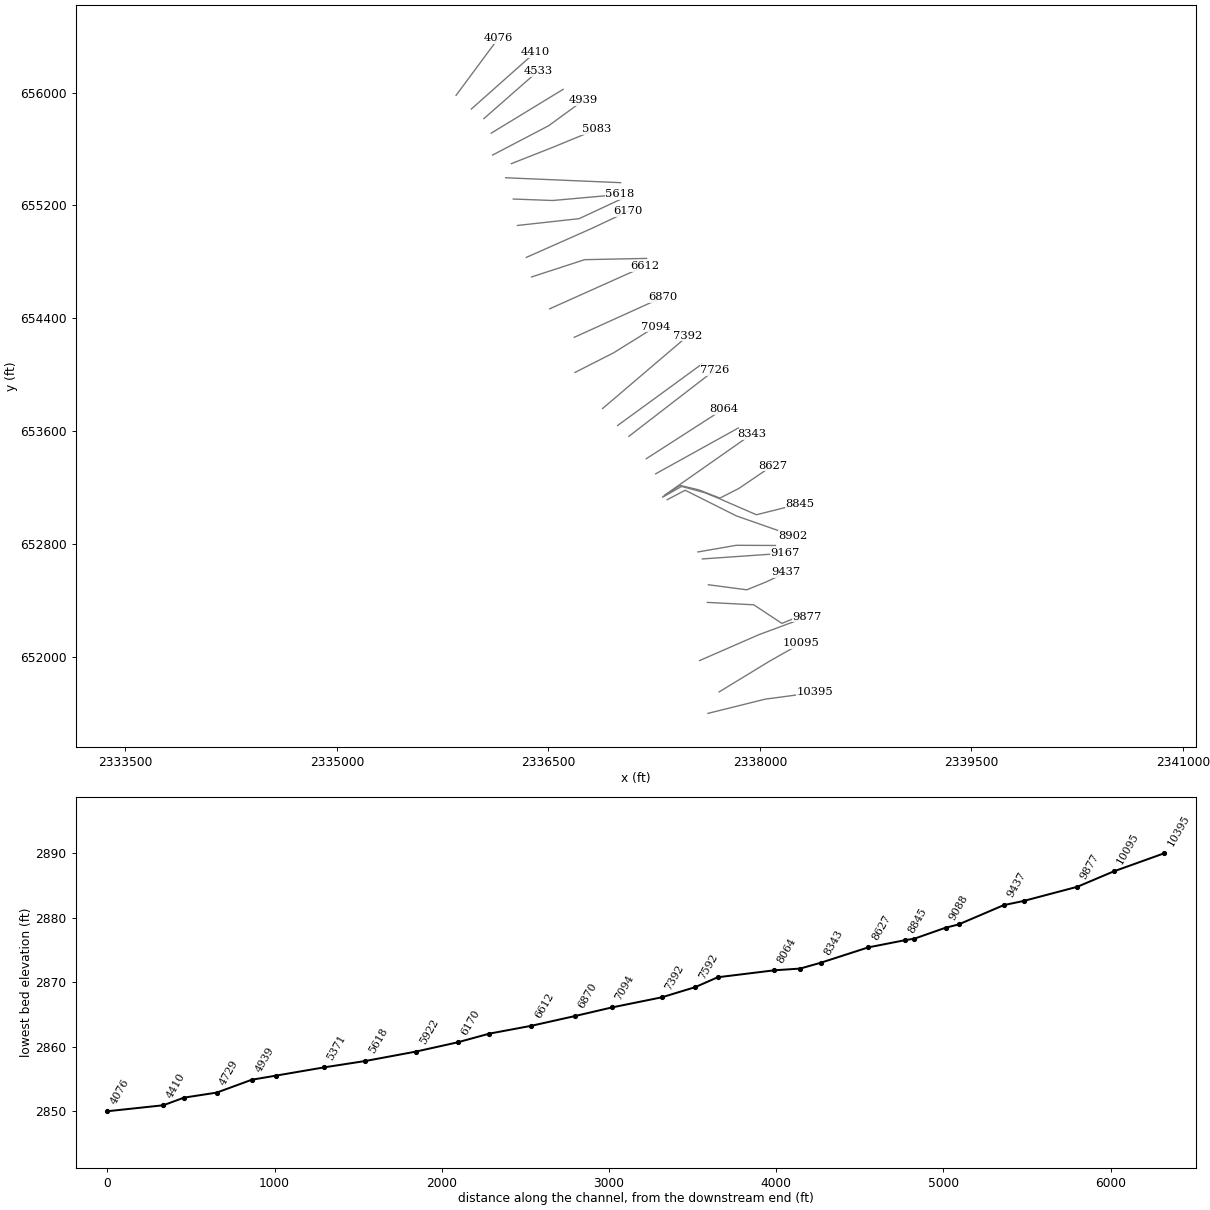
HEC-RAS study EFKGLADYFK.prj: EFKGLADYFK

--- EFKGLADYFK.g01 (geometry) --- (continued)

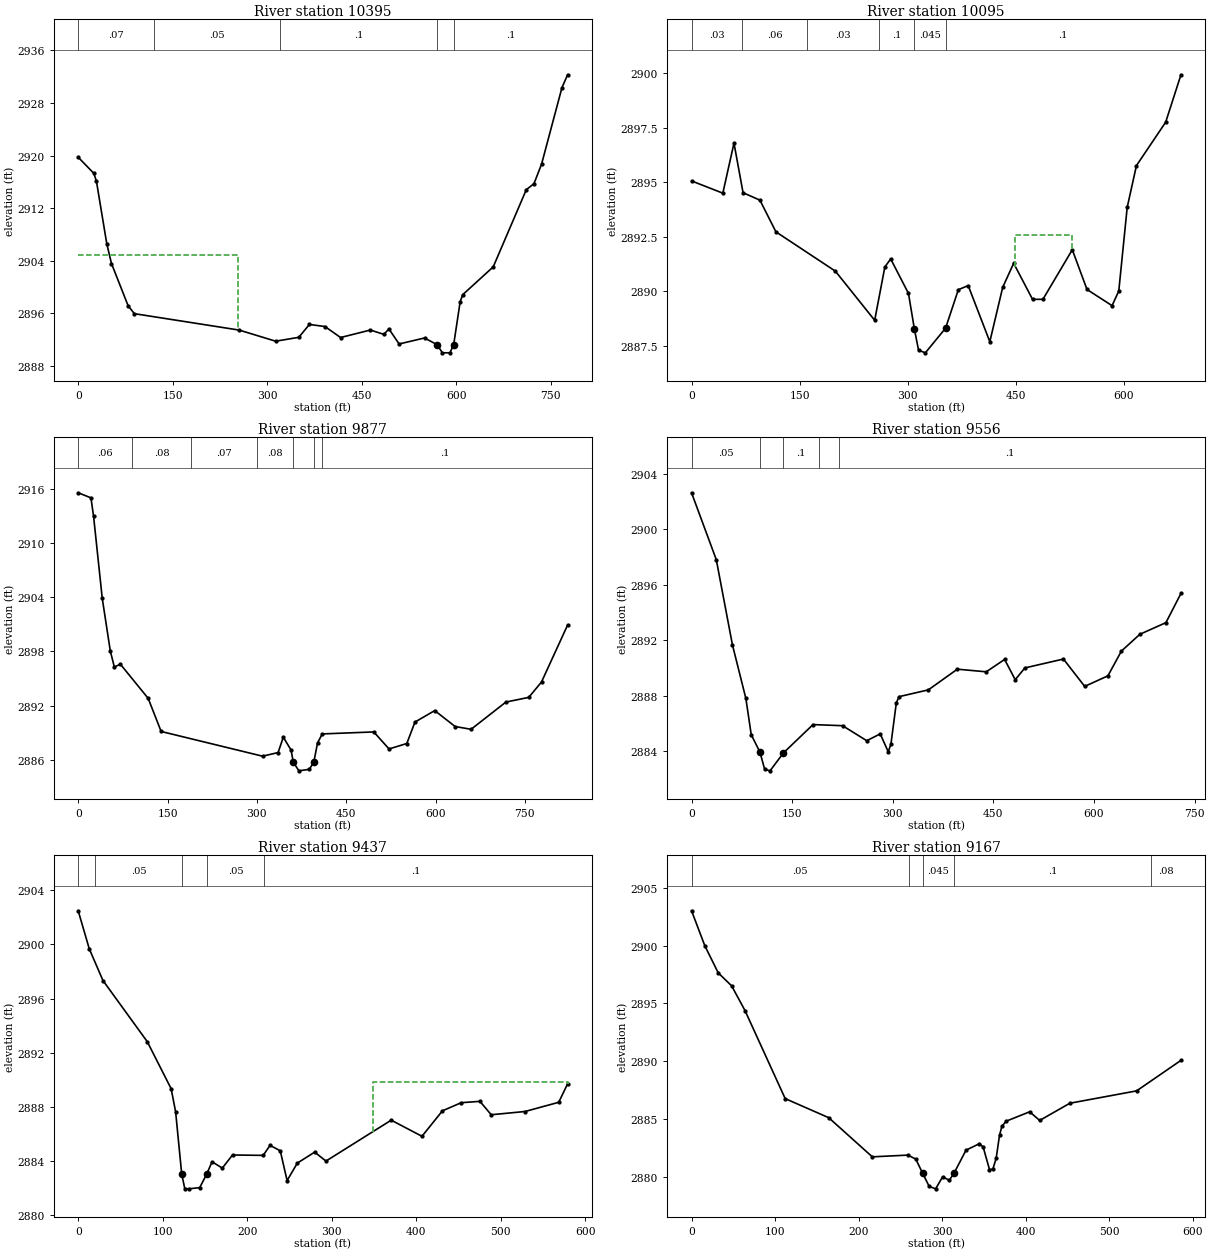
Type RM Length L Ch R = 1 ,10395   ,294.7,299.9,300.9
XS GIS Cut Line= 3
2337632.12954212651597.234251733 2338037.8043315651697.953509787
2338393.11949186651745.515381646
#Sta/Elev= 30
       0 2919.74    24.8 2917.29    28.9 2916.11    45.4 2906.55    52.8 2903.57
    79.2 2897.15    89.1 2895.94   255.6 2893.44   313.3 2891.75     350 2892.34
   366.9  2894.3   391.6 2893.98   416.3 2892.31   463.6 2893.45     485 2892.79
     493 2893.62   509.2 2891.33   549.5 2892.24   569.7 2891.21   577.8 2889.98
   589.9 2889.99  595.772891.239     606 2897.73   610.1 2898.83   658.5 2903.06
     711 2914.81   723.1 2915.71   735.2 2918.69   767.5 2930.31   776.5 2932.29
#Mann= 5 ,-1,0
       0     .07       0     120     .05       0     320      .1       0
   569.7    .045       0  595.77      .1       0
#XS Ineff= 2 , 0
           253.7  2904.8
Permanent Ineff=
       F       F
Bank Sta=569.7,595.77
XS Rating Curve= 0 ,0
Exp/Cntr(USF)=0,0
Exp/Cntr=0.3,0.1

Type RM Length L Ch R = 1 ,10095   ,220.8,217.5,214
XS GIS Cut Line= 3
 2337711.1118863651749.2872577692338066.42845763651965.916971752
2338295.35414107652095.636530925
#Sta/Elev= 30
       0 2895.06    43.4  2894.5    58.9 2896.79    71.5 2894.52    94.9 2894.18
   117.1 2892.73   199.6 2890.93   254.2 2888.68   268.3 2891.12   276.4 2891.49
   301.1 2889.91   309.2  2888.3   315.1 2887.31   324.5 2887.19   352.6 2888.32
   370.3 2890.08     384 2890.27     414  2887.7   431.9 2890.19   447.1 2891.29
   473.3 2889.64   487.7 2889.64   528.5 2891.91   548.9 2890.09   583.7 2889.35
     593 2890.02   604.7 2893.85   617.5 2895.76   658.1 2897.75   679.3 2899.92
#Mann= 6 ,-1,0
       0     .03       0      70     .06       0     160     .03       0
     260      .1       0   309.2    .045       0   352.6      .1       0
#XS Ineff= 1 ,-1
  449.52  528.66  2892.6
Permanent Ineff=
       F
Bank Sta=309.2,352.6
XS Rating Curve= 0 ,0
Exp/Cntr=0.3,0.1

Type RM Length L Ch R = 1 ,9877    ,326.2,321,310.1
XS GIS Cut Line= 3
2337572.54290995651971.5853518632337992.69329492652155.146199667
2338333.30064585652281.599228154
#Sta/Elev= 30
       0 2915.53    21.4 2914.97    25.8 2912.94    40.4 2903.86    53.9 2898.05
    60.7 2896.27    70.8 2896.59   117.5 2892.81   139.3 2889.15   309.5 2886.42
   335.7 2886.82   344.4 2888.52   357.5 2887.09   361.1 2885.77   370.6  2884.8
   388.1 2884.97   395.7 2885.77   401.9 2887.89   409.9 2888.88   496.3  2889.1
     522 2887.22   551.8 2887.82   565.5 2890.19   598.7 2891.46   632.9  2889.7
   659.7 2889.39   718.2  2892.4   756.6 2892.92     778 2894.62   821.8 2900.91
#Mann= 7 ,-1,0
       0     .06       0      90     .08       0     190     .07       0
     300     .08       0   361.1    .045       0   395.7     .08       0
     410      .1       0
Bank Sta=361.1,395.7
XS Rating Curve= 0 ,0
Exp/Cntr(USF)=0,0
Exp/Cntr=0.3,0.1

Type RM Length L Ch R = 1 ,9556    ,119.6,119.4,116.8
XS GIS Cut Line= 4
  2337627.286838652384.3554113842337957.05431673652367.286353154
2338156.54759746652235.4217856692338304.93355895652296.160977987
#Sta/Elev= 30
       0 2902.62    36.9  2897.8      61 2891.66      81 2887.81      89  2885.2
  102.022883.941     109 2882.71     117  2882.6     137 2883.89   181.1 2885.93
   225.2 2885.85   261.2 2884.77   281.3 2885.26   293.3 2883.97   297.3 2884.53
   305.3 2887.49   309.3 2887.94   353.1 2888.43   396.3 2889.92   439.4 2889.73
   466.8 2890.62   482.6 2889.16     497 2890.01   554.5 2890.65   586.2 2888.68
   620.8 2889.44   640.9 2891.22   668.4 2892.43   707.3 2893.27   729.7 2895.37
#Mann= 5 ,-1,0
       0     .05       0  102.02    .045       0     137      .1       0
     190     .08       0     220      .1       0
Bank Sta=102.02,137
XS Rating Curve= 0 ,0
Exp/Cntr=0.3,0.1

Type RM Length L Ch R = 1 ,9437    ,262.6,270.2,273.7
XS GIS Cut Line= 4
2337635.14928577652509.5922212172337907.18378661652473.658878491
2338046.98640391652530.3529531062338185.55648791652597.077321284
#Sta/Elev= 30
       0 2902.48    13.1 2899.67    29.3 2897.33    81.7 2892.82     110 2889.34
   115.3 2887.63   122.5 2883.03   126.1 2881.97   130.9 2881.95   143.8 2882.04
   152.12883.045   158.4 2883.95   170.5 2883.48   182.6 2884.45   218.9 2884.42
     227 2885.16   239.1 2884.76   247.2 2882.56   259.3 2883.85   279.8 2884.66
   293.2    2884   370.4 2887.02   406.8 2885.83     431 2887.71   453.2 2888.31
   475.4 2888.41   488.7 2887.42   528.7 2887.66   568.6 2888.34   579.1  2889.7
#Mann= 5 ,-1,0
       0     .06       0      20     .05       0   122.5    .045       0
   152.1     .05       0     220      .1       0
#XS Ineff= 2 , 0
                          349.01         2889.86
Permanent Ineff=
       F       F
Bank Sta=122.5,152.1
XS Rating Curve= 0 ,0
Exp/Cntr(USF)=0,0
Exp/Cntr=0.3,0.1

Type RM Length L Ch R = 1 ,9167    ,79.1,78.2,75.9
XS GIS Cut Line= 2
2337592.32731582652692.6347725122338176.81413057652733.167838722
#Sta/Elev= 30
       0 2903.02    15.9 2899.99    31.9 2897.65      48 2896.52      64 2894.38
   112.1 2886.76   164.2 2885.11   216.4 2881.72   259.1 2881.87   268.5 2881.52
   276.5 2880.32   284.5 2879.16   292.2 2878.95   300.6 2879.99   308.6 2879.69
  314.292880.312   328.6  2882.3   344.7 2882.86   349.1 2882.57   356.7 2880.62
   360.7 2880.65   364.7  2881.6   368.7 2883.59   371.6 2884.38   376.8 2884.81
   404.8 2885.62   416.8 2884.87   452.9 2886.36   532.8 2887.43   585.9 2890.07
#Mann= 5 ,-1,0
       0     .05       0     260      .1       0   276.5    .045       0
  314.29      .1       0     550     .08       0
Bank Sta=276.5,314.29
XS Rating Curve= 0 ,0
Exp/Cntr(USF)=0,0
Exp/Cntr=0.3,0.1

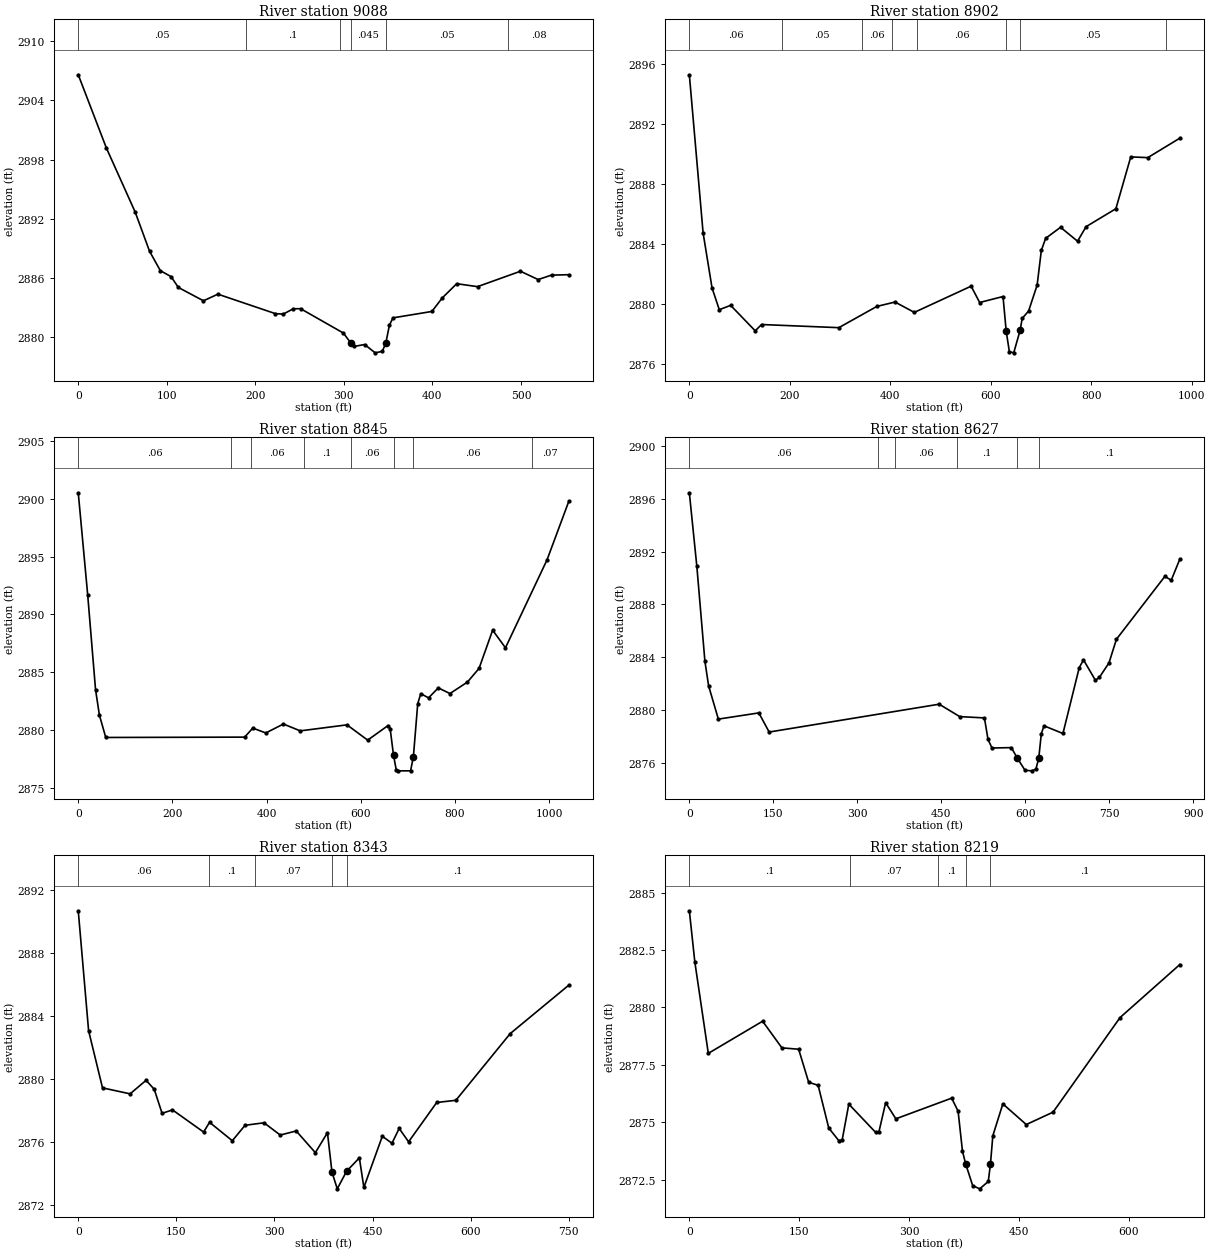
Type RM Length L Ch R = 1 ,9088    ,193.8,186.3,182.3
XS GIS Cut Line= 3
2337560.83301693652742.0566677492337832.27948226652789.342925806
2338110.74376212652788.166925806
#Sta/Elev= 30
       0 2906.59    31.8 2899.17    64.3 2892.69    80.5 2888.73    92.7 2886.76
   104.9 2886.15     113 2885.06   141.4 2883.71   157.7 2884.38   222.6 2882.41
   231.4 2882.36   242.9  2882.9   251.1 2882.91   299.5 2880.44   307.5 2879.47
   311.4 2879.09   323.5 2879.28   335.3 2878.44   343.4 2878.59   347.4 2879.45
   351.4 2881.23   355.4 2881.98   399.4 2882.63     411 2883.99   427.4 2885.44
   450.9 2885.14   499.4  2886.7   519.4 2885.86   534.5 2886.31     554 2886.35
#Mann= 6 ,-1,0
       0     .05       0     190      .1       0  295.53     .05       0
   307.5    .045       0   347.4     .05       0  485.53     .08       0
Bank Sta=307.5,347.4
XS Rating Curve= 0 ,0
Exp/Cntr=0.3,0.1

Type RM Length L Ch R = 1 ,8902    ,58.8,57.4,56.8
XS GIS Cut Line= 4
2337343.38303903653112.973636908 2337470.7281172653179.842228351
2337833.34375064652997.9145914362338236.44441854652856.935491085
#Sta/Elev= 30
       0  2895.3    27.4 2884.74    45.2 2881.07    59.6 2879.62    82.2 2879.91
   131.1 2878.21   143.8 2878.63   297.6 2878.42   373.4 2879.84   409.5 2880.13
   447.9 2879.44     561 2881.19     578  2880.1   624.5  2880.5   630.8 2878.19
   637.1 2876.82   645.8 2876.74   658.5 2878.24   662.7 2879.04   675.4 2879.53
   692.4 2881.26   700.8 2883.58   709.3 2884.38     739 2885.12   772.9 2884.19
   789.8 2885.16   849.2 2886.36   878.8 2889.82   912.7 2889.77   976.6 2891.07
#Mann= 8 ,-1,0
       0     .06       0  183.83     .05       0  343.83     .06       0
  403.83     .05       0  453.83     .06       0   630.8    .045       0
   658.5     .05       0  949.53     .08       0
Bank Sta=630.8,658.5
XS Rating Curve= 0 ,0
Exp/Cntr(USF)=0,0
Exp/Cntr=0.3,0.1

Type RM Length L Ch R = 1 ,8845    ,197,218.1,237.1
XS GIS Cut Line= 6
 2337310.6272441653131.2107360762337445.57022244653206.977636704
2337611.47266885653161.8357194342337706.04982334653123.104122834
2337975.77626696653006.0736848942338285.05570966653083.393545568
#Sta/Elev= 30
       0  2900.5    20.1 2891.66    36.7 2883.51    44.9 2881.31    58.4 2879.38
   353.4 2879.41   370.6 2880.19   398.3 2879.77   435.6 2880.54   471.5 2879.95
   570.7 2880.47   614.6 2879.15   657.9 2880.41   662.3 2880.15  669.542877.828
   675.4 2876.56   679.7  2876.5   705.7  2876.5   711.7 2877.72   720.9  2882.3
   727.4 2883.16   743.9  2882.8   764.6 2883.66   789.3 2883.17   826.4 2884.16
   851.1 2885.34     880 2888.64   907.2 2887.12   995.5 2894.71  1041.7 2899.76
#Mann= 8 ,-1,0
       0     .06       0  324.76     .05       0  366.69     .06       0
  478.89      .1       0  578.89     .06       0  669.54    .045       0
   711.7     .06       0  962.91     .07       0
Bank Sta=669.54,711.7
XS Rating Curve= 0 ,0
Exp/Cntr(USF)=0,0
Exp/Cntr=0.3,0.1

Type RM Length L Ch R = 1 ,8627    ,276.2,283.9,283.1
XS GIS Cut Line= 6
2337316.95844695653136.7651100562337434.02791234653214.078338105
2337567.33666342653182.552619942  2337716.858641653124.004857639
2337852.99343391653193.6400897852338088.82460848653353.828680893
#Sta/Elev= 30
       0 2896.46    13.4 2890.88    27.8 2883.69    34.4 2881.83    51.8 2879.31
   124.1 2879.78   142.5 2878.33   446.1 2880.44   482.8  2879.5   526.9  2879.4
   533.3 2877.77   540.4 2877.12     575 2877.15   585.22876.381   599.4 2875.43
   611.3 2875.39   618.8 2875.52   623.92876.351   628.5 2878.21   633.3  2878.8
   667.1 2878.22   696.2 2883.21   703.8  2883.8   725.1 2882.25   732.3 2882.48
   749.3 2883.57   762.6 2885.36     849 2890.12   860.5 2889.84   875.9 2891.44
#Mann= 6 ,-1,0
       0     .06       0  337.28     .05       0  367.28     .06       0
  477.86      .1       0   585.2    .045       0   623.9      .1       0
Bank Sta=585.2,623.9
XS Rating Curve= 0 ,0
Exp/Cntr=0.3,0.1

Type RM Length L Ch R = 1 ,8343    ,123,123.7,122.3
XS GIS Cut Line= 2
2337327.22947891653146.4754970662337941.61695304653577.050325248
#Sta/Elev= 30
       0 2890.69    15.8 2883.07    37.1 2879.43    79.3 2879.05   103.7 2879.91
   116.2 2879.34   128.2 2877.81   144.1 2878.03   191.7 2876.62   200.8 2877.24
   235.6 2876.07   255.1 2877.05   284.1 2877.21   308.9 2876.43   333.3 2876.69
   362.6 2875.31   381.1 2876.58     388 2874.08   396.1 2873.01   410.4 2874.13
   429.9 2874.98   436.8  2873.1     465 2876.35   479.8 2875.91   490.8 2876.85
   505.2    2876   548.2  2878.5   577.5 2878.64   660.6 2882.88   750.2 2885.96
#Mann= 5 ,-1,0
       0     .06       0     200      .1       0     270     .07       0
     388    .045       0   410.4      .1       0
Bank Sta=388,410.4
XS Rating Curve= 0 ,0
Exp/Cntr(USF)=0,0
Exp/Cntr=0.3,0.1

Type RM Length L Ch R = 1 ,8219    ,152.6,154.8,155.4
XS GIS Cut Line= 2
2337261.62478314653296.644727742 2337847.6584153653621.354064729
#Sta/Elev= 30
       0 2884.21     7.5 2881.98    25.9    2878   100.1  2879.4   126.4 2878.24
   149.3 2878.18     163 2876.74   175.9 2876.61   190.4 2874.75   204.1  2874.2
   208.7 2874.22   217.8 2875.79   254.4 2874.56     259 2874.59   268.1 2875.85
   282.1 2875.15   358.3 2876.05   367.1 2875.48     373 2873.75   377.32873.197
     387 2872.24   396.6  2872.1   408.3 2872.42   411.3 2873.19   414.5 2874.41
   428.2  2875.8   460.2  2874.9   496.8 2875.44   588.3 2879.56     670 2881.87
#Mann= 5 ,-1,0
       0      .1       0     220     .07       0     340      .1       0
   377.3    .045       0   411.3      .1       0
Bank Sta=377.3,411.3
XS Rating Curve= 0 ,0
Exp/Cntr(USF)=0,0
Exp/Cntr=0.3,0.1

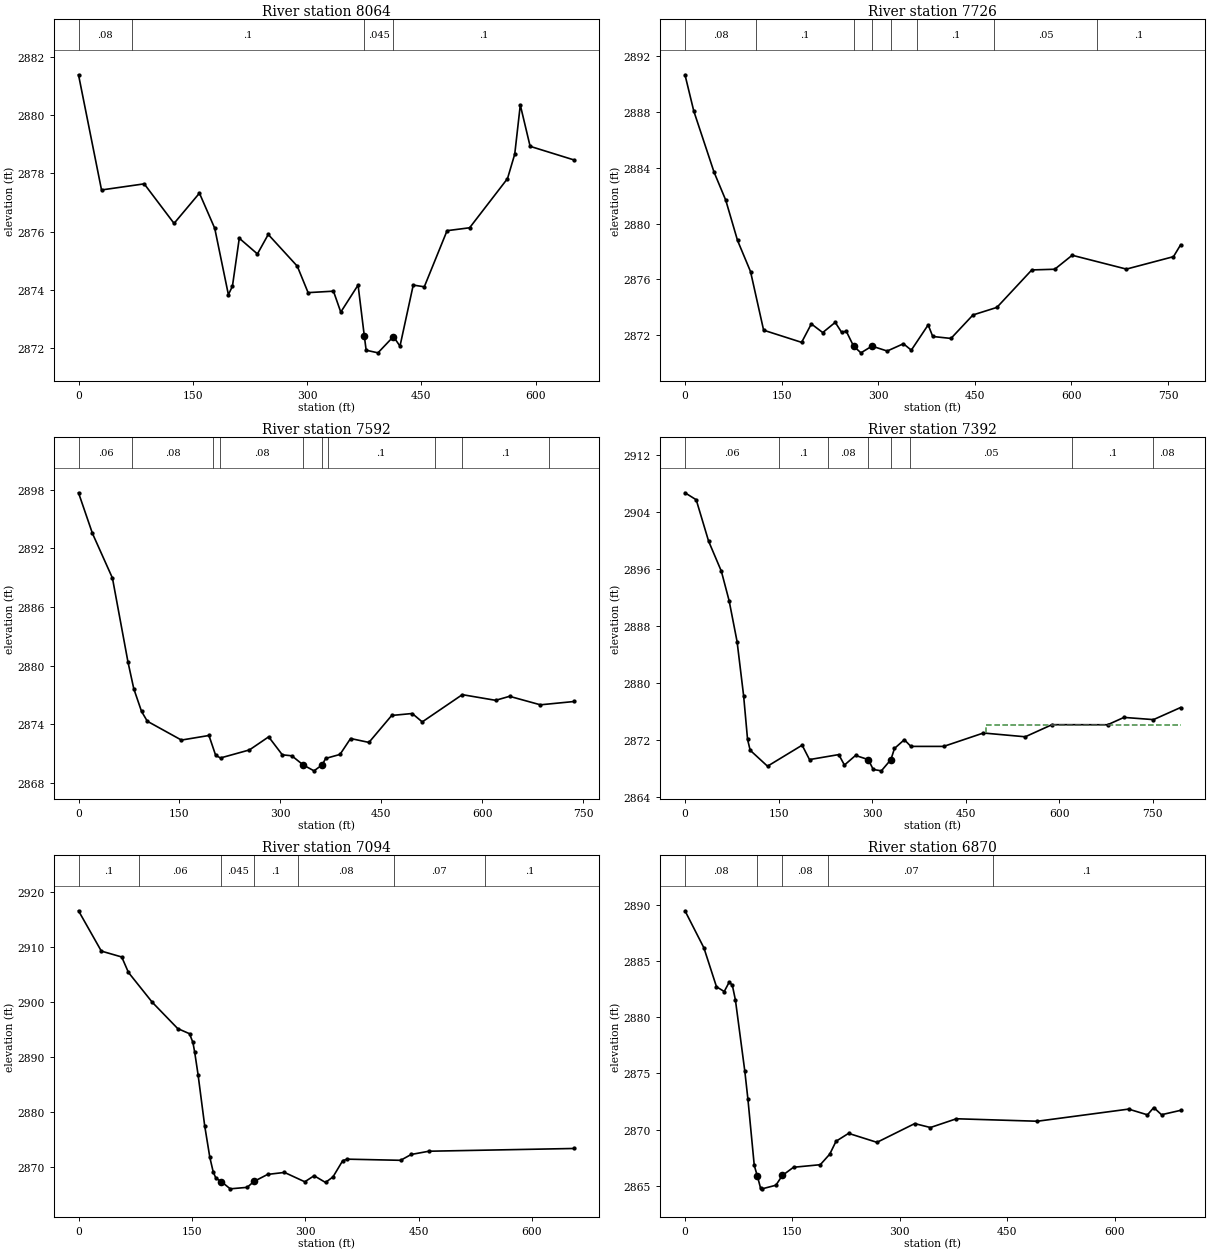
Type RM Length L Ch R = 1 ,8064    ,328.6,338.5,333.2
XS GIS Cut Line= 2
2337194.74882443653403.4681538192337741.79538888653755.437278067
#Sta/Elev= 30
       0 2881.39    30.2 2877.43    86.2 2877.64   125.4 2876.28   158.7 2877.32
   178.8 2876.11   196.7 2873.83     202 2874.12     211 2875.77   234.8 2875.23
     249  2875.9   287.1 2874.81   301.3  2873.9   334.6 2873.95   344.2 2873.23
   366.9 2874.16  375.032872.421   377.5 2871.92     393 2871.83   413.3 2872.39
   421.9 2872.06   439.3 2874.16   453.8  2874.1   483.7 2876.03   513.3 2876.13
     563 2877.82   572.5 2878.66   579.8 2880.35   592.7 2878.93   650.5 2878.46
#Mann= 4 ,-1,0
       0     .08       0      70      .1       0  375.03    .045       0
   413.3      .1       0
Bank Sta=375.03,413.3
XS Rating Curve= 0 ,0
Exp/Cntr=0.3,0.1

Type RM Length L Ch R = 1 ,7726    ,121.2,134.1,119.8
XS GIS Cut Line= 2
2337071.59236669653562.5342172452337680.94554904654032.600762145
#Sta/Elev= 30
       0 2890.64    13.7 2888.04    45.1 2883.68    63.3 2881.67    81.6 2878.79
   101.8 2876.56   122.1 2872.37   181.1  2871.5   196.2 2872.82   213.9  2872.2
   233.3 2872.93   243.2 2872.22   250.4  2872.3   261.8 2871.23   273.2 2870.75
   290.3 2871.23     314 2870.88   339.2  2871.4   351.4 2870.94   377.6 2872.75
   384.7 2871.92     413 2871.78   447.2 2873.46   484.3    2874   538.5 2876.68
   574.1 2876.73   601.2 2877.73   685.4 2876.74   758.5 2877.63   769.6 2878.48
#Mann= 8 ,-1,0
       0     .08       0     110      .1       0   261.8    .045       0
   290.3      .1       0     320     .08       0     360      .1       0
     480     .05       0     640      .1       0
Bank Sta=261.8,290.3
XS Rating Curve= 0 ,0
Exp/Cntr(USF)=0,0
Exp/Cntr=0.3,0.1

Type RM Length L Ch R = 1 ,7592    ,196,199.8,196.5
XS GIS Cut Line= 3
2336991.46926515653639.1427823322337362.85541572653909.757315882
2337586.35554992654073.140567911
#Sta/Elev= 30
       0 2897.69    20.7 2893.53    50.4 2888.96    73.5 2880.36    82.1 2877.63
    93.6 2875.31   102.2  2874.3   152.9 2872.37   193.8 2872.84   203.8  2870.8
     211 2870.54   253.9 2871.36   282.5  2872.7   302.8 2870.86   316.9 2870.76
     3342869.815   349.9 2869.22   362.2 2869.84   367.1 2870.49   388.5  2870.9
   404.2 2872.53   431.5 2872.13   465.3 2874.89   495.8 2875.09   510.7 2874.23
   570.2 2877.02   619.7 2876.44   640.4 2876.85   686.2 2875.98   736.4 2876.32
#Mann= 10 ,-1,0
       0     .06       0      80     .08       0     200      .1       0
     210     .08       0     334    .045       0   362.2     .08       0
     370      .1       0  529.52     .05       0  569.52      .1       0
  699.52     .08       0
Bank Sta=334,362.2
XS Rating Curve= 0 ,0
Exp/Cntr=0.3,0.1

Type RM Length L Ch R = 1 ,7392    ,307.1,298.1,294.4
XS GIS Cut Line= 2
2336884.61869939653759.3413550062337489.26813206654274.780215639
#Sta/Elev= 30
       0 2906.67      18 2905.69    37.9 2899.87    58.3 2895.66    70.7 2891.54
    83.5 2885.79      94 2878.18   100.3 2872.06   104.5 2870.53   132.3 2868.29
   187.8 2871.24   199.6 2869.22   246.5 2869.92   255.6 2868.45   273.4  2869.8
   293.8 2869.22   301.8 2867.83   314.8 2867.64   330.1 2869.22   335.8 2870.78
   351.6 2872.01   362.1 2871.07   414.7 2871.07   478.4 2872.95   545.4 2872.42
   588.3 2874.12   677.5 2874.11   703.7 2875.14     751 2874.83   794.5 2876.53
#Mann= 8 ,-1,0
       0     .06       0     150      .1       0     230     .08       0
   293.8    .045       0   330.1     .07       0     360     .05       0
     620      .1       0     750     .08       0
#XS Ineff= 2 , 0
                          483.11         2874.14
Permanent Ineff=
       F       F
Bank Sta=293.8,330.1
XS Rating Curve= 0 ,0
Exp/Cntr(USF)=0,0
Exp/Cntr=0.3,0.1

Type RM Length L Ch R = 1 ,7094    ,224.4,223.3,222.2
XS GIS Cut Line= 3
2336689.21604748 654015.523882172336963.34841572654154.921666126
     2337259.219654339.082851055
#Sta/Elev= 30
       0 2916.56    30.2 2909.24    57.2 2908.17    66.1 2905.36    97.6 2899.95
   131.3 2895.17   146.9 2894.24   151.4 2892.65   153.7 2890.94   158.2 2886.83
     167 2877.52   173.8 2871.78   178.3 2869.13   181.9 2867.99  188.862867.401
   200.8 2866.07   223.2 2866.34   232.2 2867.41   250.3 2868.69   272.6 2869.05
   299.5 2867.35   311.8 2868.45   326.9 2867.23   336.8 2868.24   349.7 2871.19
   355.6 2871.46   426.3 2871.25   440.3 2872.31   463.7  2872.9     656  2873.4
#Mann= 7 ,-1,0
       0      .1       0      80     .06       0  188.86    .045       0
   232.2      .1       0     290     .08       0  417.54     .07       0
  537.54      .1       0
Bank Sta=188.86,232.2
XS Rating Curve= 0 ,0
Exp/Cntr=0.3,0.1

Type RM Length L Ch R = 1 ,6870    ,259.3,258.7,257.8
XS GIS Cut Line= 2
2336684.09274639654264.7927945342337314.31832385654550.331891118
#Sta/Elev= 30
       0 2889.48    26.4 2886.18      44 2882.71    54.8 2882.29    61.6 2883.11
      66 2882.88    70.4 2881.54    83.5 2875.21    87.9 2872.68    96.7 2866.81
   101.1 2865.84   105.5 2864.79   107.6 2864.72   126.9 2865.04   135.9 2865.91
   151.5 2866.64   188.9 2866.87   202.1 2867.81   210.9 2868.96   228.4 2869.66
     268 2868.86   320.7 2870.53   342.6 2870.18   378.9 2870.96   491.9 2870.74
   619.3 2871.82   645.6 2871.31   654.4 2871.96   665.2 2871.32   691.9 2871.71
#Mann= 5 ,-1,0
       0     .08       0   101.1    .045       0   135.9     .08       0
     200     .07       0     430      .1       0
Bank Sta=101.1,135.9
XS Rating Curve= 0 ,0
Exp/Cntr(USF)=0,0
Exp/Cntr=0.3,0.1

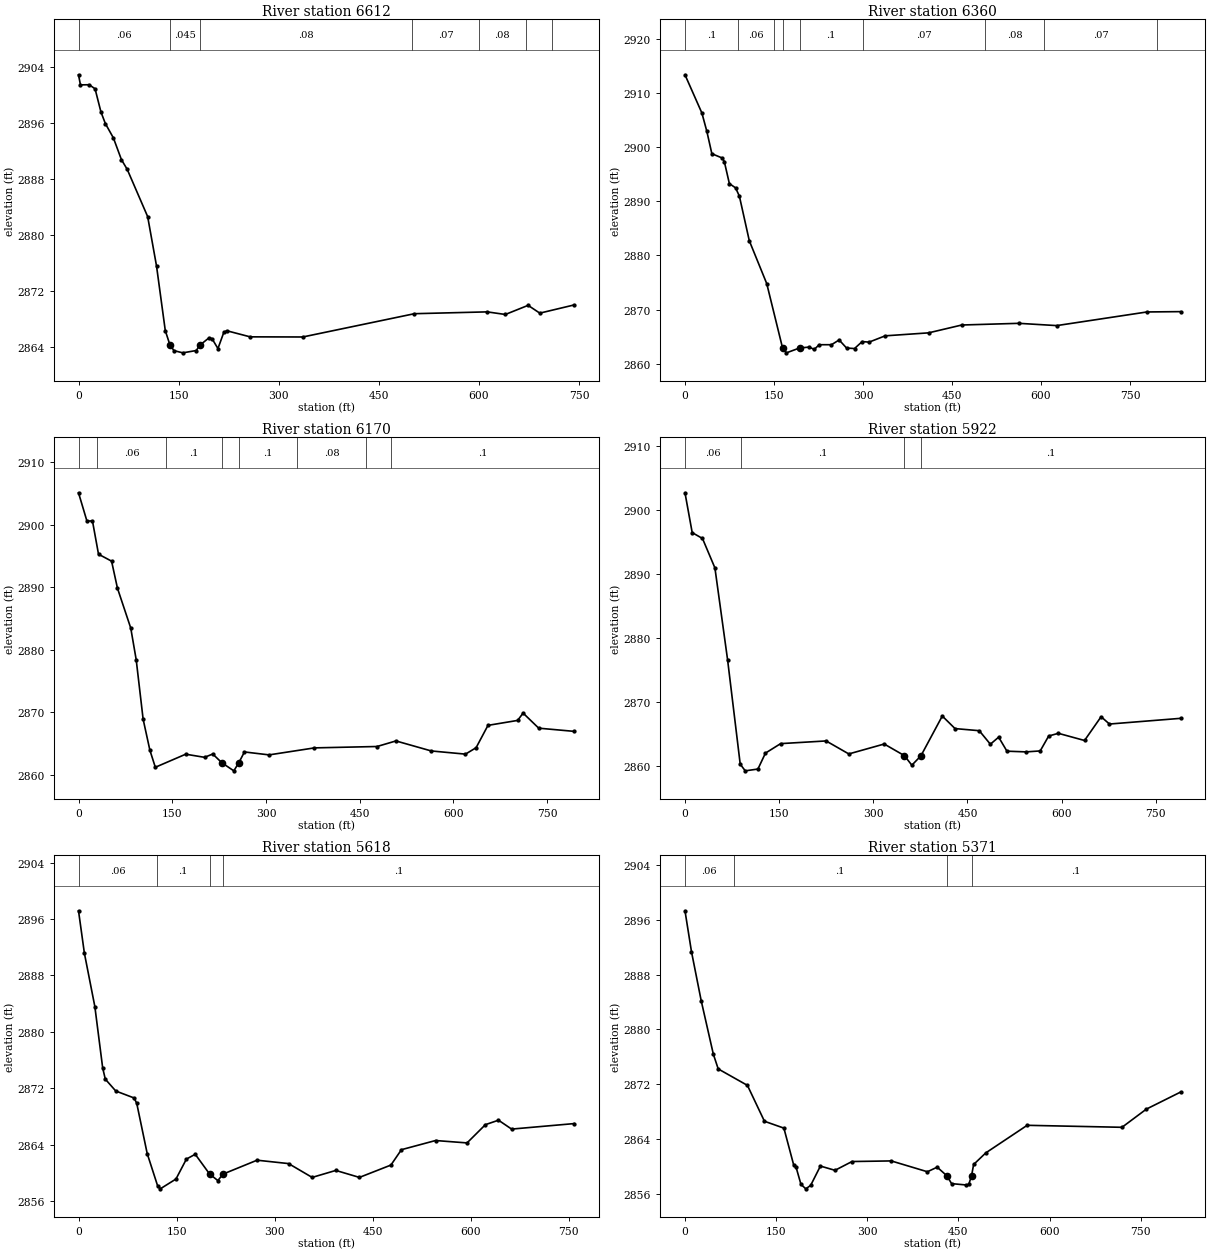
Type RM Length L Ch R = 1 ,6612    ,250.9,251.6,248.7
XS GIS Cut Line= 2
2336509.53695143654466.6917613772337187.18704834654770.444190757
#Sta/Elev= 30
       0 2902.86     2.9 2901.42      16 2901.44    24.8 2900.86    33.6 2897.56
    40.2 2895.91    52.3 2893.85    64.3 2890.76      73 2889.37   103.6 2882.64
   116.9 2875.59     130 2866.39   137.1 2864.31   143.1 2863.53   156.3 2863.22
   176.4 2863.55   181.82864.309   195.8 2865.38   200.1 2865.23   208.9 2863.83
   217.7 2866.14   222.1 2866.37   257.1  2865.5     336 2865.48   503.3  2868.8
   612.2 2869.06   639.5 2868.69   673.6 2869.99   691.1 2868.88   742.6 2870.05
#Mann= 7 ,-1,0
       0     .06       0   137.1    .045       0   181.8     .08       0
     500     .07       0     600     .08       0     670     .07       0
     710      .1       0
Bank Sta=137.1,181.8
XS Rating Curve= 0 ,0
Exp/Cntr=0.3,0.1

Type RM Length L Ch R = 1 ,6360    ,185,190,187.5
XS GIS Cut Line= 3
 2336381.0885298654692.8052916322336757.27495863654815.179190168
2337196.91452003654824.243923393
#Sta/Elev= 30
       0 2913.35    28.5 2906.29    36.9 2902.88    45.3 2898.77      63 2897.97
    66.3 2897.32    74.8 2893.26    85.3 2892.46    91.7 2890.93   108.4  2882.7
   137.8 2874.78   164.6 2862.83     171    2862   193.2  2862.9   209.4 2863.06
   217.8 2862.63   226.2  2863.5   246.9  2863.5   259.8 2864.38   272.3 2862.89
   285.7 2862.79   298.6 2864.08   310.3 2863.98   337.4 2865.14   410.5 2865.69
   466.5 2867.14   562.5 2867.45   626.5 2867.03   778.6 2869.55   835.3 2869.61
#Mann= 9 ,-1,0
       0      .1       0      90     .06       0     150      .1       0
   164.6    .045       0   193.2      .1       0     300     .07       0
  505.59     .08       0  605.59     .07       0  795.59      .1       0
Bank Sta=164.6,193.2
XS Rating Curve= 0 ,0
Exp/Cntr(USF)=0,0
Exp/Cntr=0.3,0.1

Type RM Length L Ch R = 1 ,6170    ,254.4,247.9,246.9
XS GIS Cut Line= 3
2336343.78815598654831.3063964842336807.92132598655036.953331801
2337066.03529906655158.845770956
#Sta/Elev= 30
       0  2905.1    13.5 2900.57    22.3 2900.61      32 2895.28    52.9 2894.17
    62.3 2889.85    83.6 2883.47    92.3 2878.42   103.4  2868.9   114.2 2863.95
   122.9 2861.22   171.5 2863.31   201.7 2862.81   214.8 2863.34   229.32861.946
   248.5 2860.65   256.3 2861.91   265.5 2863.67   304.9  2863.2   377.6 2864.32
   477.7 2864.54   507.9 2865.43   564.4 2863.83   619.2 2863.32   636.2 2864.35
   655.2 2867.92   702.6 2868.71   711.4 2869.88   736.4 2867.47   793.1 2866.96
#Mann= 8 ,-1,0
       0      .1       0      30     .06       0     140      .1       0
   229.3    .045       0   256.3      .1       0     350     .08       0
     460     .07       0     500      .1       0
Bank Sta=229.3,256.3
XS Rating Curve= 0 ,0
Exp/Cntr=0.3,0.1

Type RM Length L Ch R = 1 ,5922    ,301,304.2,302.8
XS GIS Cut Line= 3
2336280.71565165655057.8705418012336717.87352543 655106.02478584
2337035.04436484655253.585758615
#Sta/Elev= 30
       0 2902.65    11.5 2896.43    27.9 2895.51    47.7 2890.91    67.9 2876.55
      88 2860.26      96 2859.22   116.2  2859.5   128.2 2861.99   152.4 2863.47
   224.8 2863.89     261 2861.86   317.4 2863.41   349.6 2861.59   361.4  2860.1
   375.9 2861.57   409.9 2867.78   430.2 2865.82   468.8 2865.49   486.5 2863.38
   499.7 2864.48   512.9 2862.29   543.3 2862.18   565.9 2862.33   579.4 2864.66
   594.8 2865.08   636.5 2863.96   662.9 2867.67   676.2 2866.53   789.6 2867.42
#Mann= 4 ,-1,0
       0     .06       0      90      .1       0   349.6    .045       0
   375.9      .1       0
Bank Sta=349.6,375.9
XS Rating Curve= 0 ,0
Exp/Cntr(USF)=0,0
Exp/Cntr=0.3,0.1

Type RM Length L Ch R = 1 ,5618    ,234.8,247,255
XS GIS Cut Line= 3
2336251.16737549655245.3712676472336530.62884974655234.911173718
2337007.48763651655277.488336764
#Sta/Elev= 30
       0 2897.17       9 2891.15      25 2883.59      37 2874.88      41  2873.3
      57 2871.62    85.1 2870.63    89.1 2869.87   105.1 2862.75   121.1 2858.16
   125.1 2857.75   149.1 2859.14   165.1 2861.97   178.6 2862.65   200.5 2859.86
   213.2 2858.92   221.1 2859.84   273.2 2861.81   321.4 2861.33   357.5 2859.37
   393.7 2860.36   429.8 2859.37     478 2861.12   494.1  2863.3   546.3  2864.6
   594.5 2864.26   622.6 2866.85   642.6 2867.48   662.7 2866.22   758.4    2867
#Mann= 4 ,-1,0
       0     .06       0     120      .1       0   200.5    .045       0
   221.1      .1       0
Bank Sta=200.5,221.1
XS Rating Curve= 0 ,0
Exp/Cntr=0.3,0.1

Type RM Length L Ch R = 1 ,5371    ,278.7,287.6,299.9
XS GIS Cut Line= 2
 2336197.4917504655396.2210611182337012.50191464655361.344500036
#Sta/Elev= 30
       0 2897.29    10.7 2891.33    26.7 2884.18    46.7 2876.38    54.7 2874.24
   102.8 2871.84   130.8 2866.61   162.8 2865.61   178.8 2860.28   182.9  2859.9
   190.9 2857.41   198.9 2856.76   206.9 2857.27   222.9 2860.08   246.9 2859.46
   274.9 2860.74   339.5 2860.83     399 2859.25   415.1 2859.92   431.1 2858.66
   438.8 2857.52   463.1 2857.32   467.1  2857.4   471.72858.687   475.1 2860.31
   495.1    2862   563.2 2866.02   719.3 2865.73   759.4 2868.38   815.8 2870.87
#Mann= 4 ,-1,0
       0     .06       0      80      .1       0   431.1    .045       0
   471.7      .1       0
Bank Sta=431.1,471.7
XS Rating Curve= 0 ,0
Exp/Cntr(USF)=0,0
Exp/Cntr=0.3,0.1

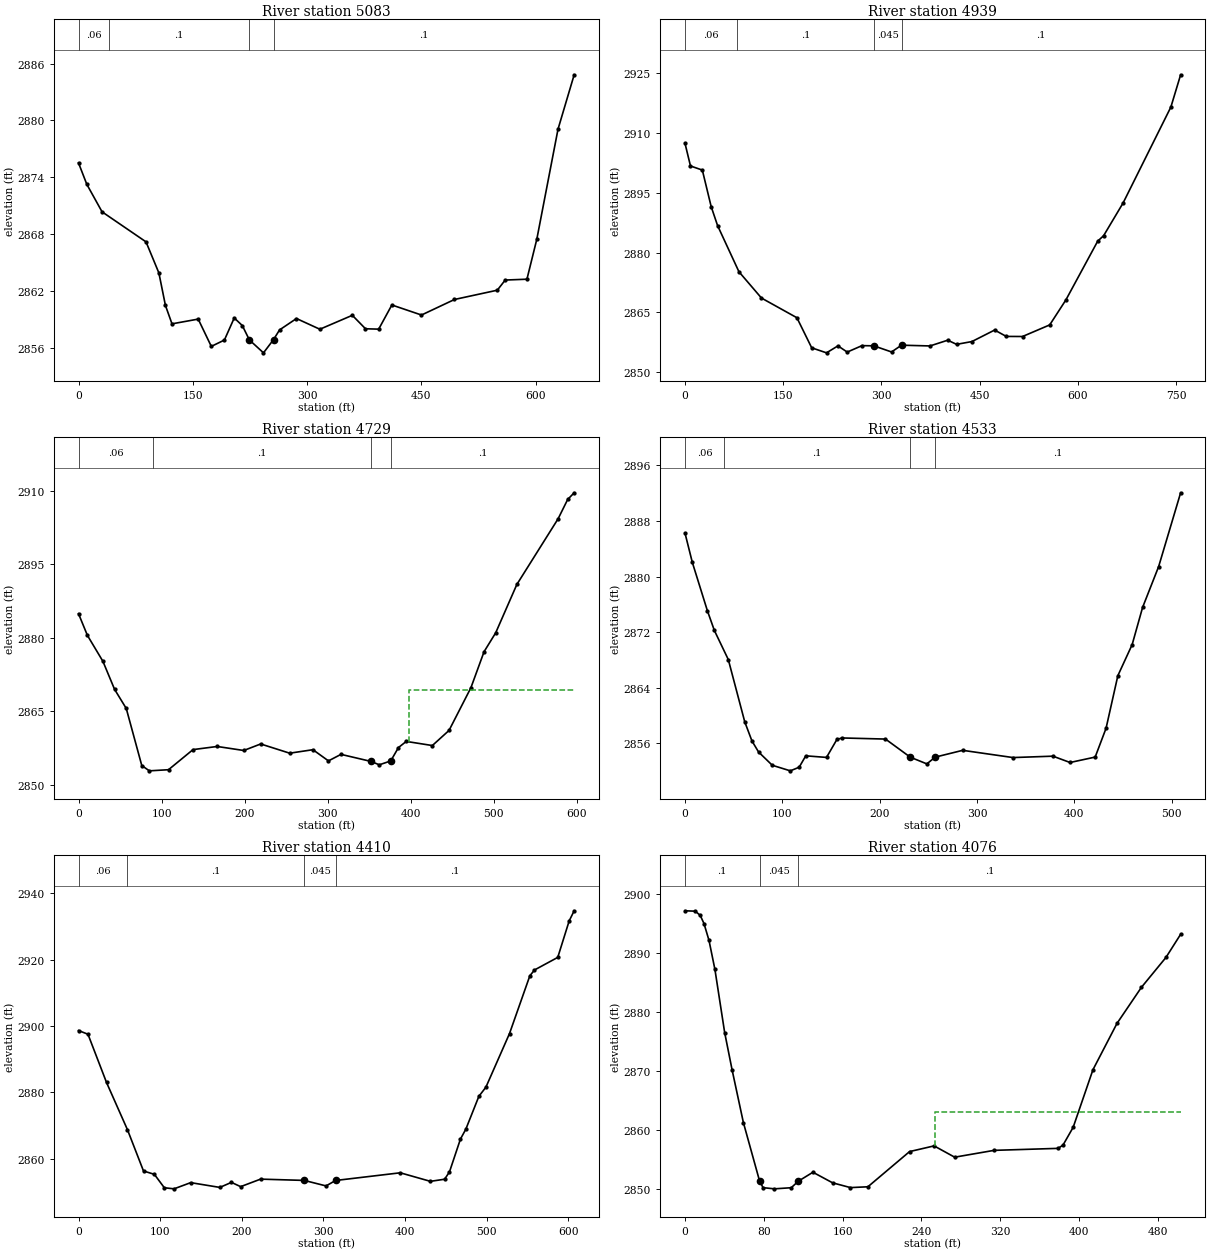
Type RM Length L Ch R = 1 ,5083    ,142.7,144.8,144.6
XS GIS Cut Line= 3
2336238.01977455655496.4767934012336528.42042251655610.854652564
2336841.51822196655739.603703267
#Sta/Elev= 30
       0 2875.52    10.9 2873.26    30.9 2870.36    88.6 2867.19   105.5 2863.91
   114.1 2860.48   122.7 2858.54   157.1 2859.04   174.3 2856.16   191.5 2856.83
   204.4 2859.16     215 2858.36   224.3 2856.84   242.8 2855.48     256 2856.88
   263.9  2857.9   286.1  2859.1   316.8 2857.97   359.4 2859.44   376.7 2858.02
     394 2857.98   411.3 2860.53   450.2 2859.47   493.5 2861.11   549.7 2862.09
   560.1 2863.16   588.6 2863.25   601.6 2867.48   629.4 2879.08   650.6 2884.82
#Mann= 4 ,-1,0
       0     .06       0      40      .1       0   224.3    .045       0
     256      .1       0
Bank Sta=224.3,256
XS Rating Curve= 0 ,0
Exp/Cntr=0.3,0.1

Type RM Length L Ch R = 1 ,4939    ,218.5,209.9,206.4
XS GIS Cut Line= 3
2336104.69779208 655557.433900962336502.41296232 655765.46952847
2336751.23988935655946.990811298
#Sta/Elev= 30
       0 2907.44     8.4 2901.74    26.5 2900.71      40 2891.54    49.8 2886.77
    82.4 2875.19   116.8 2868.59   170.9 2863.65   193.5  2856.1   216.1 2854.84
   233.6 2856.59   247.7 2855.03   270.3 2856.65   288.3  2856.6   315.4 2855.06
   330.6 2856.76   374.1 2856.57   401.2 2858.01   414.7 2856.97   438.1 2857.67
   472.8 2860.56   490.6 2858.96   515.4 2858.94   556.9 2861.85   581.6 2868.12
   630.2 2882.88   639.2 2884.24   668.9 2892.44   741.9 2916.53   756.8 2924.63
#Mann= 4 ,-1,0
       0     .06       0      80      .1       0   288.3    .045       0
   330.6      .1       0
Bank Sta=288.3,330.6
XS Rating Curve= 0 ,0
Exp/Cntr(USF)=0,0
Exp/Cntr=0.3,0.1

Type RM Length L Ch R = 1 ,4729    ,195.3,195.9,198
XS GIS Cut Line= 2
2336095.06468854655712.7915542352336604.90310771656023.244344908
#Sta/Elev= 30
       0 2884.89    10.7 2880.47    29.4 2875.17    43.4 2869.47    57.5 2865.56
    76.2 2853.92    85.3 2852.84   108.4 2853.07   137.9 2857.17     167 2857.81
     199 2856.99   219.4 2858.32   254.3 2856.44   282.3 2857.15     301 2854.87
   316.1  2856.2   352.5 2854.75   362.2 2854.07     376 2854.86   385.3 2857.59
   394.7 2858.84   426.1    2858   446.2 2861.08   472.6 2869.81   488.4 2877.14
   502.4 2880.99   527.9 2890.86   577.6 2904.26   589.1 2908.19   596.9 2909.55
#Mann= 4 ,-1,0
       0     .06       0      90      .1       0   352.5    .045       0
     376      .1       0
#XS Ineff= 2 , 0
                          397.85          2869.3
Permanent Ineff=
       F       F
Bank Sta=352.5,376
XS Rating Curve= 0 ,0
Exp/Cntr(USF)=0,0
Exp/Cntr=0.3,0.1

Type RM Length L Ch R = 1 ,4533    ,115.8,122.8,120.2
XS GIS Cut Line= 2
 2336042.8765039655815.8297649322336425.58985792656151.707568635
#Sta/Elev= 30
       0 2886.27     7.5 2882.07      23  2875.1    30.2 2872.25    44.5 2868.07
    61.4 2859.11    68.8 2856.36    75.6 2854.77    89.7 2852.86   108.2 2852.06
   117.3 2852.58   124.1 2854.22   145.4 2853.99   156.1 2856.58   161.4 2856.79
     206 2856.63   231.5 2854.02   248.5 2853.06     257 2854.03   285.3 2855.01
     337 2853.97     378 2854.17   395.6 2853.26   421.4 2854.04   432.6 2858.19
   444.7 2865.75   459.4 2870.22   470.1 2875.56   486.6 2881.44   509.2 2892.06
#Mann= 4 ,-1,0
       0     .06       0      40      .1       0   231.5    .045       0
     257      .1       0
Bank Sta=231.5,257
XS Rating Curve= 0 ,0
Exp/Cntr(USF)=0,0
Exp/Cntr=0.3,0.1

Type RM Length L Ch R = 1 ,4410    ,317.3,334.5,327.1
XS GIS Cut Line= 2
2335953.44070488655883.4806371132336407.40235887656286.517999882
#Sta/Elev= 30
       0 2898.64    11.6 2897.51    34.3 2882.97      60 2868.69    79.6 2856.26
    92.9 2855.26   105.1 2851.21     117 2850.88   137.4 2852.75   173.1 2851.31
   187.3 2852.83   198.6 2851.54     223 2853.81   276.5 2853.42   303.2 2851.76
   314.8  2853.4   394.1 2855.72     431 2853.14   448.4 2853.78   454.4 2856.01
   467.8 2865.89   474.4 2868.87   490.4  2878.8     499 2881.55   527.9 2897.72
   552.8 2915.14   558.5  2916.9     587  2920.7     601 2931.72   607.1 2934.76
#Mann= 4 ,-1,0
       0     .06       0      60      .1       0   276.5    .045       0
   314.8      .1       0
Bank Sta=276.5,314.8
XS Rating Curve= 0 ,0
Exp/Cntr(USF)=0,0
Exp/Cntr=0.3,0.1

Type RM Length L Ch R = 1 ,4076    ,198.1,196.2,196.9
XS GIS Cut Line= 2
2335845.63763746655980.7559218752336145.09858252656385.102718439
#Sta/Elev= 30
       0 2897.21    10.5 2897.14    15.5 2896.42    19.3 2895.04    24.4 2892.17
    30.4 2887.24    40.3  2876.5    47.9 2870.12    59.3 2861.21    75.82851.243
    79.3 2850.15    90.8 2849.95   107.9 2850.14     115 2851.24   129.9 2852.77
   149.9 2850.97     168 2850.16   185.7  2850.3     228 2856.28   252.9 2857.25
   273.8 2855.33   313.8 2856.49   378.8 2856.83   383.8 2857.39   394.1 2860.41
   414.2  2870.2   438.6 2878.07   463.4  2884.2   488.3 2889.28   503.2 2893.21
#Mann= 3 ,-1,0
       0      .1       0    75.8    .045       0     115      .1       0
#XS Ineff= 2 , 0
                           253.7         2863.07
Permanent Ineff=
       F       F
Bank Sta=75.8,115
XS Rating Curve= 0 ,0
Exp/Cntr(USF)=0,0
Exp/Cntr=0.3,0.1