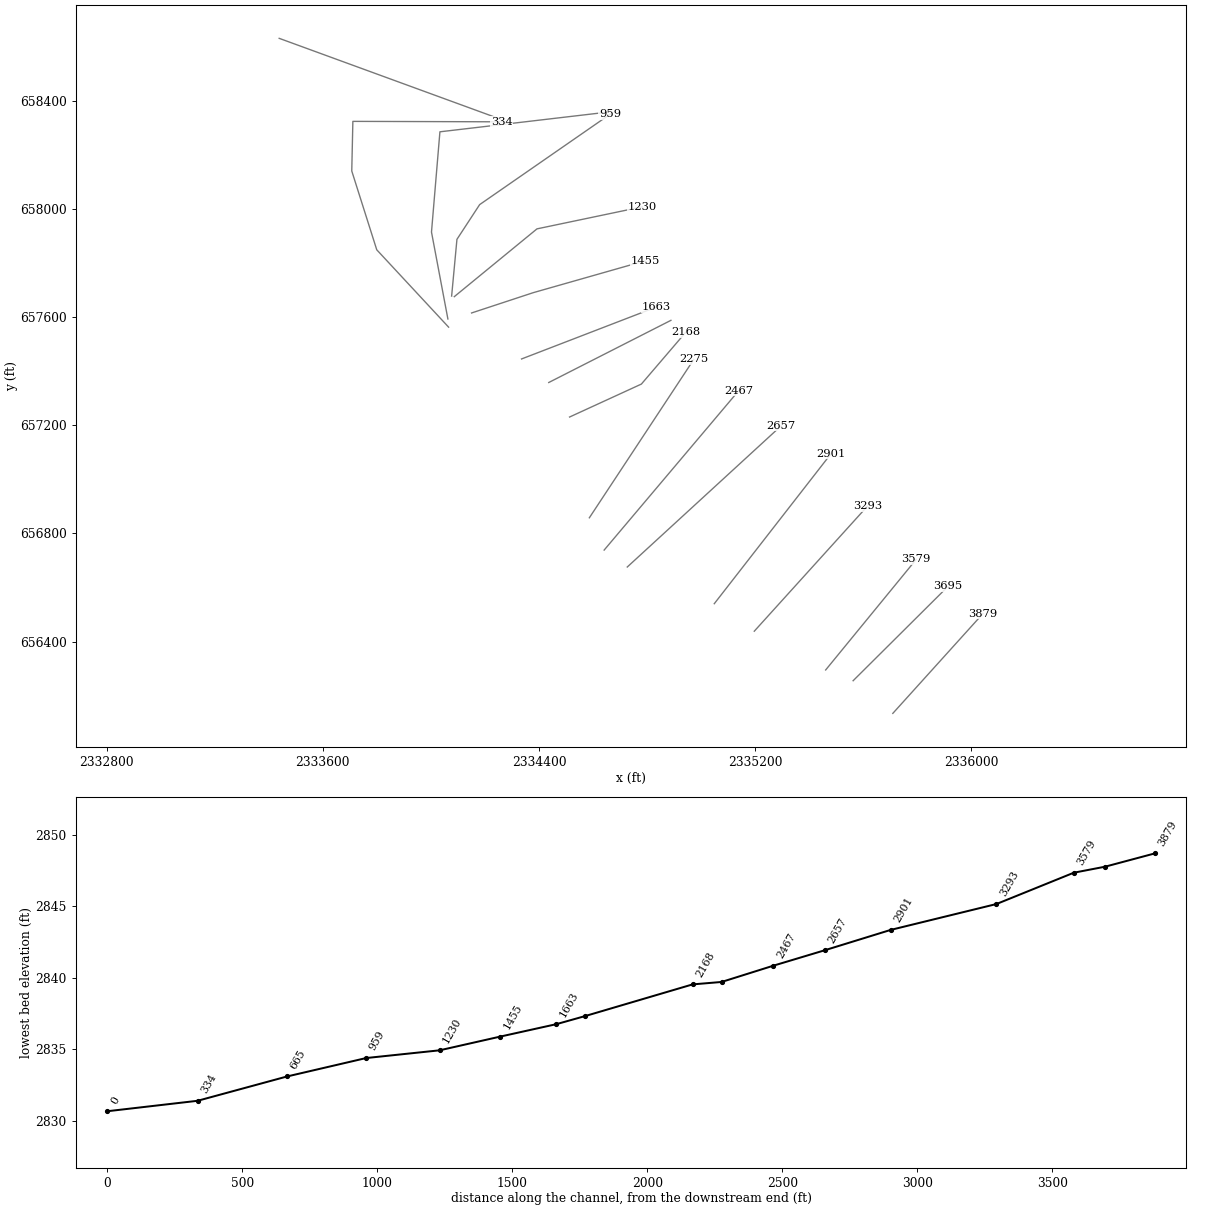
HEC-RAS study EFKGLADYFK.prj: EFKGLADYFK

--- EFKGLADYFK.g01 (geometry) --- (continued)

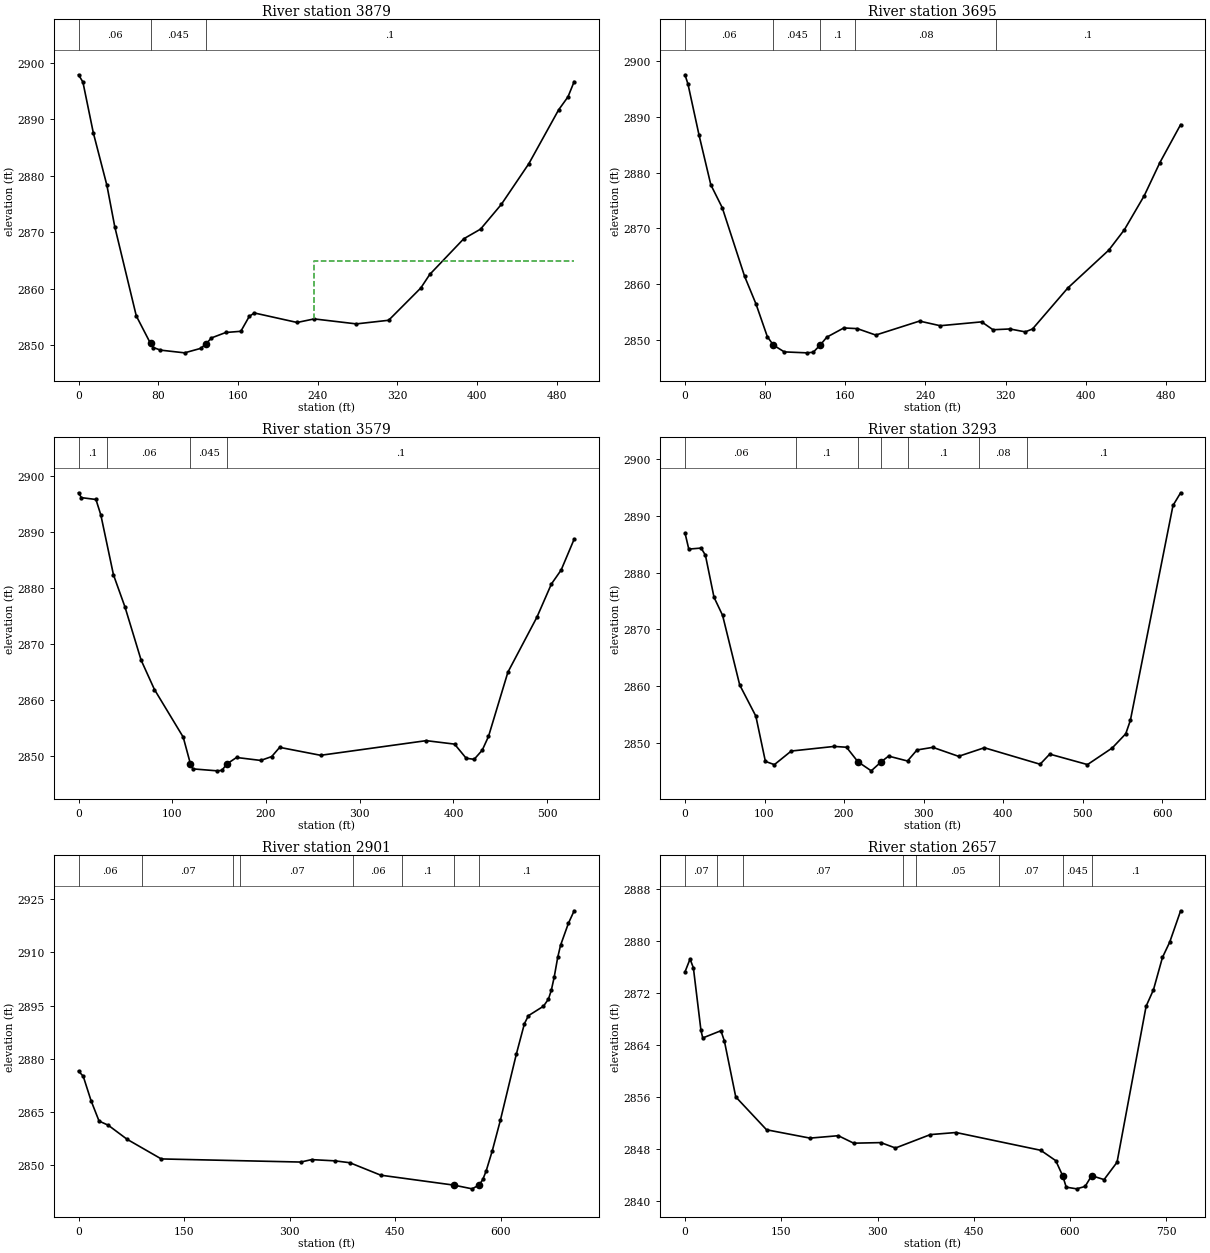
Type RM Length L Ch R = 1 ,3879    ,185.6,184.4,183
XS GIS Cut Line= 2
2335709.03781368656134.1389340042336042.64329689656503.438831051
#Sta/Elev= 30
       0 2897.87     4.4 2896.59    14.9 2887.58    28.5 2878.32    36.4    2871
      58 2855.23    72.3 2850.35    75.2 2849.63    82.3 2849.17   106.5 2848.69
   122.7 2849.48   128.1 2850.29   133.5 2851.33   147.9 2852.29     163  2852.5
   171.5 2855.15   176.6 2855.74   219.5 2854.06   236.6 2854.69     279 2853.81
   311.4 2854.45   343.7 2860.16   352.7 2862.56   386.8 2868.86   403.7 2870.57
   424.5 2874.93   452.2 2882.15   482.1 2891.67   491.5 2893.97   497.7 2896.66
#Mann= 3 ,-1,0
       0     .06       0    72.3    .045       0   128.1      .1       0
#XS Ineff= 2 , 0
                          236.29         2864.87
Permanent Ineff=
       F       F
Bank Sta=72.3,128.1
XS Rating Curve= 0 ,0
Exp/Cntr(USF)=0,0
Exp/Cntr=0.3,0.1

Type RM Length L Ch R = 1 ,3695    ,112.9,115.7,118
XS GIS Cut Line= 2
2335562.17350858656254.9651226132335912.97868438 656603.73073344
#Sta/Elev= 30
       0 2897.49       3 2895.82    14.1 2886.65    25.8 2877.81    37.2 2873.72
    59.5 2861.45    70.9 2856.49    82.2 2850.65    88.2 2849.15    99.1 2847.93
   121.3 2847.76     128 2847.86  135.092849.186   141.6 2850.57   158.5 2852.21
     172 2852.09   190.4 2850.94   234.1 2853.44   254.7 2852.61   296.1  2853.3
   307.4 2851.89   324.3 2852.03   339.6 2851.51   346.9 2852.03     382 2859.34
     423 2866.13   438.6 2869.79   458.4 2875.87     474 2881.79   494.7 2888.58
#Mann= 5 ,-1,0
       0     .06       0    88.2    .045       0  135.09      .1       0
     170     .08       0     310      .1       0
Bank Sta=88.2,135.09
XS Rating Curve= 0 ,0
Exp/Cntr(USF)=0,0
Exp/Cntr=0.3,0.1

Type RM Length L Ch R = 1 ,3579    ,288.1,286.5,285.4
XS GIS Cut Line= 2
2335460.54977887656294.7637962892335795.52812415656703.876693389
#Sta/Elev= 30
       0 2897.08     3.1 2896.21    18.6 2895.88    23.8 2893.12    37.3  2882.4
    49.6 2876.64    66.8 2867.14      81 2861.89   111.7 2853.37   119.4 2848.58
     122 2847.69   147.9 2847.34     153 2847.42   158.2 2848.56   168.6 2849.73
   194.4  2849.2   206.1 2849.89   214.6 2851.54   258.3 2850.12     371 2852.74
   401.2 2852.12   413.6 2849.59   422.1  2849.4   430.7 2851.03   437.4 2853.49
   458.1 2864.99   489.1 2874.84   504.5 2880.76   514.9 2883.26   528.8 2888.79
#Mann= 4 ,-1,0
       0      .1       0      30     .06       0   119.4    .045       0
   158.2      .1       0
Bank Sta=119.4,158.2
XS Rating Curve= 0 ,0
Exp/Cntr(USF)=0,0
Exp/Cntr=0.3,0.1

Type RM Length L Ch R = 1 ,3293    ,385.4,391.7,392.9
XS GIS Cut Line= 2
2335196.41024099656438.1411426082335614.57976425656900.157273902
#Sta/Elev= 30
       0 2886.98     4.8 2884.13    20.3 2884.31    25.7 2883.05    36.5 2875.66
    47.3 2872.48    68.8 2860.25    89.1 2854.77   101.1 2846.81   112.4 2846.24
   133.6 2848.63   187.5 2849.44   203.1  2849.3   217.52846.737   234.2 2845.15
   246.9 2846.76     256 2847.74   279.8 2846.88   291.7 2848.82   311.6 2849.28
     344  2847.7   376.4 2849.21   446.5 2846.31   458.6 2848.09   506.1 2846.25
   537.2 2849.17   554.2 2851.67     560 2854.02   613.6  2891.8   623.2 2894.03
#Mann= 7 ,-1,0
       0     .06       0     140      .1       0   217.5    .045       0
   246.9     .06       0     280      .1       0     370     .08       0
     430      .1       0
Bank Sta=217.5,246.9
XS Rating Curve= 0 ,0
Exp/Cntr(USF)=0,0
Exp/Cntr=0.3,0.1

Type RM Length L Ch R = 1 ,2901    ,247.3,243.7,237.7
XS GIS Cut Line= 2
2335048.40890953656539.9157711762335480.92316021657095.597099154
#Sta/Elev= 30
       0 2876.54     6.7 2875.08    17.8  2868.2    29.2 2862.44    42.2 2861.28
    69.1  2857.3   117.6 2851.77   315.9 2850.89   331.1 2851.58   364.3 2851.23
   385.5  2850.7   429.4 2847.19   533.6 2844.38   559.2 2843.34   569.3 2844.44
   574.4 2845.98   579.2  2848.4   587.9 2854.09   599.3 2862.62   622.1 2881.36
   633.5 2889.88   639.2 2892.15   660.6 2894.82   667.7 2896.84   671.8 2899.38
   675.8 2902.99   680.8 2908.56   684.8 2911.96     696 2918.18   704.2 2921.72
#Mann= 8 ,-1,0
       0     .06       0      90     .07       0     220     .05       0
     230     .07       0     390     .06       0     460      .1       0
   533.6    .045       0   569.3      .1       0
Bank Sta=533.6,569.3
XS Rating Curve= 0 ,0
Exp/Cntr(USF)=0,0
Exp/Cntr=0.3,0.1

Type RM Length L Ch R = 1 ,2657    ,183.6,190.5,190.9
XS GIS Cut Line= 2
2334726.49653559656675.6712911412335295.53516378657197.799924894
#Sta/Elev= 30
       0 2875.23     7.9 2877.21    13.1 2875.86    24.9 2866.25    27.7 2865.09
      56  2866.2    61.4 2864.62    79.1 2856.04   127.1 2850.99   194.8 2849.71
   238.9 2850.08   262.9 2848.93   305.2 2849.02     328 2848.19   382.3 2850.25
   422.3 2850.57   554.3 2847.84   577.7 2846.25   588.6 2843.91     594 2842.18
   610.3 2841.92   623.5 2842.29   633.6 2843.94     653 2843.34   673.2    2846
   718.5 2869.96     730  2872.5     744 2877.46   755.3 2879.81   772.3 2884.62
#Mann= 8 ,-1,0
       0     .07       0      50     .05       0      90     .07       0
     340     .06       0     360     .05       0     490     .07       0
   588.6    .045       0   633.6      .1       0
Bank Sta=588.6,633.6
XS Rating Curve= 0 ,0
Exp/Cntr(USF)=0,0
Exp/Cntr=0.3,0.1

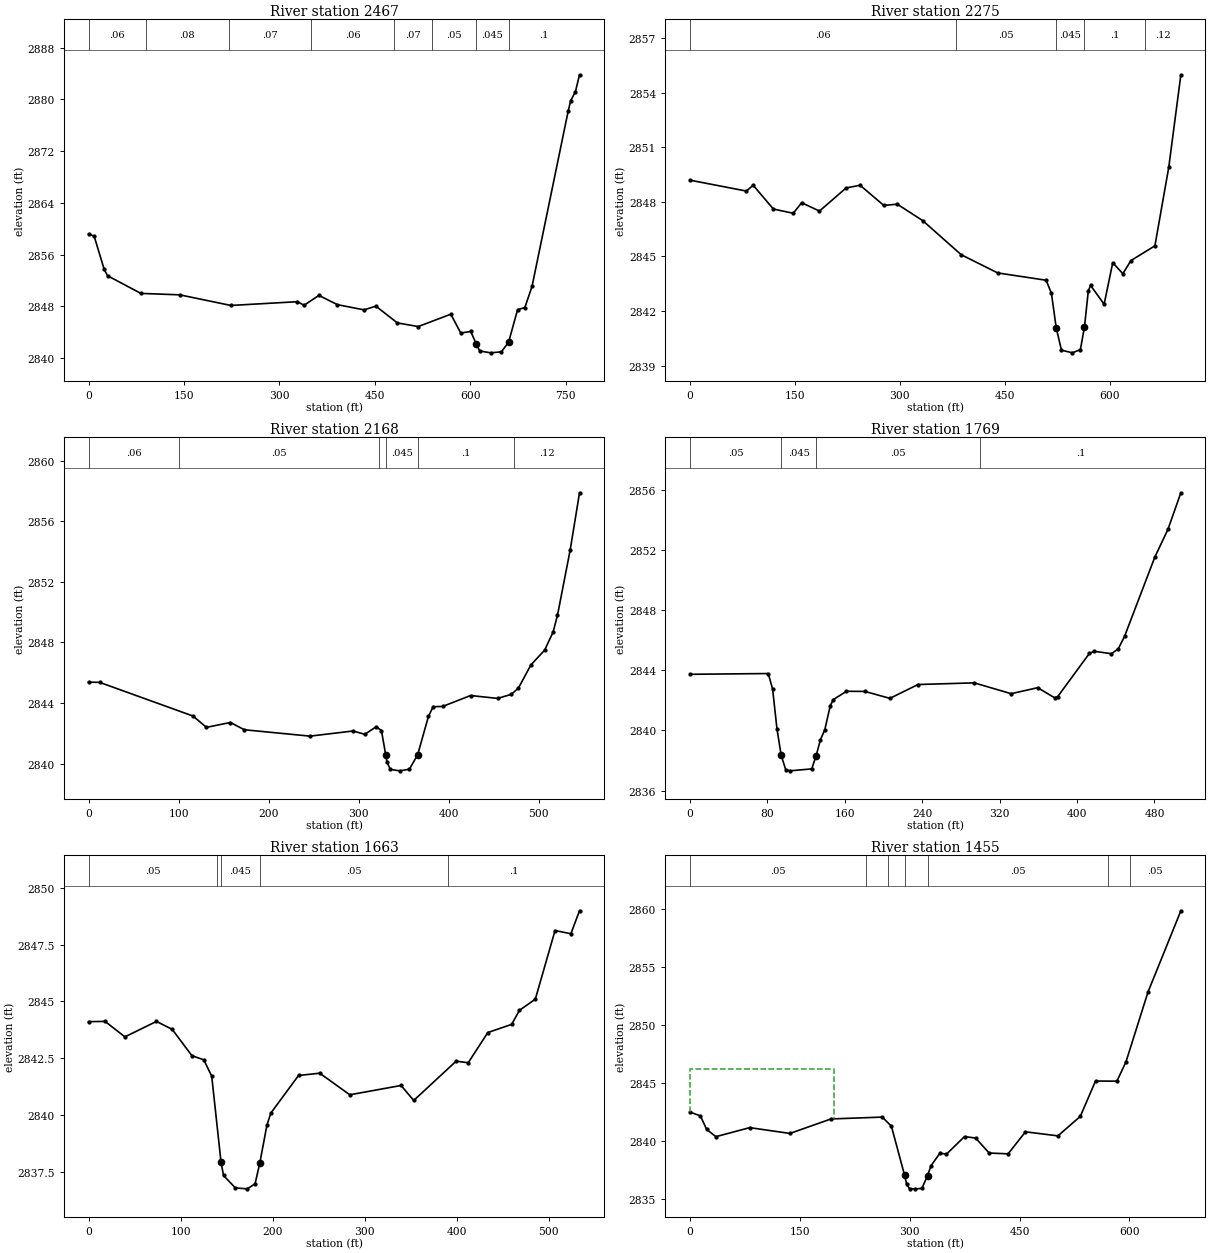
Type RM Length L Ch R = 1 ,2467    ,185.3,192,193.7
XS GIS Cut Line= 2
2334640.99614394656738.3572165272335138.64999799657327.791494474
#Sta/Elev= 30
       0 2859.22     8.9 2858.84    24.6 2853.73    29.9 2852.75    82.2 2850.02
   143.3  2849.8   223.6 2848.16   328.3 2848.74   338.7 2848.19   361.9 2849.71
   391.1 2848.28   432.8 2847.48   451.4 2848.05   485.3 2845.46     518  2844.9
   569.2 2846.81   584.8  2843.9   600.5 2844.14   608.9 2842.27   614.5 2841.13
   631.9 2840.84   648.6    2841   659.9 2842.46   674.1 2847.51   685.5 2847.83
   696.8 2851.11   753.6 2878.19   757.5 2879.78     765  2881.2   771.4 2883.79
#Mann= 8 ,-1,0
       0     .06       0      90     .08       0     220     .07       0
     350     .06       0     480     .07       0     540     .05       0
   608.9    .045       0   659.9      .1       0
Bank Sta=608.9,659.9
XS Rating Curve= 0 ,0
Exp/Cntr(USF)=0,0
Exp/Cntr=0.3,0.1

Type RM Length L Ch R = 1 ,2275    ,111.9,107.3,106.2
XS GIS Cut Line= 2
2334586.21067426656857.7724253652334972.59042358657443.655006543
#Sta/Elev= 30
       0 2849.19    80.7 2848.59    90.5 2848.91   119.4  2847.6   147.8 2847.37
   159.8 2847.95   185.2 2847.49   223.3 2848.76   243.3 2848.91   277.2  2847.8
   296.4 2847.87     333 2846.96   387.9 2845.09   440.1 2844.09   509.2 2843.69
   516.8 2842.97   523.6 2841.08   531.1 2839.85   546.7  2839.7   558.2 2839.88
     564 2841.12   569.5  2843.1   572.7 2843.41   592.1 2842.37   604.4 2844.65
   618.9 2844.05   630.4 2844.77   664.7 2845.58   684.5  2849.9   701.8 2854.98
#Mann= 5 ,-1,0
       0     .06       0     380     .05       0   523.6    .045       0
     564      .1       0     650     .12       0
Bank Sta=523.6,564
XS Rating Curve= 0 ,0
Exp/Cntr(USF)=0,0
Exp/Cntr=0.3,0.1

Type RM Length L Ch R = 1 ,2168    ,407.1,399,394.7
XS GIS Cut Line= 3
2334513.03340147657230.6017750532334778.75967122657352.536773293
2334943.25688582657544.641912029
#Sta/Elev= 30
       0 2845.38    12.3 2845.37   115.9 2843.15     131  2842.4   157.5 2842.72
   173.2 2842.24     246 2841.82   293.8 2842.16   306.8 2841.94   319.5 2842.44
   325.3 2842.19   330.1 2840.57   331.4 2840.11   335.3 2839.62   345.9 2839.53
   356.4 2839.64  365.552840.594   377.5 2843.12   382.7 2843.76   393.3 2843.78
   424.3  2844.5   454.4 2844.31   469.7 2844.58   477.5    2845   491.3 2846.52
   506.6  2847.5   515.9 2848.68   520.8 2849.79     535 2854.13   545.3 2857.88
#Mann= 6 ,-1,0
       0     .06       0     100     .05       0  322.37      .1       0
   330.1    .045       0  365.55      .1       0  472.37     .12       0
Bank Sta=330.1,365.55
XS Rating Curve= 0 ,0
Exp/Cntr(USF)=0,0
Exp/Cntr=0.3,0.1

Type RM Length L Ch R = 1 ,1769    ,108.6,105.4,104.3
XS GIS Cut Line= 2
2334435.96127994657358.2884241532334888.04103756657588.354458568
#Sta/Elev= 30
       0 2843.73      81 2843.78    85.5 2842.74      90  2840.1   94.32 2838.35
      99 2837.39   103.4 2837.31   125.9 2837.44   130.4  2838.3   134.9 2839.38
   139.4 2840.04   145.1 2841.65   148.3 2842.05   161.8  2842.6   180.8 2842.59
   206.7 2842.13   235.7 2843.05   293.8 2843.16     332 2842.44   359.4 2842.84
   376.8 2842.17   380.1 2842.25   412.8 2845.12   417.6 2845.26   435.6  2845.1
   442.5 2845.41   449.1 2846.25   480.5 2851.54   493.9 2853.36   507.3  2855.8
#Mann= 4 ,-1,0
       0     .05       0   94.32    .045       0   130.4     .05       0
     300      .1       0
Bank Sta=94.32,130.4
XS Rating Curve= 0 ,0
Exp/Cntr(USF)=0,0
Exp/Cntr=0.3,0.1

Type RM Length L Ch R = 1 ,1663    ,212.1,208,207.6
XS GIS Cut Line= 2
2334335.34476668657445.4375913062334832.99862073657637.156699012
#Sta/Elev= 30
       0 2844.11      18 2844.12    39.5 2843.44    73.8 2844.12    90.9 2843.77
   112.3 2842.61   125.2 2842.43   133.8 2841.71   143.9 2837.93   146.6 2837.34
   159.5 2836.79   172.4 2836.75   180.9 2836.97   186.1  2837.9   193.8 2839.56
   198.1 2840.09   228.1 2841.74   251.1 2841.84   283.8 2840.89   339.5  2841.3
   353.2 2840.64   399.3 2842.37   412.4  2842.3   433.7 2843.63   459.6 2843.99
   468.1 2844.61   485.3  2845.1   506.7 2848.12   523.9 2847.98   533.3 2848.99
#Mann= 5 ,-1,0
       0     .05       0     140     .07       0   143.9    .045       0
   186.1     .05       0     390      .1       0
Bank Sta=143.9,186.1
XS Rating Curve= 0 ,0
Exp/Cntr(USF)=0,0
Exp/Cntr=0.3,0.1

Type RM Length L Ch R = 1 ,1455    ,226.7,224.7,227.6
XS GIS Cut Line= 3
2334150.46632115657615.6151976092334378.58174223657690.715401823
2334792.20732122657808.480156962
#Sta/Elev= 30
       0 2842.51    14.4 2842.17    22.9 2841.01    35.5 2840.38    81.7 2841.16
   136.6 2840.66   192.7 2841.91   262.6 2842.07   275.1 2841.28     293 2837.07
   295.9 2836.26     300 2835.89   307.6 2835.88   316.7 2835.91   324.4 2837.03
   329.2 2837.88   341.6 2838.98   349.9 2838.85   374.9 2840.39   390.1 2840.26
   408.5 2838.97   434.4  2838.9   458.1  2840.8   502.4 2840.45   532.9 2842.13
   553.7 2845.18   582.9 2845.17   595.3 2846.84   625.4 2852.87   670.2 2859.87
#Mann= 7 ,-1,0
       0     .05       0     240     .06       0  270.16     .05       0
     293    .045       0   324.4     .05       0  570.16      .1       0
  600.16     .05       0
#XS Ineff= 2 , 0
          196.27 2846.24
Permanent Ineff=
       F       F
Bank Sta=293,324.4
XS Rating Curve= 0 ,0
Exp/Cntr(USF)=0,0
Exp/Cntr=0.3,0.1

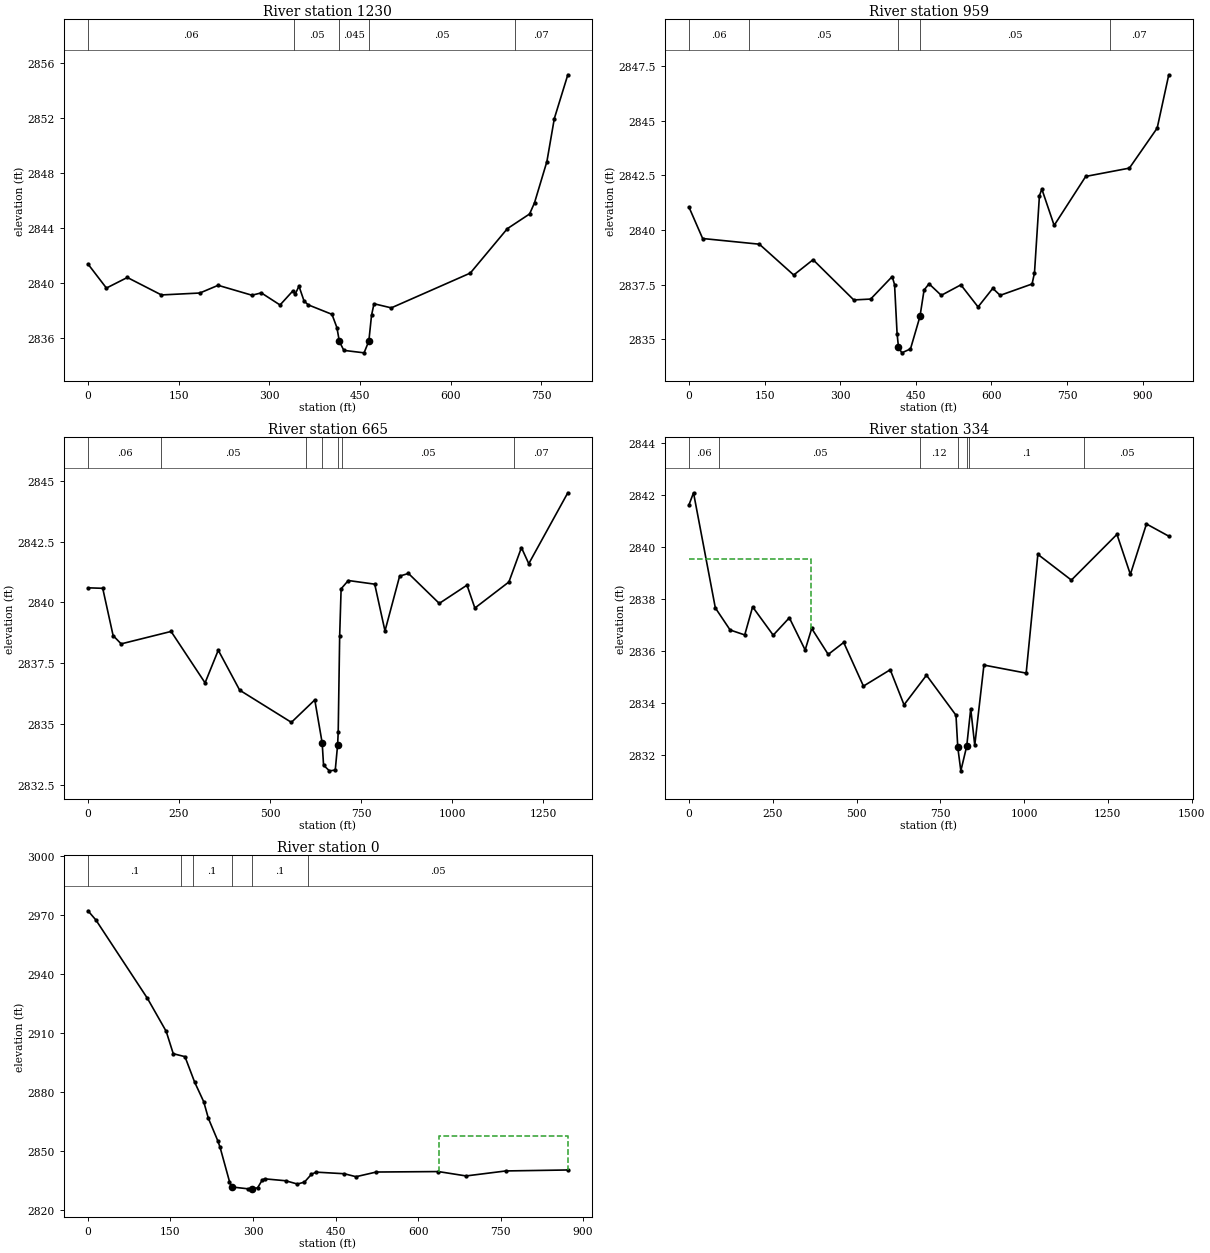
Type RM Length L Ch R = 1 ,1230    ,255.5,271.9,276.9
XS GIS Cut Line= 3
2334086.45142964657675.909886769  2334392.452586657926.774925546
2334782.00949634 658008.35752457
#Sta/Elev= 30
       0 2841.38    30.5 2839.63    65.1  2840.4   121.5 2839.13     185 2839.27
   215.3 2839.83   271.2 2839.11   286.7 2839.28   317.7  2838.4   338.4  2839.4
   343.2 2839.23     349 2839.77   357.4 2838.69   364.3 2838.41   403.6 2837.72
   411.8 2836.75   415.8 2835.75   423.2  2835.1   456.7 2834.92   464.6 2835.78
     469 2837.64   473.1 2838.49   501.7 2838.19   632.4 2840.72   693.7 2843.95
   730.5 2845.02   738.6 2845.83   759.1 2848.83   771.4 2851.96   793.7 2855.14
#Mann= 5 ,-1,0
       0     .06       0     340     .05       0   415.8    .045       0
   464.6     .05       0  705.69     .07       0
Bank Sta=415.8,464.6
XS Rating Curve= 0 ,0
Exp/Cntr(USF)=0,0
Exp/Cntr=0.3,0.1

Type RM Length L Ch R = 1 ,959     ,277.4,293.3,314
XS GIS Cut Line= 4
2334076.66469257657678.1256635592334096.31190675657888.018256863
2334180.33782854658016.5157844722334663.04358101658350.986906174
#Sta/Elev= 30
       0 2841.05    27.2 2839.61   139.7 2839.35   207.8 2837.94   246.2 2838.64
   326.9  2836.8   360.4 2836.84   403.1 2837.87   407.8  2837.5   412.8 2835.26
   415.62834.636   422.2 2834.38   439.4 2834.56   458.22836.045   466.3 2837.25
   476.1 2837.54   500.4 2837.01   539.3 2837.49   573.4 2836.48   602.6 2837.33
   617.2 2837.01   680.5 2837.53   685.3 2838.04   695.1 2841.57   699.9 2841.87
   724.3 2840.21   786.9 2842.45   873.5 2842.83   928.6 2844.66   951.6  2847.1
#Mann= 5 ,-1,0
       0     .06       0     120     .05       0   415.6    .045       0
   458.2     .05       0  834.34     .07       0
Bank Sta=415.6,458.2
XS Rating Curve= 0 ,0
Exp/Cntr(USF)=0,0
Exp/Cntr=0.3,0.1

Type RM Length L Ch R = 1 ,665     ,328.2,331.2,330.1
XS GIS Cut Line= 4
2334062.83202505 657593.365038562334002.14123594657914.930278371
2334033.31205266658285.8836415042334646.58946712658357.851493262
#Sta/Elev= 30
       0  2840.6    40.5 2840.58      69 2838.64    91.1  2838.3   228.1 2838.81
   321.4  2836.7   357.6 2838.04   416.4  2836.4   558.3 2835.08   622.5    2836
   642.82834.236   646.6 2833.32   662.7 2833.09   678.7 2833.12   685.12834.141
   686.8 2834.67   690.8 2838.62   694.8 2840.56   714.5  2840.9     787 2840.75
   815.2 2838.83   855.4 2841.08   879.6 2841.19   964.2 2839.96  1040.3 2840.71
  1061.9 2839.77  1155.3 2840.84  1189.7 2842.25  1209.8 2841.59    1317  2844.5
#Mann= 7 ,-1,0
       0     .06       0     200     .05       0  597.24      .1       0
   642.8    .045       0   685.1      .1       0  697.24     .05       0
  1169.5     .07       0
Bank Sta=642.8,685.1
XS Rating Curve= 0 ,0
Exp/Cntr(USF)=0,0
Exp/Cntr=0.3,0.1

Type RM Length L Ch R = 1 ,334     ,365.8,334.1,316.7
XS GIS Cut Line= 5
2334065.50001823657563.1310513362333799.62115625657849.317251041
 2333707.1587542658140.9292479842333711.23788415658324.490095787
2334262.75994012658322.876786537
#Sta/Elev= 30
       0 2841.62    13.7 2842.09    78.8 2837.66   122.9 2836.81   166.5 2836.62
     190  2837.7   251.5 2836.61   299.6 2837.28   346.8 2836.04   366.3 2836.87
   415.6 2835.87   461.8 2836.33   520.7 2834.65   600.6 2835.28   641.8 2833.93
   708.8 2835.07   796.8 2833.53   802.2 2832.29   811.3 2831.39   828.92832.343
   840.8 2833.78   852.8 2832.37   880.2 2835.46  1006.2 2835.15  1041.1 2839.72
  1141.1 2838.73  1277.1 2840.49  1317.1 2838.95  1365.1 2840.89  1431.7 2840.42
#Mann= 7 ,-1,0
       0     .06       0      90     .05       0  690.63     .12       0
   802.2    .045       0   828.9     .05       0  836.55      .1       0
 1180.16     .05       0
#XS Ineff= 2 , 0
          364.95 2839.53
Permanent Ineff=
       F       F
Bank Sta=802.2,828.9
XS Rating Curve= 0 ,0
Exp/Cntr(USF)=0,0
Exp/Cntr=0.3,0.1

Type RM Length L Ch R = 1 ,0       ,253.6,245.3,242.7
XS GIS Cut Line= 2
2333438.58642161658631.7211917232334257.86126192658332.419547275
#Sta/Elev= 30
       0 2972.05    14.5 2967.33   108.2 2927.46   142.2 2910.73     155 2899.38
   176.3 2897.87   193.9 2884.91   210.4 2874.95   218.9 2866.47   235.9 2855.15
   240.2 2851.69   257.2 2834.39   261.5 2831.61   291.3 2830.66   298.8 2830.75
   308.3 2831.17   316.8 2835.14   321.1 2835.75   359.4 2834.77   380.7  2833.1
   393.5 2834.08   406.3  2838.1   414.8 2839.15   465.9 2838.34   487.2 2836.83
   524.1 2839.21   636.9 2839.44   687.3 2837.22   759.7 2839.76   872.2 2840.25
#Mann= 6 ,-1,0
       0      .1       0     170     .06       0     190      .1       0
   261.5    .045       0   298.8      .1       0     400     .05       0
#XS Ineff= 2 , 0
                          638.21         2857.39
Permanent Ineff=
       F       F
Bank Sta=261.5,298.8
XS Rating Curve= 0 ,0
Exp/Cntr=0.3,0.1
LCMann Table=0

Chan Stop Cuts=-1
Use User Specified Reach Order=0
Composite Channel Slope=5